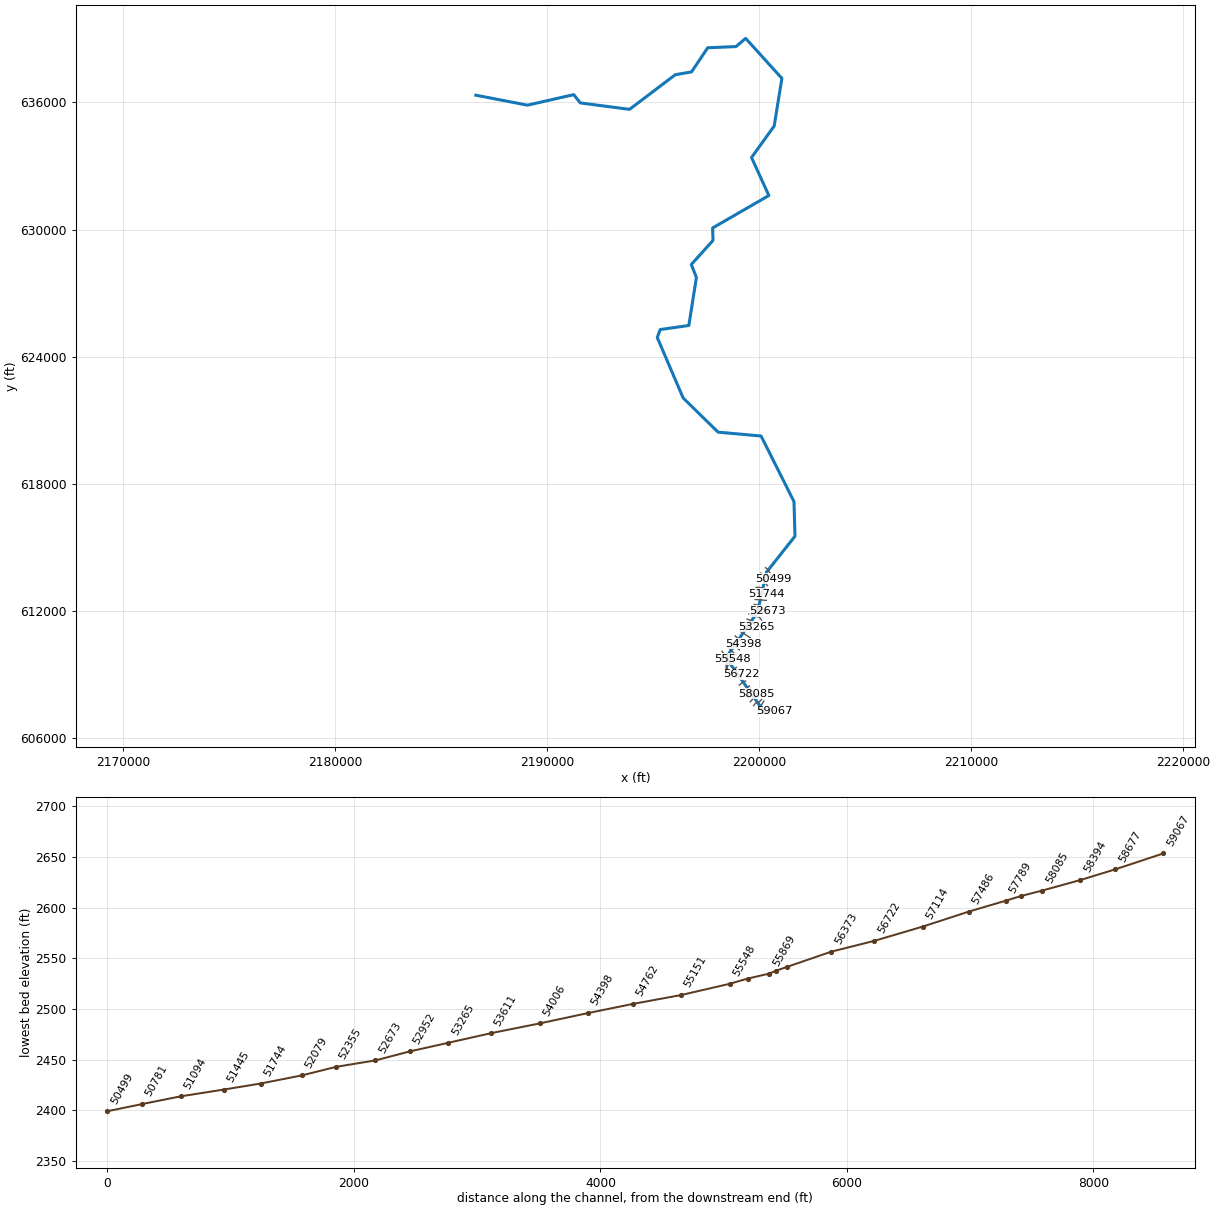
--- LFRFBUCRV.prj (project) ---

Proj Title=LFRFBUCRV
Current Plan=p01
Default Exp/Contr=0,0
English Units
Geom File=g01
Flow File=f01
Plan File=p01
BEGIN DESCRIPTION:
----------MODEL BY WOOD PLC 2022----------
AFH study
Randolph County, WV
HEC-RAS Version: RAS 6.2
Vertical Datum: NAVD88
Projection: NAD 1983 StatePlane West Virginia S FIPS 4702 (US Feet)
Terrain: 1-meter LIDAR (FEMA Region III 3DEP collected 2016-2018)
Land Use: 2019 NLCD
Hydrologic Method:
WV SIR2010-5033 regression equations
Additional Model Notes:
Added shared XS with SALTBLKRN to establish backwater tie-in
END DESCRIPTION:
DSS Export Rating Curves= 0
DSS Export Rating Curve Sorted= 0
DSS Export Volume Flow Curves= 0
DXF OffsetX= 0
DXF OffsetY= 0
DXF ScaleX= 0
DXF ScaleY= 0

--- LFRFBUCRV.p01 (plan) ---

Plan Title=Floodplain
Program Version=6.20
Short Identifier=Floodplain
Geom File=g01
Flow File=f01
Subcritical Flow
K Sum by GR= 0
Std Step Tol= 0.01
Critical Tol= 0.01
Num of Std Step Trials= 20
Max Error Tol= 0.3
Flow Tol Ratio= 0.001
Split Flow NTrial= 30
Split Flow Tol= 0.02
Split Flow Ratio= 0.02
Log Output Level= 0
Friction Slope Method= 1
Unsteady Friction Slope Method= 2
Unsteady Bridges Friction Slope Method= 1
Parabolic Critical Depth
Global Vel Dist= 0 , 0 , 0
Global Log Level= 0
CheckData=True
Encroach Param=-1 ,0,0, 0
Mapping Interval=1HOUR
Computation Time Step Use Courant=        0
Computation Time Step Use Time Series=    0
Computation Time Step Count To Double=0
Computation Time Step Max Doubling=0
Computation Time Step Max Halving=0
Computation Time Step Residence Courant=0
Run HTab= 0
Run UNet= 0
Run Sediment= 0
Run PostProcess= 0
Run WQNet= 0
Run RASMapper=-1
UNET Theta= 0
UNET Theta Warmup= 0
UNET ZTol= 0
UNET ZSATol= 0
UNET MxIter= 0
UNET Max Iter WO Improvement= 0
UNET MaxInSteps= 0
UNET DtIC= 0
UNET DtMin= 0
UNET MaxCRTS= 0
UNET WFStab= 0
UNET SFStab= 0
UNET WFX= 1
UNET SFX= 1
UNET Gravity=32.174
UNET 1D Methodology=Finite Difference
UNET DSS MLevel= 1
UNET Pardiso=0
UNET DZMax Abort= 0
UNET Use Existing IB Tables= 0
UNET Froude Reduction=False
UNET Froude Limit= 0
UNET Froude Power= 0
UNET D1 Cores= 0
UNET WindReference=Eulerian
UNET WindDragFormulation=Hsu (1988)
UNET D2 Coriolis=0
UNET D2 Cores= 0
UNET D2 Theta= 1
UNET D2 Theta Warmup= 1
UNET D2 Z Tol= 0.01
UNET D2 Volume Tol= 0.01
UNET D2 Max Iterations= 20
UNET D2 Equation= 0
UNET D2 RampUpFraction=0.1
UNET D2 TimeSlices= 1
UNET D2 Turbulence Formulation=Non-Conservative (original)
UNET D2 Eddy Viscosity=0.3
UNET D2 Transverse Eddy Viscosity=0.1
UNET D2 Smagorinsky Mixing=0
UNET D2 BCVolumeCheck=0
UNET D2 Cores=0
UNET D2 SolverType=PARDISO (Direct)
UNET D2 Minimum Iterations= 2147483647
UNET D2 Maximum Iterations= 2147483647
UNET D2 Restart Number= 10
UNET D2 Relaxation Coeff=1.3
UNET D2 SOR Precondition Iterations= 10
UNET D2 ILUT Maximum Fill= 8
UNET D2 ILUT Tolerance=1E-08
UNET D1D2 MaxIter= 0
UNET D1D2 ZTol=0.01
UNET D1D2 QTol=0.1
UNET D1D2 MinQTol=1
Write IC File= 0
Write IC File at Fixed DateTime=0
Write IC File at Sim End=0
Echo Input=False
Echo Parameters=False
Echo Output=False
Write Detailed= 0
HDF Write Warmup=0
HDF Write Time Slices=0
HDF Flush=0
HDF Compression= 1
HDF Chunk Size= 1
HDF Spatial Parts= 1
HDF Use Max Rows=0
HDF Fixed Rows= 1
Calibration Method= 0
Calibration Iterations= 20
Calibration Max Change=0.05
Calibration Tolerance=0.2
Calibration Maximum=1.5
Calibration Minimum=0.5
Calibration Optimization Method= 1
WQ AD Non Conservative
WQ ULTIMATE=-1
WQ Max Comp Step=1HOUR
WQ Output Interval=15MIN
WQ Output Selected Increments= 0
WQ Output face flow=0
WQ Output face velocity=0
WQ Output face area=0
WQ Output face dispersion=0
WQ Output cell volume=0
WQ Output cell surface area=0
WQ Output cell continuity=0
WQ Output cumulative cell continuity=0
WQ Output face conc=0
WQ Output face dconc_dx=0
WQ Output face courant=0
WQ Output face peclet=0
WQ Output face adv mass=0
WQ Output face disp mass=0
WQ Output cell mass=0
WQ Output cell source sink temp=0
WQ Output nsm pathways=0
WQ Output nsm derived pathways=0
WQ Create Restart=0
WQ Fixed Restart=0
WQ System Summary=0
WQ Write To DSS=0
Sorting and Armoring Iterations= 10
XS Update Threshold= 0.02
Bed Roughness Predictor= 0
Hydraulics Update Threshold= 0.02
Energy Slope Method= 1
Volume Change Method= 1
Sediment Retention Method= 0
Sediment TS Multiplier= 1
Warm Up Method= 0
XS Weighting Method= 0
Number of US Weighted Cross Sections= 1
Number of DS Weighted Cross Sections= 1
Upstream XS Weight=0
Main XS Weight=1
Downstream XS Weight=0
Number of DS XS's Weighted with US Boundary= 1
Upstream Boundary Weight= 1
Weight of XSs Associated with US Boundary= 0
Number of US XS's Weighted with DS Boundary= 1
Downstream Boundary Weight= 0.5
Weight of XSs Associated with DS Boundary= 0.5
Percentile Method= 0
Sediment Output Level= 3
Mass or Volume Output= 0
Output Increment Type= 1
Profile and TS Output Increment= 1
Transport Output Increment 1
XS Output Flag= 0
XS Output Increment= 10
Read HDF5 Sediment Hotstart= 0
Sediment Hotstart Type= 0
Write Gradation File= 0
Read Gradation Hotstart= 0
Write HDF5 File= 1
Write Binary Output= 1
Write DSS Sediment File= 0
DSS Sediment Output Type= 1
SV Curve= 0
Specific Gage Flag= 0
Subcell Erosion Methods= 0
Subcell Deposition Methods= 0
Advection Scheme= 1
Matrix Solver= 0
Implicit Weighting Factor= 1
Maximum Outer Loop Convergence Iterations= 5
Convergence Maximum Absolute= 0.001
Convergence RMSE= 0.0001
Grain Fractions Max Abs Error= 0.001
Max Subgrid Regions= 1
Max Subgrid Length Scale= 3.402823E+38
Initial Layer Thickness= 3.402823E+38
Min Layer Thickness= 3.402823E+38
Max Layer Thickness= 3.402823E+38
Number of Layers= 5

--- LFRFBUCRV.f01 (steady flow) ---

Flow Title=Flow
Program Version=6.20
Number of Profiles= 1
Profile Names=P100yr
River Rch & RM=LFRFBUCRV,Main,59067
     727
River Rch & RM=LFRFBUCRV,Main,51094
     820
River Rch & RM=LFRFBUCRV,Main,49850
    1100
River Rch & RM=LFRFBUCRV,Main,46470
    1380
River Rch & RM=LFRFBUCRV,Main,43332
    1580
River Rch & RM=LFRFBUCRV,Main,38450
    2210
River Rch & RM=LFRFBUCRV,Main,29488
    2720
River Rch & RM=LFRFBUCRV,Main,20950
    3030
Boundary for River Rch & Prof#=LFRFBUCRV,Main            , 1
Up Type= 0
Dn Type= 3
Dn Slope=0.011957
DSS Import GetInterval= 0
DSS Import GetPeak= 0
DSS Import FillOption= 0

--- LFRFBUCRV.g01 (geometry) ---

Geom Title=Geometry
Program Version=6.20

River Reach=LFRFBUCRV       ,Main
Reach XY= 30
2200278.73800004607211.3369999982198444.58400001609805.658000007
2199932.54100002611963.3510000112200351.02106965613834.559169009
2201699.03819487615538.8161471042201651.70000003617170.974000007
  2200099.254357620262.2484249032198074.05100003      620444.934
2196425.20900002 622055.880000012195204.19800001624909.024000004
2195342.95200004625282.3869999952196693.15900001625475.493000001
2197050.34200004627741.4382644742196810.52000003      628351.125
2197834.85900003629490.3560000212197813.08347383630071.997526169
2200466.15600003631604.0310000182199650.29800001633396.292999998
2200717.65499999634881.2720000152201081.61300002637129.733999997
2199371.51400004639016.9490000162198919.34900002638628.738000005
2197584.01000002638572.893000022      2196820.97637434.586999998
2196055.59346808637301.4281430392193894.99747384635667.410789937
2191572.79484296 635971.498157712191266.40100001636361.943210736
2189083.77499999635865.7080000192186646.64366651636335.791738245

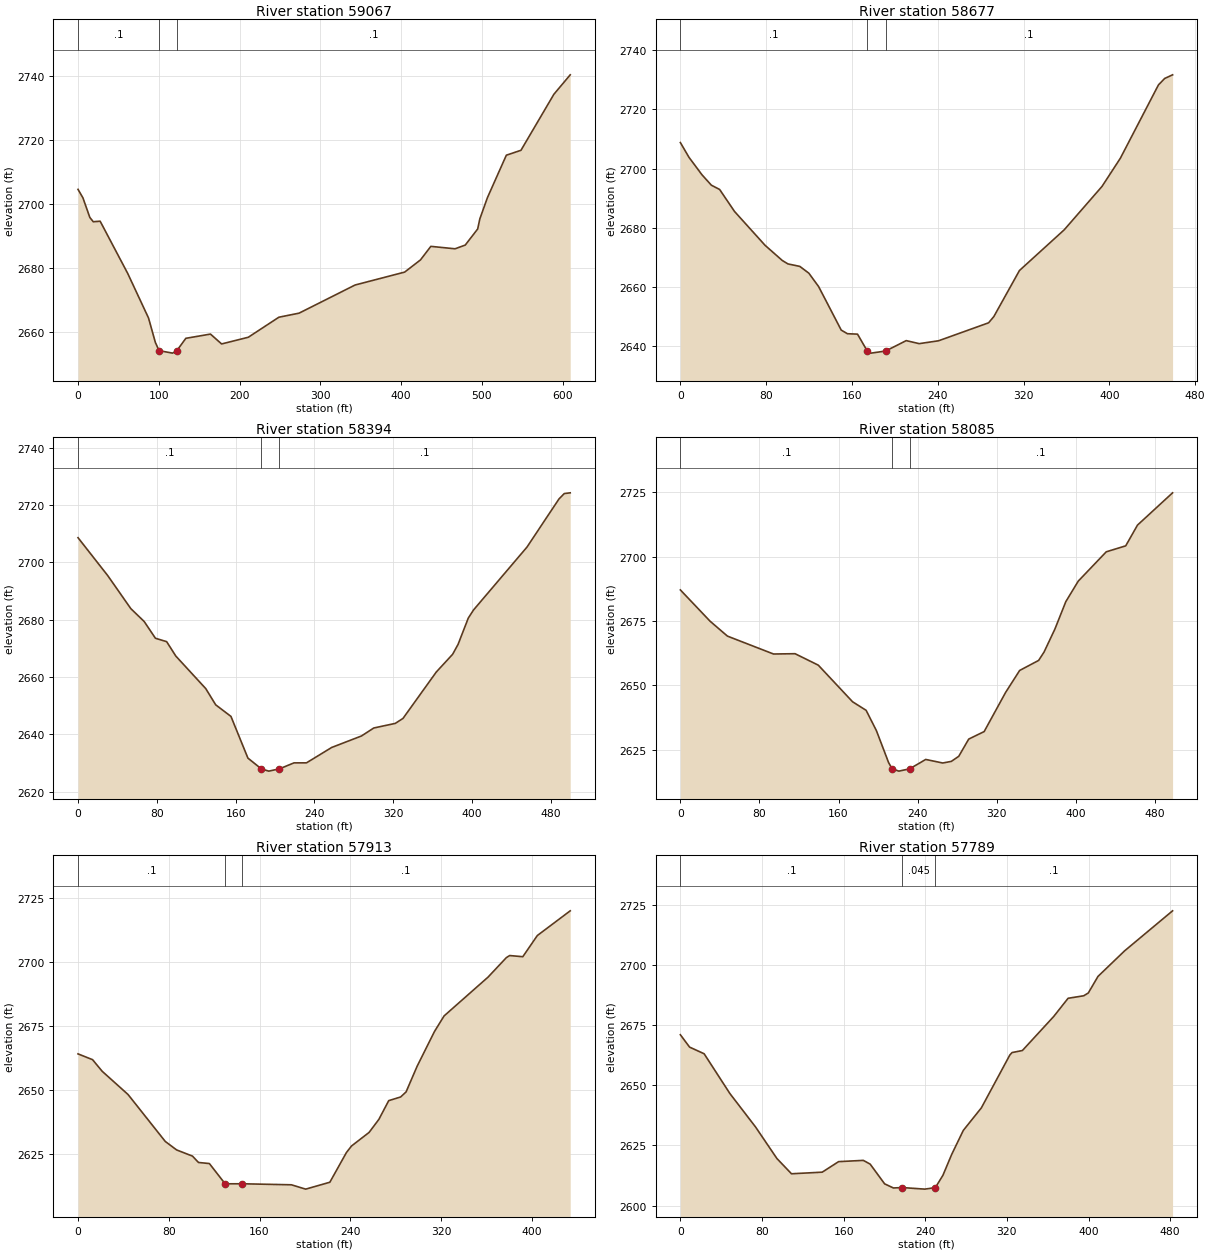
Type RM Length L Ch R = 1 ,59067   ,389.7,389.7,389.7
XS GIS Cut Line= 4
2200170.50396211607183.0220105532200253.25238602607214.263584123
 2200634.6059526 607354.859670762200725.36783104607284.825358905
#Sta/Elev= 30
       0 2704.64     6.1 2701.97    14.6 2695.87    18.9 2694.51    27.4 2694.68
    61.6 2678.31    87.3  2664.4    95.8 2656.74  100.372654.187   117.1 2653.41
  122.372654.188   133.5 2658.04     164 2659.37   177.8 2656.28   210.9 2658.38
   248.7 2664.64   273.7 2665.91   343.1 2674.72   404.5 2678.76   424.1 2682.58
   436.9 2686.81   466.9 2686.05   479.5 2687.21   494.9 2692.25   497.6 2695.44
     507 2702.06   530.4 2715.33   548.5 2716.86   589.3  2734.4   609.5 2740.47
#Mann= 3 ,-1,0
       0      .1       0  100.37    .045       0  122.37      .1       0
Bank Sta=100.37,122.37
XS Rating Curve= 0 ,0
Exp/Cntr=0.3,0.1

Type RM Length L Ch R = 1 ,58677   ,283.2,283.2,283.2
XS GIS Cut Line= 4
2199994.93646883607373.6392003852200072.07743989607462.000676336
2200145.01072163607624.6979971332200233.37219758607762.149181944
#Sta/Elev= 30
       0 2708.81       8 2703.84    20.1 2697.95    28.9 2694.42    36.6 2692.98
    50.5 2685.55      79 2674.12      95 2669.02   100.3 2667.85   111.4 2667.01
   119.8 2664.72   128.9 2660.21     150 2645.51   155.8 2644.29   165.2 2644.15
  174.292638.453   177.8 2637.74  191.432638.452   210.6 2641.96   222.7 2640.94
   240.8 2641.91   287.4 2647.97   292.3 2650.07   316.2 2665.62     358 2679.38
   393.2 2694.01   410.3 2703.52   445.8 2728.25   451.6 2730.43     459 2731.67
#Mann= 3 ,-1,0
       0      .1       0  174.29    .045       0  191.43      .1       0
Bank Sta=174.29,191.43
XS Rating Curve= 0 ,0
Exp/Cntr(USF)=0,0
Exp/Cntr=0.3,0.1

Type RM Length L Ch R = 1 ,58394   ,309,309,309
XS GIS Cut Line= 4
2199748.07811646607546.9326028972199835.04427425 607658.35951178
2200019.42244666607725.8758839082200128.67010633607845.617397829
#Sta/Elev= 30
       0 2708.64    30.2  2695.4    53.6 2683.89    67.2 2679.39    78.6 2673.55
      90 2672.36    99.3 2667.34   129.7 2655.98   139.8 2650.32   155.3 2646.27
   172.5 2631.73  186.192627.958   193.7 2627.18  204.412627.958   219.3 2630.06
     232 2630.07   257.6 2635.44   287.9 2639.46   300.3 2642.23   322.2 2643.84
     330 2645.58   363.8 2661.77   380.4 2667.96   385.9  2671.4   396.3  2680.6
   401.7 2683.46   455.9 2705.37   488.4 2722.17   493.8 2724.05   499.8  2724.3
#Mann= 3 ,-1,0
       0      .1       0  186.19    .045       0  204.41      .1       0
Bank Sta=186.19,204.41
XS Rating Curve= 0 ,0
Exp/Cntr=0.3,0.1

Type RM Length L Ch R = 1 ,58085   ,172,172,172
XS GIS Cut Line= 4
2199583.67975769 607724.493388792199695.66093201607844.134912477
2199762.11099251 607965.520832942199896.59964051 608107.62317432
#Sta/Elev= 30
       0 2687.06      30 2674.95    47.6 2669.15    94.2 2662.21     116 2662.33
   139.5 2657.89   174.2 2643.68   187.9 2640.37   198.3 2632.49   210.7 2620.04
  214.212617.684     221 2616.79  231.962617.684   248.2 2621.32   265.4 2619.94
   274.1 2620.57   281.6 2622.54   291.7 2629.22   307.3 2632.13   328.9 2647.25
   343.2 2655.83   362.4 2659.72   367.9 2662.98   378.9 2671.92   389.9 2682.52
   402.5 2690.48   430.8 2701.84   450.5 2704.16   462.4  2712.2   497.9 2724.72
#Mann= 3 ,-1,0
       0      .1       0  214.21    .045       0  231.96      .1       0
Bank Sta=214.21,231.96
XS Rating Curve= 0 ,0
Exp/Cntr=0.3,0.1

Type RM Length L Ch R = 1 ,57913   ,123.7,123.7,123.7
XS GIS Cut Line= 3
2199475.94017111607907.3401086792199534.39993047607961.902550751
 2199828.2576542608159.106805668
#Sta/Elev= 30
       0 2664.21    12.8 2661.96    21.3 2657.42    44.1 2648.36    76.9 2630.05
    86.9 2626.74   100.9 2624.32   106.2 2621.84   115.8 2621.42   129.7 2613.51
   144.7 2613.53   188.1 2613.13   200.7 2611.44     222 2614.13   236.6 2625.71
   241.1 2628.27   256.6 2633.57   265.2 2638.65   273.9 2645.97   284.4  2647.4
   289.2 2649.37   298.9 2659.35   314.2 2672.92   322.7 2679.02   361.5 2694.18
   377.6 2701.77   380.5 2702.58   392.1 2702.13   404.9 2710.39   433.9 2720.03
#Mann= 3 ,-1,0
       0      .1       0   129.7    .045       0   144.7      .1       0
Bank Sta=129.7,144.7
XS Rating Curve= 0 ,0
Exp/Cntr(USF)=0,0
Exp/Cntr=0.3,0.1

Type RM Length L Ch R = 1 ,57789   ,303,303,303
XS GIS Cut Line= 3
2199373.60101095607971.1310853822199686.37258456608209.566814136
2199766.31868184608248.838581225
#Sta/Elev= 30
       0 2671.01       9 2665.88    23.3  2663.1    48.5 2646.59    73.7 2632.66
    94.6 2619.57   108.9 2613.22     139 2613.89   155.1 2618.27   179.3 2618.79
     186 2617.24   200.2 2609.03   208.8 2607.32   217.4 2607.49   239.6 2606.84
  249.922607.488   257.3 2612.57   265.9 2621.25   277.3 2631.25     295 2640.63
   322.9 2662.59   325.1 2663.61   335.2 2664.45   365.8 2678.55     380 2686.17
   395.3 2687.21   399.8 2688.37   409.3 2695.26   435.4 2705.89   482.4 2722.52
#Mann= 3 ,-1,0
       0      .1       0   217.4    .045       0  249.92      .1       0
Bank Sta=217.4,249.92
XS Rating Curve= 0 ,0
Exp/Cntr(USF)=0,0
Exp/Cntr=0.3,0.1

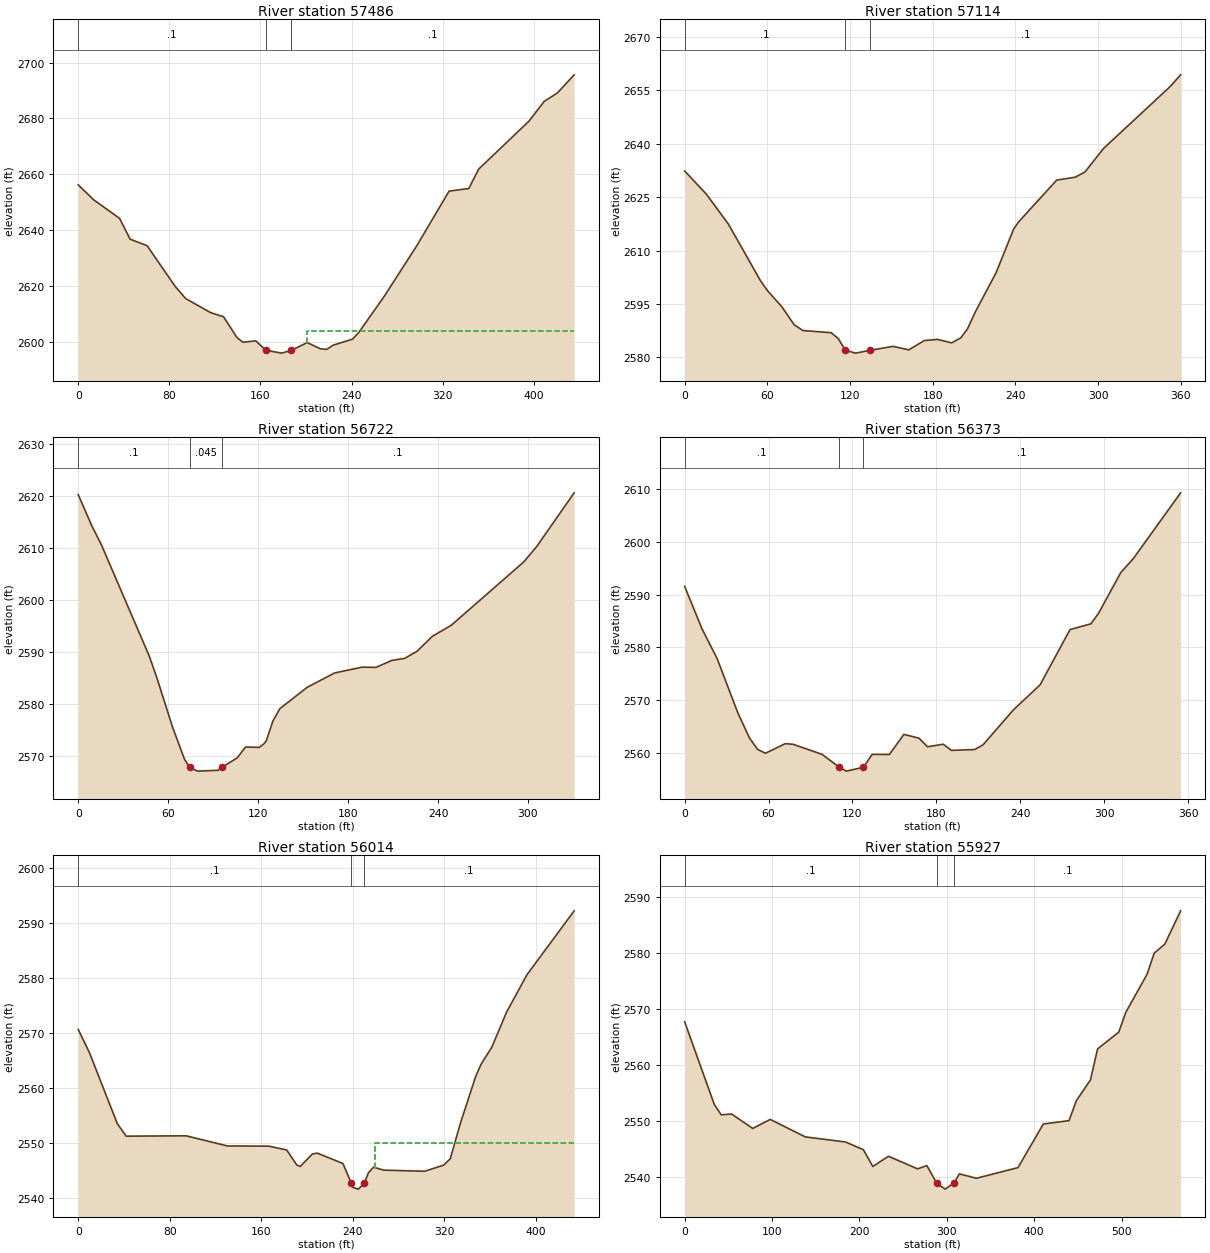
Type RM Length L Ch R = 1 ,57486   ,372.2,372.2,372.2
XS GIS Cut Line= 3
2199226.58993237608194.2503598582199467.35858264608437.073631466
  2199551.939349608476.753077395
#Sta/Elev= 30
       0 2656.19    13.6 2650.84    36.3  2644.2    45.6 2636.73    60.5 2634.41
    85.2 2619.79    94.3 2615.49   116.3 2610.43   127.6 2608.96   139.3 2601.56
   144.6 2599.83   155.9 2600.33  164.742596.967   178.6 2595.94     187 2596.93
   201.1 2599.72   212.4 2597.51   218.2 2597.28   223.8 2598.78   240.9 2600.96
   246.5 2603.44   268.9 2616.41   297.4 2634.49   325.6 2653.95   342.9 2654.88
   351.6 2661.84   395.9 2679.07   409.1 2686.08   420.8 2689.14   435.4 2695.59
#Mann= 3 ,-1,0
       0      .1       0  164.74    .045       0     187      .1       0
#XS Ineff= 2 , 0
                         200.595            2604
Permanent Ineff=
       F       F
Bank Sta=164.74,187
XS Rating Curve= 0 ,0
Exp/Cntr=0.3,0.1

Type RM Length L Ch R = 1 ,57114   ,392.2,392.2,392.2
XS GIS Cut Line= 3
2199069.40857475608515.3449541912199258.31875359608667.718735019
2199367.31699351608710.629122157
#Sta/Elev= 30
       0 2632.38    15.7 2625.89    31.7 2617.48    54.9 2601.62    60.3 2598.66
    70.4 2594.29    79.4  2589.2    85.8 2587.56   106.3 2586.95   111.4 2585.31
  116.632582.001     124 2581.21  134.492582.001   151.2 2583.11   162.6 2582.13
   173.9 2584.75   183.4 2585.07   193.7 2584.09   200.4 2585.52   205.2 2588.04
   210.9 2592.82   225.9 2603.78   238.7  2616.1   242.2 2618.05   269.9 2629.82
   283.4 2630.64   290.4  2632.1   303.9 2638.72   352.2  2656.1   359.8  2659.4
#Mann= 3 ,-1,0
       0      .1       0  116.63    .045       0  134.49      .1       0
Bank Sta=116.63,134.49
XS Rating Curve= 0 ,0
Exp/Cntr=0.3,0.1

Type RM Length L Ch R = 1 ,56722   ,348.5,348.5,348.5
XS GIS Cut Line= 2
2198878.58076587608866.5268560882199167.78608144 609027.09791068
#Sta/Elev= 30
       0 2620.24       9 2614.29    15.5 2610.58    47.3 2589.31    52.2 2585.32
    63.1 2575.47    70.8  2569.5   74.262567.865    79.6 2567.16    93.3 2567.32
    95.82567.863   106.1 2569.72   111.6 2571.79   120.8 2571.72   123.7 2572.36
   125.4 2572.96   129.9 2576.79   134.5 2579.15   152.8 2583.26   171.1 2586.01
   189.4 2587.12   198.6 2587.07   209.1  2588.4   217.9 2588.82     226 2590.16
   236.2 2593.03   248.9 2595.17   297.3 2607.35   305.9  2610.3   330.8 2620.58
#Mann= 3 ,-1,0
       0      .1       0   74.26    .045       0    95.8      .1       0
Bank Sta=74.26,95.8
XS Rating Curve= 0 ,0
Exp/Cntr=0.3,0.1

Type RM Length L Ch R = 1 ,56373   ,359,359,359
XS GIS Cut Line= 2
2198678.57910988609113.1060168532198934.40073043609358.805199186
#Sta/Elev= 30
       0 2591.58    12.5 2583.47    23.2  2577.9      38 2567.59    46.3 2562.84
    52.1 2560.66    57.8 2559.91    71.9 2561.73    77.6 2561.61    98.3  2559.7
  110.632557.245   115.6 2556.52   127.82557.245   134.1  2559.7   146.4 2559.68
   156.8  2563.5   167.6 2562.77   173.7 2561.14   184.9 2561.63   190.8 2560.46
   207.4 2560.62   213.4 2561.51   235.1 2568.15   254.2  2572.9   275.6 2583.39
   290.6 2584.49   296.2 2586.57   311.9 2594.21   320.9 2596.87   354.7 2609.35
#Mann= 3 ,-1,0
       0      .1       0  110.63    .045       0   127.8      .1       0
Bank Sta=110.63,127.8
XS Rating Curve= 0 ,0
Exp/Cntr(USF)=0,0
Exp/Cntr=0.3,0.1

Type RM Length L Ch R = 1 ,56014   ,86.9,86.9,86.9
XS GIS Cut Line= 3
2198508.32027495609279.5088344762198526.49749286609454.464556857
2198757.12094509609569.208244913
#Sta/Elev= 30
       0 2570.64     9.7 2566.46    34.2 2553.46    41.9 2551.18    94.2 2551.25
   130.4  2549.4   166.6 2549.36   182.2 2548.67   191.1 2545.92   194.1 2545.67
   204.6 2547.92     209 2548.09   231.4  2546.2  238.792542.576   240.3 2541.83
   244.8 2541.53  250.032542.576   253.7 2544.52   258.2 2545.53   267.1 2544.99
   302.9 2544.79   319.4  2545.9   325.2 2547.06   334.1 2553.55   347.5 2562.11
   352.2  2564.3   361.6 2567.43   374.4 2573.77   392.2 2580.58   433.5 2592.25
#Mann= 3 ,-1,0
       0      .1       0  238.79    .045       0  250.03      .1       0
#XS Ineff= 1 ,-1
 259.685433.4888    2550
Permanent Ineff=
       F
Bank Sta=238.79,250.03
XS Rating Curve= 0 ,0
Exp/Cntr(USF)=0,0
Exp/Cntr=0.3,0.1

Type RM Length L Ch R = 1 ,55927   ,58.6,58.6,58.6
XS GIS Cut Line= 6
2198480.35412404609287.4865256842198491.98773332609465.123790571
2198537.52693642609541.6957740432198585.60667781609598.062886377
2198604.01845525609694.5092956642198730.07726031609674.302643862
#Sta/Elev= 30
       0 2567.71    33.8    2553    41.8 2551.11    53.8 2551.25    77.9 2548.68
    97.9 2550.29     138 2547.17     184 2546.26   204.5 2544.88   215.3 2541.88
   233.2 2543.71   266.5 2541.46   277.1 2542.05   288.5  2538.9     298 2537.84
   308.3 2538.94   314.3 2540.56   333.9 2539.78   381.4 2541.68   410.4 2549.47
   439.8 2550.07   448.2 2553.63   464.3 2557.33   472.5 2562.88   496.7 2565.87
   504.8 2569.42   529.1  2576.2   537.2 2579.97   549.4 2581.59   567.5 2587.54
#Mann= 3 ,0,0
       0      .1       0   288.5    .045       0   308.3      .1       0
Bank Sta=288.5,308.3
XS Rating Curve= 0 ,0
Exp/Cntr=0.3,0.1

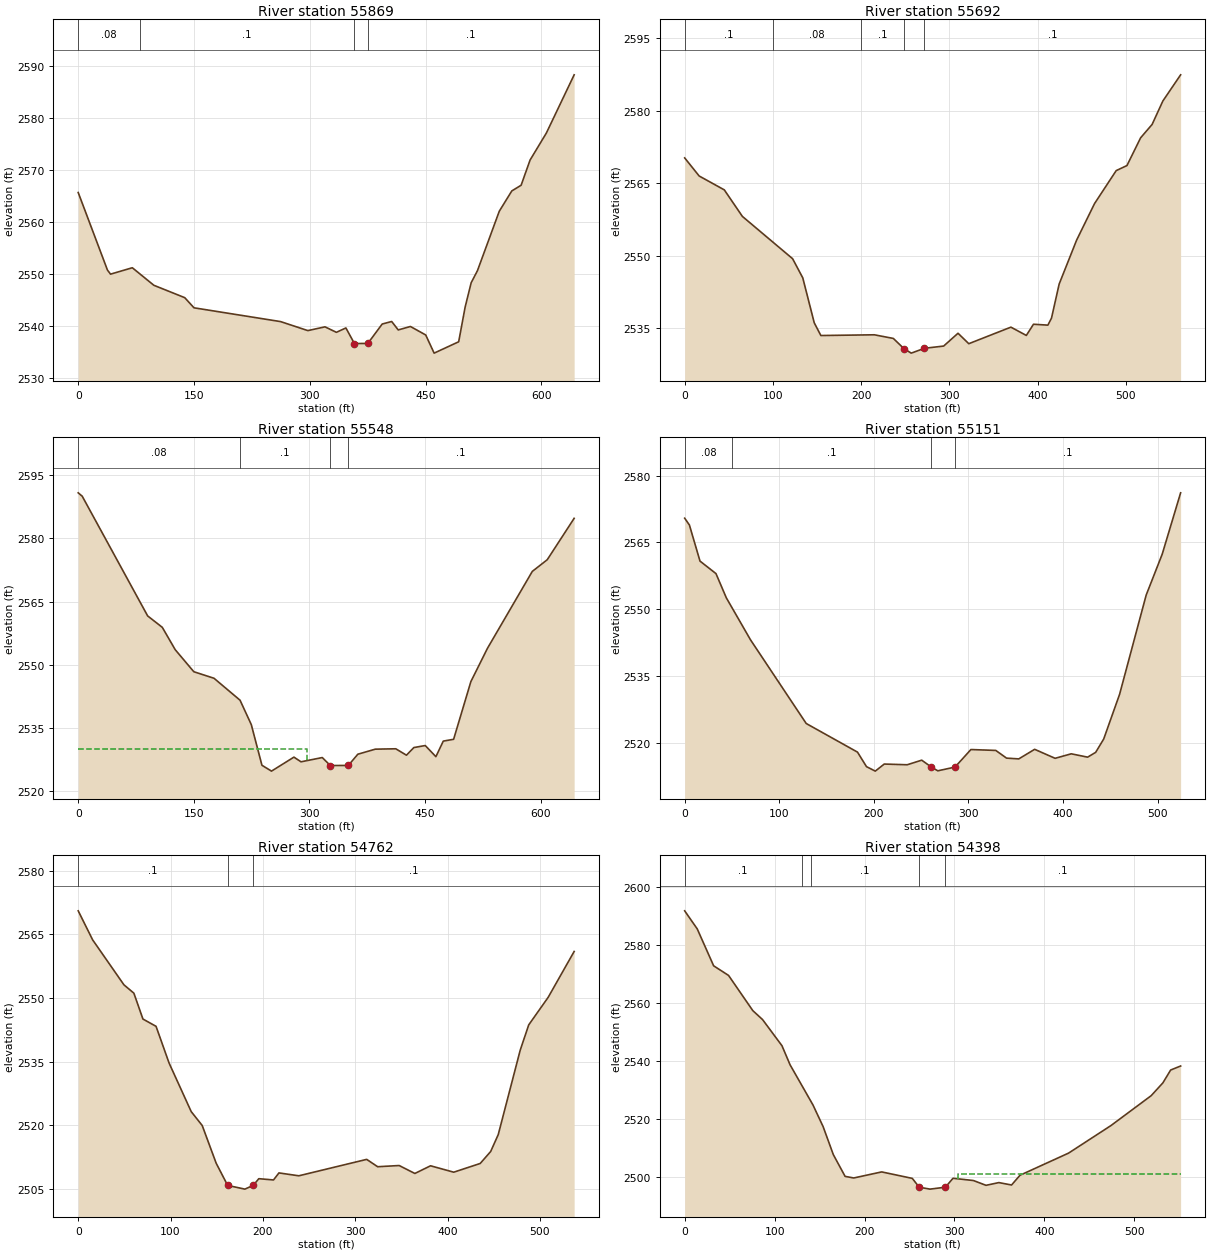
Type RM Length L Ch R = 1 ,55869   ,176.4,176.4,176.4
XS GIS Cut Line= 6
 2198455.8967676609287.3763313342198444.70373033609486.318466339
2198490.24293343609562.8904498112198538.32267482609619.257562145
2198556.73445226609715.7039714322198736.05543261609687.888437445
#Sta/Elev= 30
       0 2565.71    37.9  2550.8    41.9 2550.02    70.1 2551.25      98 2547.88
     138  2545.5     150 2543.55   262.2  2540.9   297.5 2539.17   319.7 2539.89
   334.5 2538.84   346.8 2539.68  357.82 2536.69   375.2  2536.7   393.8 2540.43
   406.1 2540.92   414.6  2539.3   430.4 2539.96   450.2 2538.33   461.1 2534.84
   492.9 2537.02   501.3 2543.71   509.1 2548.37   517.2 2550.68   545.5 2562.11
   561.7 2566.01   573.8 2567.11   585.4 2571.95   606.5 2577.14   642.5 2588.33
#Mann= 4 ,-1,0
       0     .08       0      80      .1       0  357.82    .045       0
   375.2      .1       0
Bank Sta=357.82,375.2
XS Rating Curve= 0 ,0
Exp/Cntr=0.3,0.1

Type RM Length L Ch R = 1 ,55692   ,144.5,144.5,144.5
XS GIS Cut Line= 2
2198184.03084997609801.6050267842198735.86358685609695.893248026
#Sta/Elev= 30
       0 2570.24    16.4  2566.5    44.9 2563.63    65.4 2558.14   122.3 2549.39
   133.8 2545.44   146.8 2536.14   154.3 2533.51   214.9 2533.66   236.4 2532.91
   248.6 2530.77   256.7 2529.87   271.7 2530.87   293.4 2531.33   309.7 2533.98
   321.9 2531.82   369.6 2535.24   387.1 2533.53   395.2 2535.84   411.5 2535.66
   415.6  2537.1   424.3 2544.16   444.1 2553.25   464.4  2560.8   488.9 2567.61
   501.1 2568.66   516.6  2574.4   529.6 2577.16   541.8 2582.01   561.9 2587.42
#Mann= 5 ,-1,0
       0      .1       0     100     .08       0     200      .1       0
   248.6    .045       0   271.7      .1       0
Bank Sta=248.6,271.7
XS Rating Curve= 0 ,0
Exp/Cntr(USF)=0,0
Exp/Cntr=0.3,0.1

Type RM Length L Ch R = 1 ,55548   ,397.1,397.1,397.1
XS GIS Cut Line= 4
2198258.06263147610113.3194466552198389.50388047609940.765138601
2198629.58581591609803.7296600362198768.47827125609746.596883544
#Sta/Elev= 30
       0 2590.79     5.2 2589.99    90.1 2561.59   109.1 2558.88   125.9 2553.57
     150 2548.35   176.2  2546.8     210 2541.59   224.6  2535.8   238.4 2526.16
   250.8 2524.77   279.9 2528.09   289.1 2526.98   316.7 2527.99   327.1  2526.1
   350.5 2526.12   362.8 2528.78   385.5 2529.98   412.1 2530.07   425.9 2528.55
   435.5 2530.36   450.3 2530.84   464.1  2528.2   473.7 2531.89   487.1 2532.32
   509.5 2546.01     531  2553.9   589.2 2572.15   608.6 2574.92   643.5 2584.74
#Mann= 4 ,-1,0
       0     .08       0     210      .1       0   327.1    .045       0
   350.5      .1       0
#XS Ineff= 2 , 0
        297.2142    2530
Permanent Ineff=
       F       F
Bank Sta=327.1,350.5
XS Rating Curve= 0 ,0
Exp/Cntr=0.3,0.1

Type RM Length L Ch R = 1 ,55151   ,388.6,388.6,388.6
XS GIS Cut Line= 2
2198540.61530163610304.0502036162198914.09943616609936.056436527
#Sta/Elev= 30
       0 2570.44       5 2568.91    16.2  2560.8    33.1 2557.99      44 2552.56
    69.6 2543.11   128.5 2524.31   182.7 2517.88   192.2 2514.62   201.5 2513.61
     211  2515.2   235.2 2515.04   250.6 2516.07   260.6 2514.55   267.6 2513.68
   285.8 2514.52   302.6 2518.46   328.9 2518.26   340.3 2516.53   353.2 2516.36
     370 2518.51   391.6 2516.49   408.7  2517.5     426 2516.75   434.5 2517.83
     443 2520.83   459.8 2530.88   487.9 2553.17   504.8 2562.33   524.3 2576.14
#Mann= 4 ,-1,0
       0     .08       0      50      .1       0   260.6    .045       0
   285.8      .1       0
Bank Sta=260.6,285.8
XS Rating Curve= 0 ,0
Exp/Cntr=0.3,0.1

Type RM Length L Ch R = 1 ,54762   ,364.2,364.2,364.2
XS GIS Cut Line= 2
2198675.62675498610539.659586707 2199072.5521152610177.798304245
#Sta/Elev= 30
       0 2570.51    15.6 2563.68    49.5 2553.08    60.3  2551.1    70.1 2545.01
    84.3 2543.29    98.4 2534.65   122.4 2523.19   134.3 2519.92   149.4 2511.04
  161.852505.805   180.5 2504.93  189.522505.806   195.6 2507.39   211.5 2507.09
   217.4 2508.75   238.9 2508.07   312.4 2511.94   324.3 2510.21   347.6 2510.49
   364.6 2508.62   381.6 2510.43   406.7 2508.92   435.4 2510.98   446.7  2513.8
   454.9 2517.78   478.7 2537.68   487.9 2543.63     509 2550.14   537.1 2560.93
#Mann= 3 ,-1,0
       0      .1       0  161.85    .045       0  189.52      .1       0
Bank Sta=161.85,189.52
XS Rating Curve= 0 ,0
Exp/Cntr(USF)=0,0
Exp/Cntr=0.3,0.1

Type RM Length L Ch R = 1 ,54398   ,391.9,391.9,391.9
XS GIS Cut Line= 2
2198876.05427233 610834.58010669     2199284.446610463.891243402
#Sta/Elev= 30
       0 2591.74      14  2585.5    32.2 2572.81    48.8 2569.49    75.8 2557.36
    86.6 2554.29   108.2 2545.28   117.2 2538.72   142.7 2524.87     154 2517.39
   165.3 2507.78   178.4 2500.29     188 2499.74   219.1 2501.83   253.1  2499.6
  260.822496.561   272.9  2495.9  289.932496.561   298.4 2499.64   321.1 2498.86
   335.1 2497.21   349.4 2498.15   363.5 2497.32   372.9 2500.68   426.9  2508.3
     474 2517.78   518.8 2528.09   531.8  2532.5   540.4 2536.91   551.5  2538.3
#Mann= 5 ,-1,0
       0      .1       0     130     .05       0     140      .1       0
  260.82    .045       0  289.93      .1       0
#XS Ineff= 2 , 0
                        304.4914            2501
Permanent Ineff=
       F       F
Bank Sta=260.82,289.93
XS Rating Curve= 0 ,0
Exp/Cntr=0.3,0.1

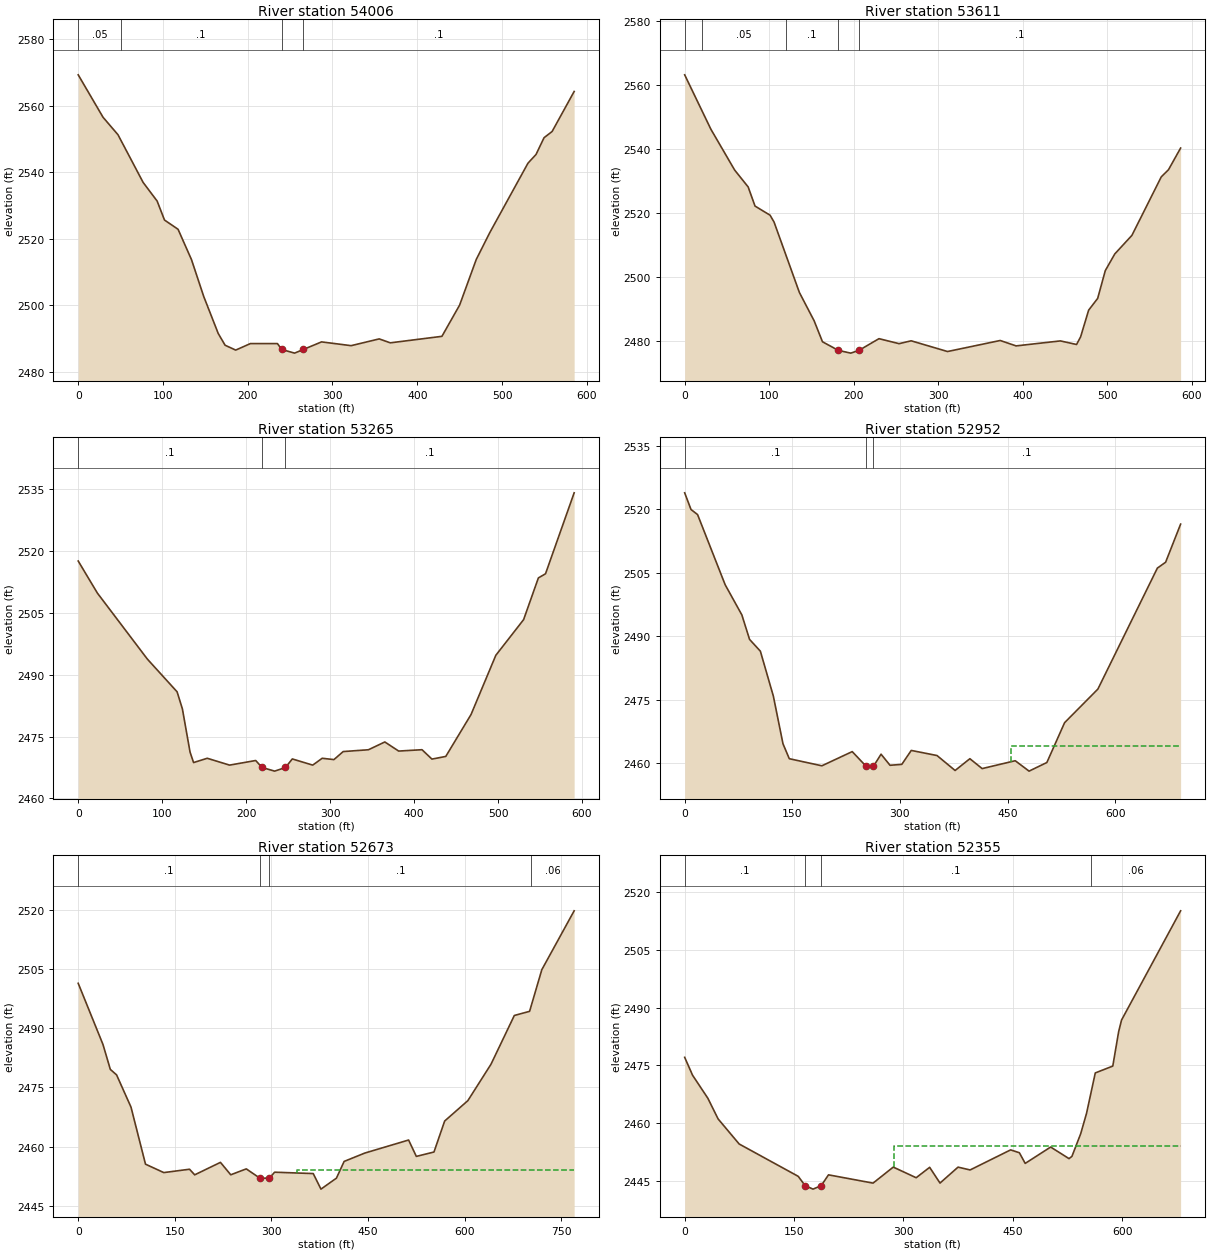
Type RM Length L Ch R = 1 ,54006   ,394.8,394.8,394.8
XS GIS Cut Line= 2
2199100.88490344611062.4107280292199594.10793273610747.591572513
#Sta/Elev= 30
       0 2569.23    29.3 2556.49    46.9 2551.26    76.6 2536.93    93.1 2531.35
   101.8 2525.65   117.8 2522.87   133.6 2513.79   148.1 2502.69   165.2 2491.59
   173.3 2488.07   185.8 2486.61   203.2 2488.57     235 2488.57   240.2 2486.79
   255.3  2485.7  265.612486.798   287.1 2489.07     322 2487.94   355.1 2489.97
   368.2 2488.79   429.1 2490.74     450 2500.13   469.6 2513.81   485.5 2521.84
   530.6  2542.7   540.1 2545.32   549.6 2550.36   559.1 2552.22   585.1 2564.23
#Mann= 4 ,-1,0
       0     .05       0      50      .1       0   240.2    .045       0
  265.61      .1       0
Bank Sta=240.2,265.61
XS Rating Curve= 0 ,0
Exp/Cntr=0.3,0.1

Type RM Length L Ch R = 1 ,53611   ,346.4,346.4,346.4
XS GIS Cut Line= 3
2199245.22198011611349.5380097652199334.83141683 611343.32824892
2199751.39266059611072.633568628
#Sta/Elev= 30
       0 2563.07      31 2546.06    59.1  2533.3    75.1 2528.01    83.2 2522.04
     101 2519.18   105.7 2517.05   135.7 2495.01   153.1 2486.18     163 2479.61
  181.752476.916   196.4 2476.06  206.09 2476.91   229.8 2480.58   253.6 2479.02
   267.9 2479.91   310.9 2476.56   373.2 2480.01     392 2478.32   444.4 2479.88
   463.5 2478.76   468.3 2481.14   477.8 2489.49   488.5 2493.17   497.5 2501.85
   508.7 2507.06     529 2512.88   563.7 2531.16   572.3 2533.42   586.6 2540.18
#Mann= 5 ,-1,0
       0      .1       0      20     .05       0  119.82      .1       0
  181.75    .045       0  206.09      .1       0
Bank Sta=181.75,206.09
XS Rating Curve= 0 ,0
Exp/Cntr=0.3,0.1

Type RM Length L Ch R = 1 ,53265   ,312.8,312.8,312.8
XS GIS Cut Line= 3
2199434.65183339611630.0682511932199575.52527219611580.080901942
2199895.89873785611276.748578073
#Sta/Elev= 30
       0 2517.61    22.8 2509.84    82.3 2493.82   117.8 2485.85   124.1  2481.7
   133.2 2471.23   137.4 2468.68   153.7 2469.72   180.3 2468.06   211.4 2469.18
  218.972467.482     234  2466.6  246.872467.483     255 2469.56   279.3 2468.06
   290.6 2469.72   304.6  2469.4   315.6 2471.35   345.7 2471.79   365.2 2473.68
   381.7 2471.47   409.5  2471.8   421.3 2469.52   437.8 2470.17   467.9 2480.35
   497.4 2494.72   530.5 2503.38   548.1 2513.51   556.6 2514.52   590.7 2534.17
#Mann= 3 ,-1,0
       0      .1       0  218.97    .045       0  246.87      .1       0
Bank Sta=218.97,246.87
XS Rating Curve= 0 ,0
Exp/Cntr(USF)=0,0
Exp/Cntr=0.3,0.1

Type RM Length L Ch R = 1 ,52952   ,278.6,278.6,278.6
XS GIS Cut Line= 4
2199519.83286417611872.8807925392199651.64237219611811.840430291
2200026.01573581611717.0509686552200120.51455373611588.188199994
#Sta/Elev= 30
       0 2523.94     8.8    2520      18 2518.78    56.4 2502.19    79.7 2495.04
    90.4 2489.25   105.5 2486.45   123.6 2475.81     137 2464.54   145.8    2461
   191.2 2459.32   233.5 2462.68   252.8 2459.22   263.1  2459.2   273.7 2462.07
   286.2 2459.44   302.6 2459.66   315.8 2462.96   351.7 2461.75   376.9 2458.21
   397.5    2461   414.6 2458.66   460.7 2460.52     480 2458.06   504.8  2460.1
   529.5 2469.53   575.9 2477.48   658.8 2506.12   670.3 2507.51   691.2 2516.53
#Mann= 3 ,-1,0
       0      .1       0   252.8    .045       0   263.1      .1       0
#XS Ineff= 2 , 0
                        455.4829            2464
Permanent Ineff=
       F       F
Bank Sta=252.8,263.1
XS Rating Curve= 0 ,0
Exp/Cntr=0.3,0.1

Type RM Length L Ch R = 1 ,52673   ,318.5,318.5,318.5
XS GIS Cut Line= 4
2199654.99908208612043.7452358262199751.61707069611994.748685507
2200316.73747909611978.1736164222200408.49690298612008.220585077
#Sta/Elev= 30
       0 2501.35    38.5 2485.84    49.9 2479.53    59.6 2478.15      82 2469.98
   104.5 2455.53   132.9  2453.4   172.9 2454.25   180.9 2452.83   220.9 2455.99
   236.9 2452.84     261 2454.34  282.232451.983   296.9 2451.99     305  2453.5
     365 2453.15     377 2449.21     401 2451.99     413 2456.23     445 2458.34
   513.1 2461.65   525.1  2457.5   552.5 2458.61   569.1 2466.46   605.1 2471.62
   641.1 2480.86   677.3  2493.2     701 2494.25     720  2504.8   770.2 2519.71
#Mann= 4 ,-1,0
       0      .1       0  282.23    .045       0   296.9      .1       0
  703.69     .06       0
#XS Ineff= 2 , 0
                        340.5182            2454
Permanent Ineff=
       F       F
Bank Sta=282.23,296.9
XS Rating Curve= 0 ,0
Exp/Cntr=0.3,0.1

Type RM Length L Ch R = 1 ,52355   ,275.4,275.4,275.4
XS GIS Cut Line= 4
2199774.33859308612319.6664556442199935.66140203612294.672781018
2200140.15510351612098.1316123692200373.05070798612089.043003414
#Sta/Elev= 30
       0 2477.09    10.8 2472.45    31.8 2466.46    45.8 2461.11    74.7 2454.59
   155.7 2446.19  165.15 2443.77     176 2442.87   187.22443.771   197.2 2446.58
   258.3 2444.43     286 2448.59   317.4 2445.83   335.9 2448.53   350.1 2444.44
   374.8 2448.58   391.4 2447.85   446.9 2453.06   458.9 2452.32   466.9 2449.55
   501.8  2453.8     527 2450.79     531 2451.38     543 2457.26     551 2462.54
     563 2473.04     587 2474.82     595 2483.72     599 2486.77     680 2515.13
#Mann= 4 ,-1,0
       0      .1       0  165.15    .045       0   187.2      .1       0
  556.88     .06       0
#XS Ineff= 1 ,-1
 287.057679.9506    2454
Permanent Ineff=
       F
Bank Sta=165.15,187.2
XS Rating Curve= 0 ,0
Exp/Cntr(USF)=0,0
Exp/Cntr=0.3,0.1

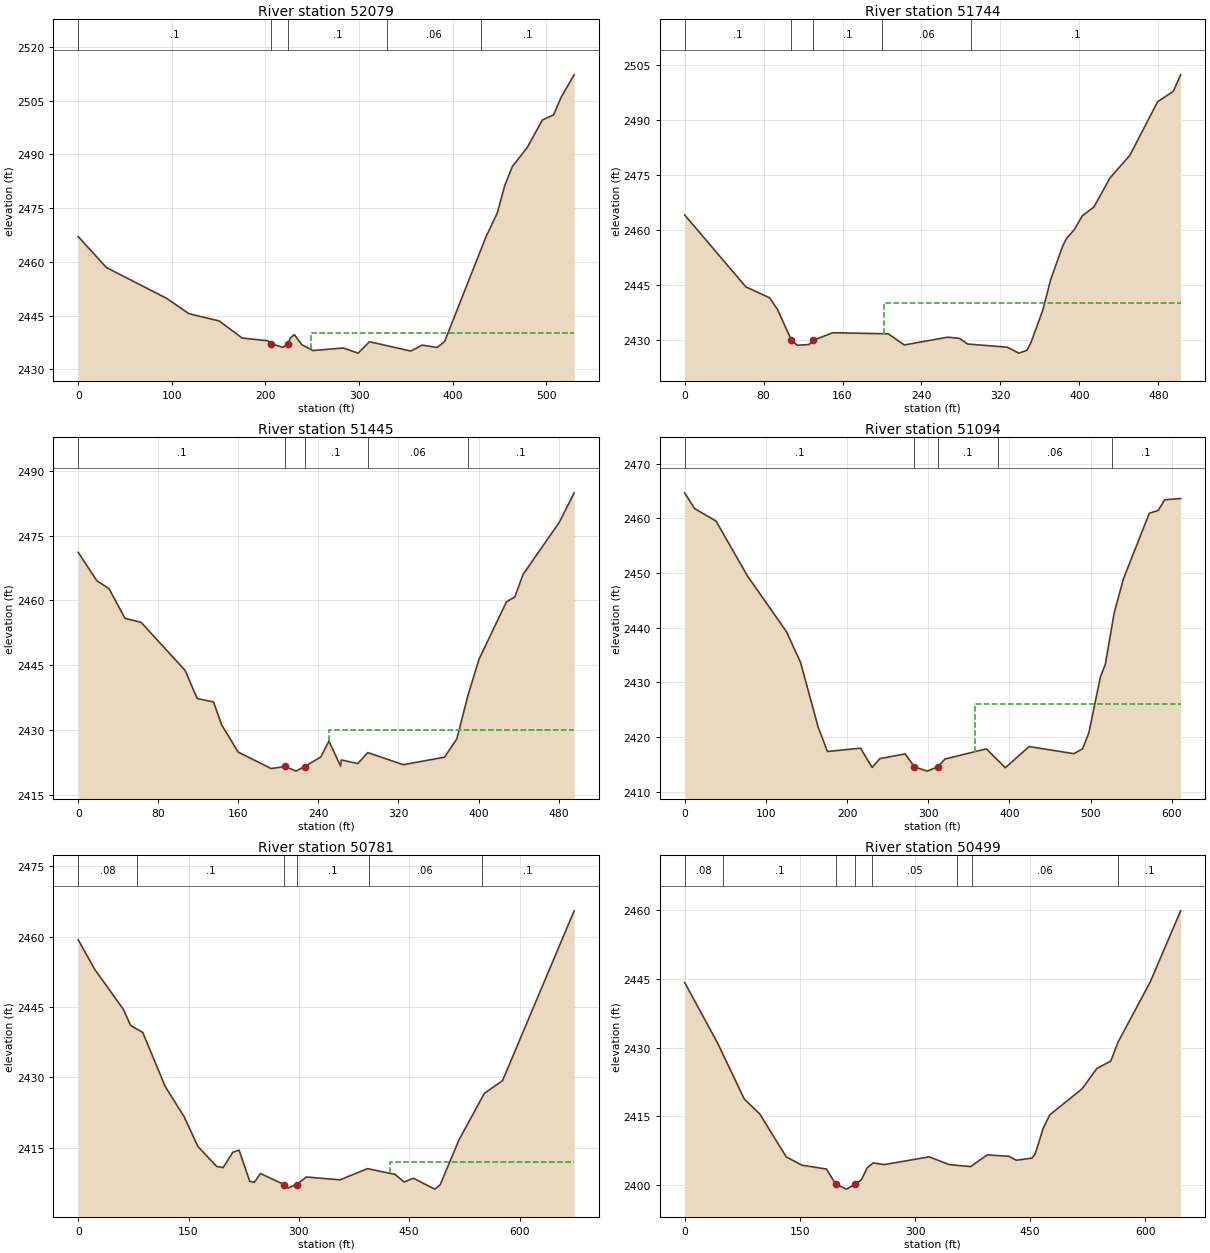
Type RM Length L Ch R = 1 ,52079   ,335.6,335.6,335.6
XS GIS Cut Line= 2
2199818.18156153612557.1119440592200346.05477306612510.651877017
#Sta/Elev= 30
       0 2467.04    30.1 2458.39    94.4  2449.8   118.4  2445.5   150.6 2443.49
   175.2 2438.71   202.8 2437.94  206.17 2437.14   218.8 2436.11  224.08 2437.14
   226.9 2438.79   230.9 2439.67   238.9 2436.84     251 2435.22   283.1 2435.94
   299.1  2434.5   311.2 2437.68   355.4 2435.08   367.4 2436.74   383.5 2436.08
   391.5 2437.73   435.7 2466.97   447.7 2473.54   455.7 2481.25   463.8 2486.55
   479.8  2491.9   495.9 2499.57   507.9 2500.98     516 2505.93   529.9 2512.18
#Mann= 5 ,-1,0
       0      .1       0  206.17    .045       0  224.08      .1       0
     330     .06       0     430      .1       0
#XS Ineff= 2 , 0
                        248.5047            2440
Permanent Ineff=
       F       F
Bank Sta=206.17,224.08
XS Rating Curve= 0 ,0
Exp/Cntr=0.3,0.1

Type RM Length L Ch R = 1 ,51744   ,298.6,298.6,298.6
XS GIS Cut Line= 2
2199858.40822591612861.5747645772200359.41779455  612821.8121004
#Sta/Elev= 30
       0  2464.1      62  2444.5      86 2441.52    94.1 2438.34  108.24 2429.94
   114.1 2428.57   126.2 2428.78   130.2 2429.93   150.2    2432   206.4 2431.69
   222.5 2428.66   266.6 2430.78   278.6 2430.45   286.7 2428.91   326.8 2428.05
   338.8 2426.43   346.9  2427.2   350.9 2429.28   362.9 2438.13   370.9 2446.46
     383 2455.57     387 2457.72     395 2460.14     403  2463.9   414.7 2466.25
   431.1 2474.22   451.2 2480.38   479.3 2494.98   495.3 2497.85   502.6 2502.31
#Mann= 5 ,-1,0
       0      .1       0  108.24    .045       0   130.2      .1       0
     200     .06       0     290      .1       0
#XS Ineff= 1 ,-1
  201.84 502.585    2440
Permanent Ineff=
       F
Bank Sta=108.24,130.2
XS Rating Curve= 0 ,0
Exp/Cntr(USF)=0,0
Exp/Cntr=0.3,0.1

Type RM Length L Ch R = 1 ,51445   ,351,351,351
XS GIS Cut Line= 3
2199865.46600644613123.5749834752199993.94113929613129.952055108
2200349.69003929613040.492871524
#Sta/Elev= 30
       0 2471.14    18.7 2464.53    30.7 2462.75    46.8 2455.85    62.8 2454.94
   106.8 2443.81   118.9 2437.29   135.1 2436.52   143.3 2431.21   159.8  2424.9
   192.8 2421.08   206.9 2421.57   217.6 2420.49  226.23 2421.56   242.3 2423.75
   250.5 2427.43  262.14 2421.66   262.9 2423.07   279.4 2422.25   289.3 2424.78
   324.8 2421.98     366 2423.72   378.3 2427.97   389.6 2438.18   400.6 2446.48
   427.9 2459.69   436.2 2460.79   444.4 2466.01   480.5 2478.02   495.5 2484.91
#Mann= 5 ,-1,0
       0      .1       0   206.9    .045       0  226.23      .1       0
   289.3     .06       0   389.6      .1       0
#XS Ineff= 2 , 0
                           250.5            2430
Permanent Ineff=
       F       F
Bank Sta=206.9,226.23
XS Rating Curve= 0 ,0
Exp/Cntr=0.3,0.1

Type RM Length L Ch R = 1 ,51094   ,313.1,313.1,313.1
XS GIS Cut Line= 3
2199944.99535949613596.4063880642200106.65591013613526.978786295
2200403.50948499613208.966582641
#Sta/Elev= 30
       0 2464.68    12.2  2461.8    38.6 2459.52    77.5 2449.44   125.4 2439.29
   142.8 2433.64   164.5  2421.8   175.9 2417.36   216.7 2417.97   230.9 2414.44
   240.5 2416.06   271.7 2416.92     283 2414.55   298.8 2413.77  311.642414.552
   320.7 2415.98   371.6 2417.85   395.1  2414.4   424.4 2418.27   479.4 2416.96
   490.3 2417.87   498.1 2420.85   512.2 2431.03   518.2 2433.29   529.2 2442.75
   540.5 2448.92   572.4 2460.94   583.3 2461.46   591.5 2463.42     611 2463.63
#Mann= 5 ,-1,0
       0      .1       0     283    .045       0  311.64      .1       0
  385.94     .06       0  525.94      .1       0
#XS Ineff= 2 , 0
                        357.6812            2426
Permanent Ineff=
       F       F
Bank Sta=283,311.64
XS Rating Curve= 0 ,0
Exp/Cntr=0.3,0.1

Type RM Length L Ch R = 1 ,50781   ,282.4,282.4,282.4
XS GIS Cut Line= 4
2200080.00721103613799.0760296972200276.36604648613712.117116857
2200540.04791122613637.7812720112200669.08371737 613504.53777653
#Sta/Elev= 30
       0 2459.36    22.1 2453.13    61.4 2444.51    71.3 2441.08    87.7 2439.59
   118.3 2428.06   144.1 2421.59   162.7 2415.27   188.3    2411     197 2410.76
   210.2 2414.03   218.7 2414.49   233.2 2407.83   239.5 2407.62   247.8  2409.5
   279.7 2407.15   285.2 2406.41  297.08 2407.15   310.1 2408.76   355.9 2408.15
   393.3 2410.54   430.7 2409.32   443.1 2407.69   455.6  2408.5   484.7 2406.17
   492.1  2407.1   517.6 2416.66   552.1 2426.59   576.9 2429.32   674.2 2465.53
#Mann= 6 ,-1,0
       0     .08       0      80      .1       0   279.7    .045       0
  297.08      .1       0  394.75     .06       0  548.71      .1       0
#XS Ineff= 1 ,-1
   424.2 674.196    2412
Permanent Ineff=
       F
Bank Sta=279.7,297.08
XS Rating Curve= 0 ,0
Exp/Cntr(USF)=0,0
Exp/Cntr=0.3,0.1

Type RM Length L Ch R = 1 ,50499   ,371.2,371.2,371.2
XS GIS Cut Line= 3
  2200308.620583 614054.05561121 2200418.2073302613976.418922605
2200684.72664051613539.664359132
#Sta/Elev= 30
       0 2444.24      43 2430.96    77.6 2418.78    97.9 2415.48   132.3 2406.12
   152.6 2404.31   184.7 2403.46  196.782400.131   210.8 2399.07  222.13 2400.13
   230.2 2401.13   237.9 2403.78   245.6  2404.8   259.9 2404.43   318.5 2406.13
   344.7 2404.43   372.4    2404   394.2 2406.55   422.2 2406.25     432 2405.38
   452.4 2405.86   456.7 2406.81   466.9 2412.32   475.5  2415.3   517.7 2421.01
   536.8 2425.42   555.1 2427.07   564.5  2431.2   606.5 2444.39     646 2459.91
#Mann= 8 ,-1,0
       0     .08       0      50      .1       0  196.78    .045       0
  222.13      .1       0   244.3     .05       0   354.3      .1       0
   374.3     .06       0   564.3      .1       0
Bank Sta=196.78,222.13
XS Rating Curve= 0 ,0
Exp/Cntr=0.3,0.1