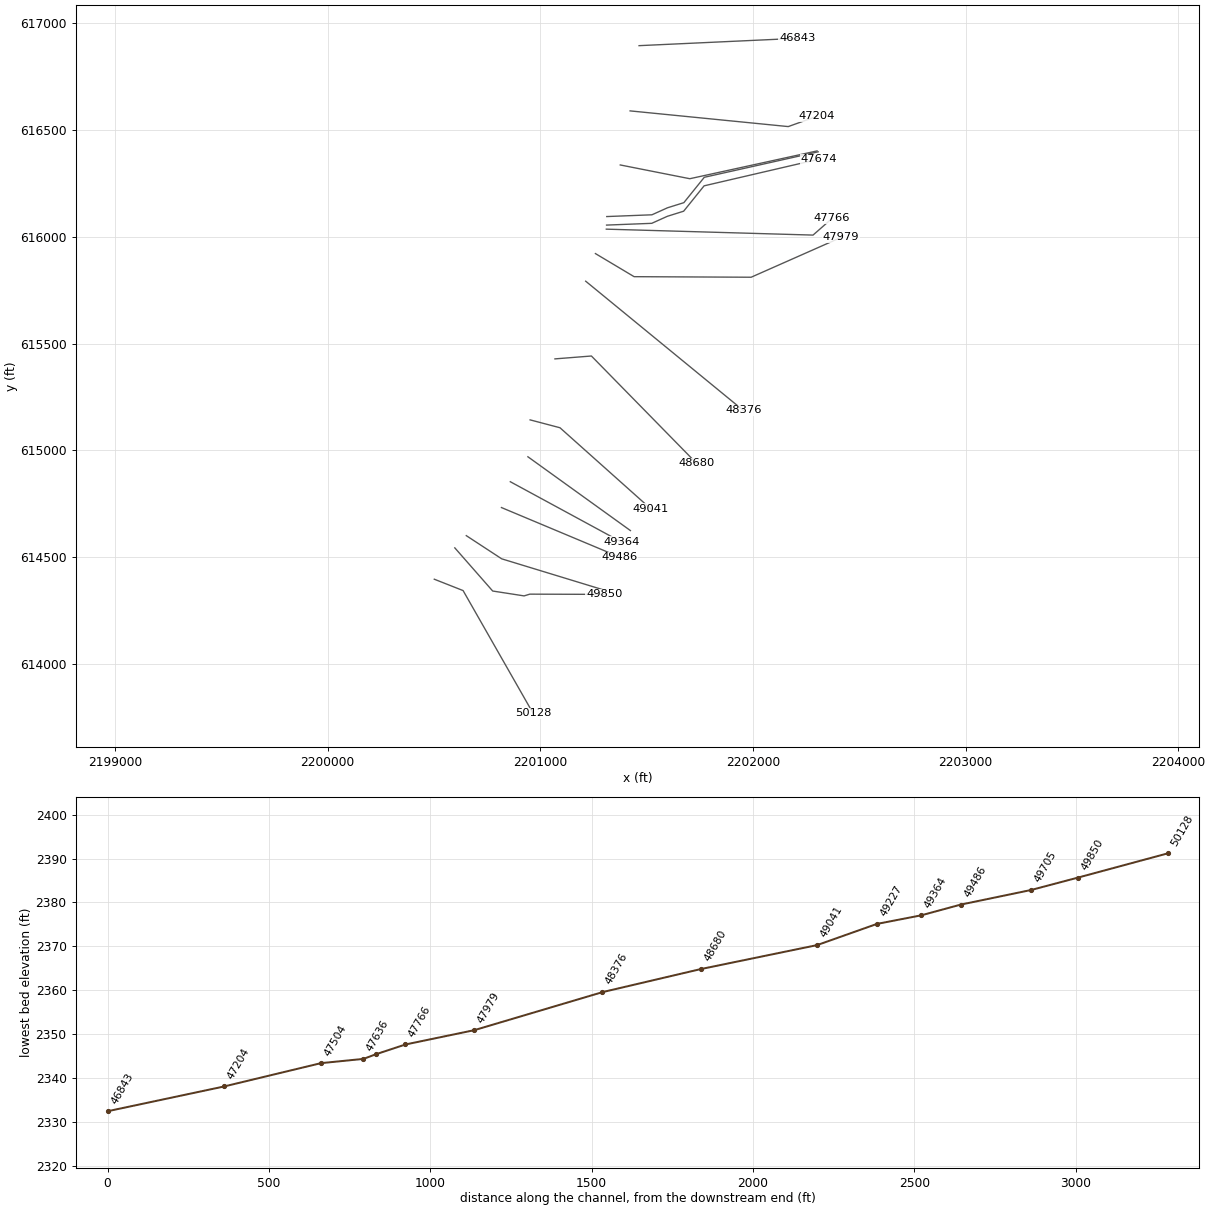
HEC-RAS study LFRFBUCRV.prj: LFRFBUCRV

--- LFRFBUCRV.g01 (geometry) --- (continued)

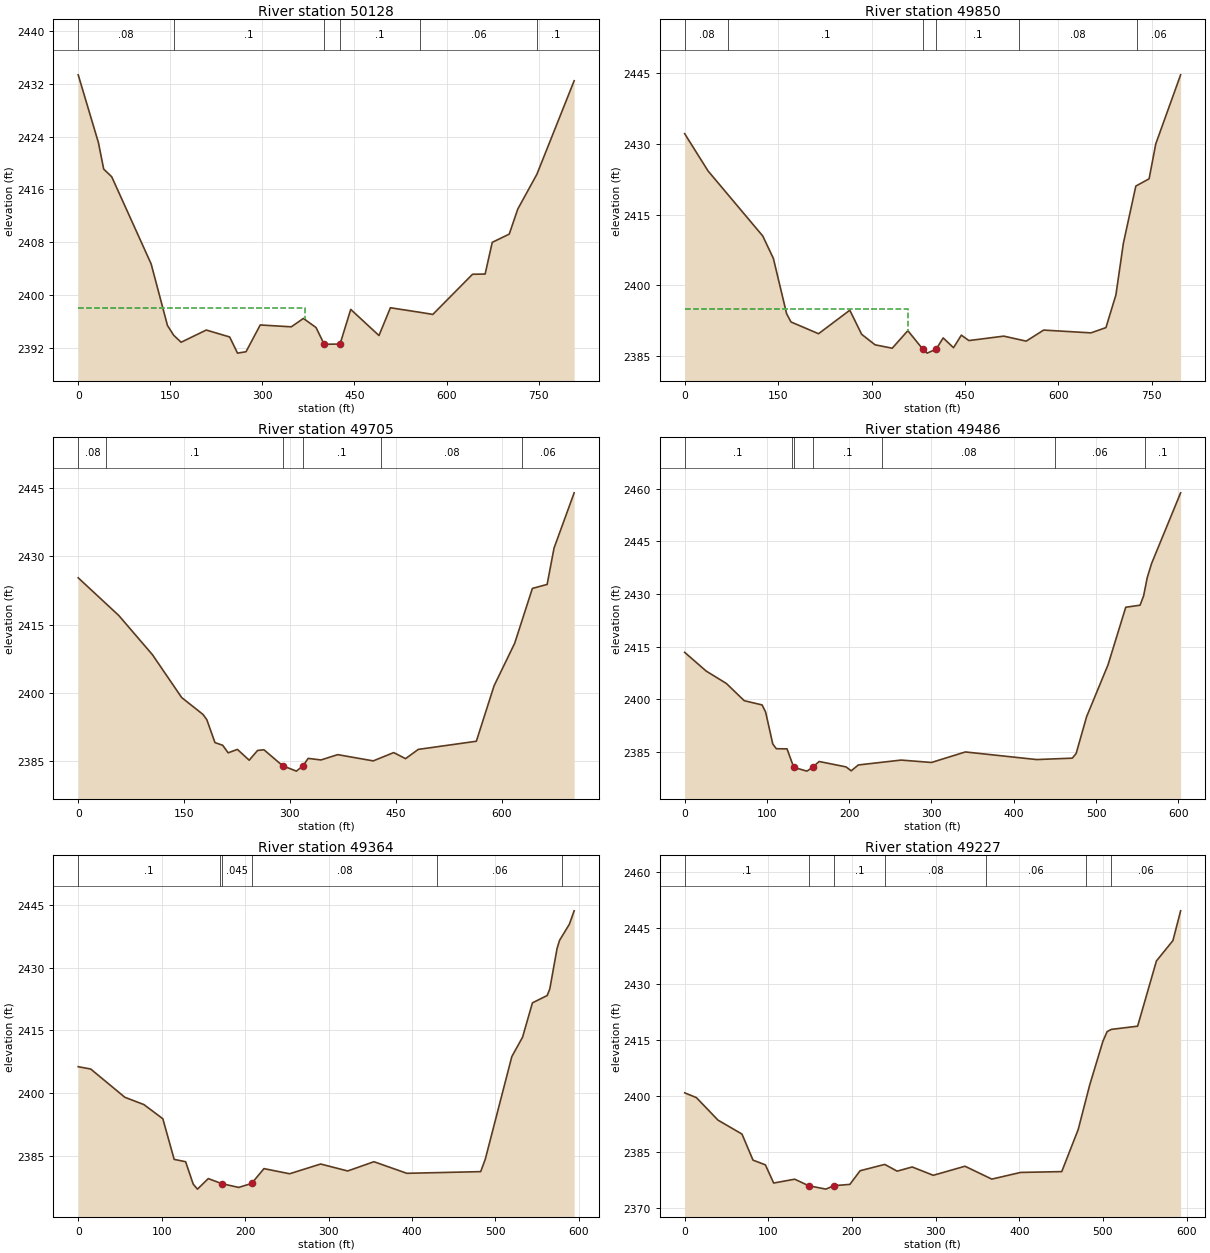
Type RM Length L Ch R = 1 ,50128   ,277.8,277.8,277.8
XS GIS Cut Line= 3
2200501.59263515 614397.323409622200636.95511609 614344.15254228
2200966.28152405613769.471147595
#Sta/Elev= 30
       0 2433.37    32.9  2423.1    41.5 2419.08    54.6 2417.91   118.8  2404.7
   145.4 2395.36   155.6 2393.87   167.6 2392.82   208.6 2394.67   246.7 2393.62
   259.5 2391.17   273.3 2391.38   296.5 2395.44   347.1 2395.16   366.8 2396.43
   387.4 2395.05  400.68 2392.51  426.482392.548   443.9  2397.8   489.9 2393.84
   508.5 2398.05   557.3 2397.35   577.6 2397.04   642.3 2403.13   662.8 2403.16
   674.4 2407.97   702.1 2409.22   715.9    2413   747.2 2418.31   807.8 2432.47
#Mann= 6 ,-1,0
       0     .08       0   155.6      .1       0  400.68    .045       0
  426.48      .1       0   557.3     .06       0   747.2      .1       0
#XS Ineff= 2 , 0
           369.1    2398
Permanent Ineff=
       F       F
Bank Sta=400.68,426.48
XS Rating Curve= 0 ,0
Exp/Cntr=0.3,0.1

Type RM Length L Ch R = 1 ,49850   ,144.6,144.6,144.6
XS GIS Cut Line= 5
2200598.05760272614543.9888129132200776.11886258614342.041286478
2200923.77941955  614319.24075932200950.58614947614327.420331439
 2201300.1070173614326.355327227
#Sta/Elev= 30
       0 2432.13    37.5 2424.25   125.4 2410.46   142.4 2405.72   163.7 2393.99
   170.7 2392.26   214.9 2389.77   265.1 2394.75   284.1 2389.65   305.7 2387.42
   333.2  2386.7   358.3 2390.42   382.2 2386.52   389.2 2385.66  403.672386.487
     415 2388.88   431.6 2386.81   444.2 2389.47   456.3 2388.32   512.3 2389.26
   548.3  2388.2   576.3 2390.54   652.3 2389.95   676.3 2391.06   692.3 2397.98
   704.3 2408.92   724.3 2421.04   745.6 2422.58   756.3 2429.97   796.2  2444.6
#Mann= 6 ,-1,0
       0     .08       0      70      .1       0   382.2    .045       0
  403.67      .1       0  536.67     .08       0  726.67     .06       0
#XS Ineff= 2 , 0
          358.34    2395
Permanent Ineff=
       F       F
Bank Sta=382.2,403.67
XS Rating Curve= 0 ,0
Exp/Cntr(USF)=0,0
Exp/Cntr=0.3,0.1

Type RM Length L Ch R = 1 ,49705   ,219.4,219.4,219.4
XS GIS Cut Line= 3
2200651.99647546614601.2217236372200818.62097296614492.663338899
2201300.82217029614346.235750181
#Sta/Elev= 30
       0 2425.29    57.5 2417.02   105.2 2408.41   146.6 2399.01   176.9 2395.29
   182.3 2394.13   193.8 2389.12   204.7 2388.53   212.5 2386.87   225.6 2387.62
   242.3 2385.25   254.2 2387.39   263.2 2387.54  289.772384.027   309.2 2382.85
  318.652384.028   325.9 2385.65     344  2385.3   367.7 2386.47   418.1  2385.1
   447.1 2386.92   463.9 2385.59   481.9 2387.62   564.2 2389.41   589.3 2401.58
   618.5 2410.91   643.6 2422.96   664.5 2423.84   674.3 2431.82   702.8 2443.95
#Mann= 6 ,-1,0
       0     .08       0      40      .1       0  289.77    .045       0
  318.65      .1       0  428.87     .08       0  628.87     .06       0
Bank Sta=289.77,318.65
XS Rating Curve= 0 ,0
Exp/Cntr(USF)=0,0
Exp/Cntr=0.3,0.1

Type RM Length L Ch R = 1 ,49486   ,121.8,121.8,121.8
XS GIS Cut Line= 2
2200817.35841058614732.662849415 2201373.6824053614500.583578164
#Sta/Elev= 30
       0 2413.38    26.2 2408.03    50.7  2404.5    72.4 2399.59    94.1 2398.38
    98.4 2396.34   107.1 2387.23   111.4 2385.89   124.4 2385.85   132.6 2380.58
   148.6  2379.5  155.53  2380.6   163.4 2382.25   196.1 2380.71   202.4 2379.59
   211.1 2381.26   263.1 2382.65     300 2381.97   341.1 2384.97   427.8  2382.8
   471.1  2383.2   475.8 2384.52   488.5 2395.01   514.5 2409.78   536.1 2426.24
   553.5 2426.83   557.8 2429.48   562.2 2434.67   567.5 2438.72   602.8 2458.88
#Mann= 7 ,-1,0
       0      .1       0     130     .08       0   132.6    .045       0
  155.53      .1       0     240     .08       0     450     .06       0
     560      .1       0
Bank Sta=132.6,155.53
XS Rating Curve= 0 ,0
Exp/Cntr(USF)=0,0
Exp/Cntr=0.3,0.1

Type RM Length L Ch R = 1 ,49364   ,137.5,137.5,137.5
XS GIS Cut Line= 2
2200858.96010239614853.5431306932201381.92129322614571.170117124
#Sta/Elev= 30
       0 2406.33      15 2405.77    55.9 2399.02    78.7 2397.28   101.4 2393.89
     115 2384.18   128.7 2383.62   137.8 2378.27   142.9 2377.07   155.9 2379.59
  172.23 2378.37   192.3 2377.48   207.8 2378.43   222.6 2381.97   253.3 2380.74
   290.5 2383.07   322.9 2381.41   354.4 2383.62   393.8 2380.85   482.3 2381.25
   487.8 2384.22   519.6 2408.74   532.5 2413.39   544.3 2421.59     562 2423.34
   565.1  2424.9   573.8 2434.56   576.8 2436.52   588.6 2440.39   594.3 2443.58
#Mann= 6 ,-1,0
       0      .1       0     170     .08       0  172.23    .045       0
   207.8     .08       0     430     .06       0     580      .1       0
Bank Sta=172.23,207.8
XS Rating Curve= 0 ,0
Exp/Cntr=0.3,0.1

Type RM Length L Ch R = 1 ,49227   ,185.2,185.2,185.2
XS GIS Cut Line= 2
2200941.72624972614970.2942563422201423.65162638614624.951417304
#Sta/Elev= 30
       0 2400.89      14 2399.61    39.8 2393.59    68.5 2389.85    81.7 2382.87
    96.5 2381.61   106.4 2376.74   131.6 2377.77  148.11 2376.03   168.8 2375.11
  178.44 2376.03   197.5 2376.38   209.7 2380.03   239.2 2381.73     254 2379.92
     272 2381.04   297.2 2378.81   335.1 2381.24   367.2 2377.79   401.6 2379.58
   450.8  2379.8   470.5  2391.1   484.2 2402.98     500 2414.69     505 2417.27
     510 2417.87   541.5 2418.73     564  2436.2   583.7 2441.64   592.9 2449.61
#Mann= 7 ,-1,0
       0      .1       0  148.11    .045       0  178.44      .1       0
     240     .08       0     360     .06       0     480      .1       0
     510     .06       0
Bank Sta=148.11,178.44
XS Rating Curve= 0 ,0
Exp/Cntr(USF)=0,0
Exp/Cntr=0.3,0.1

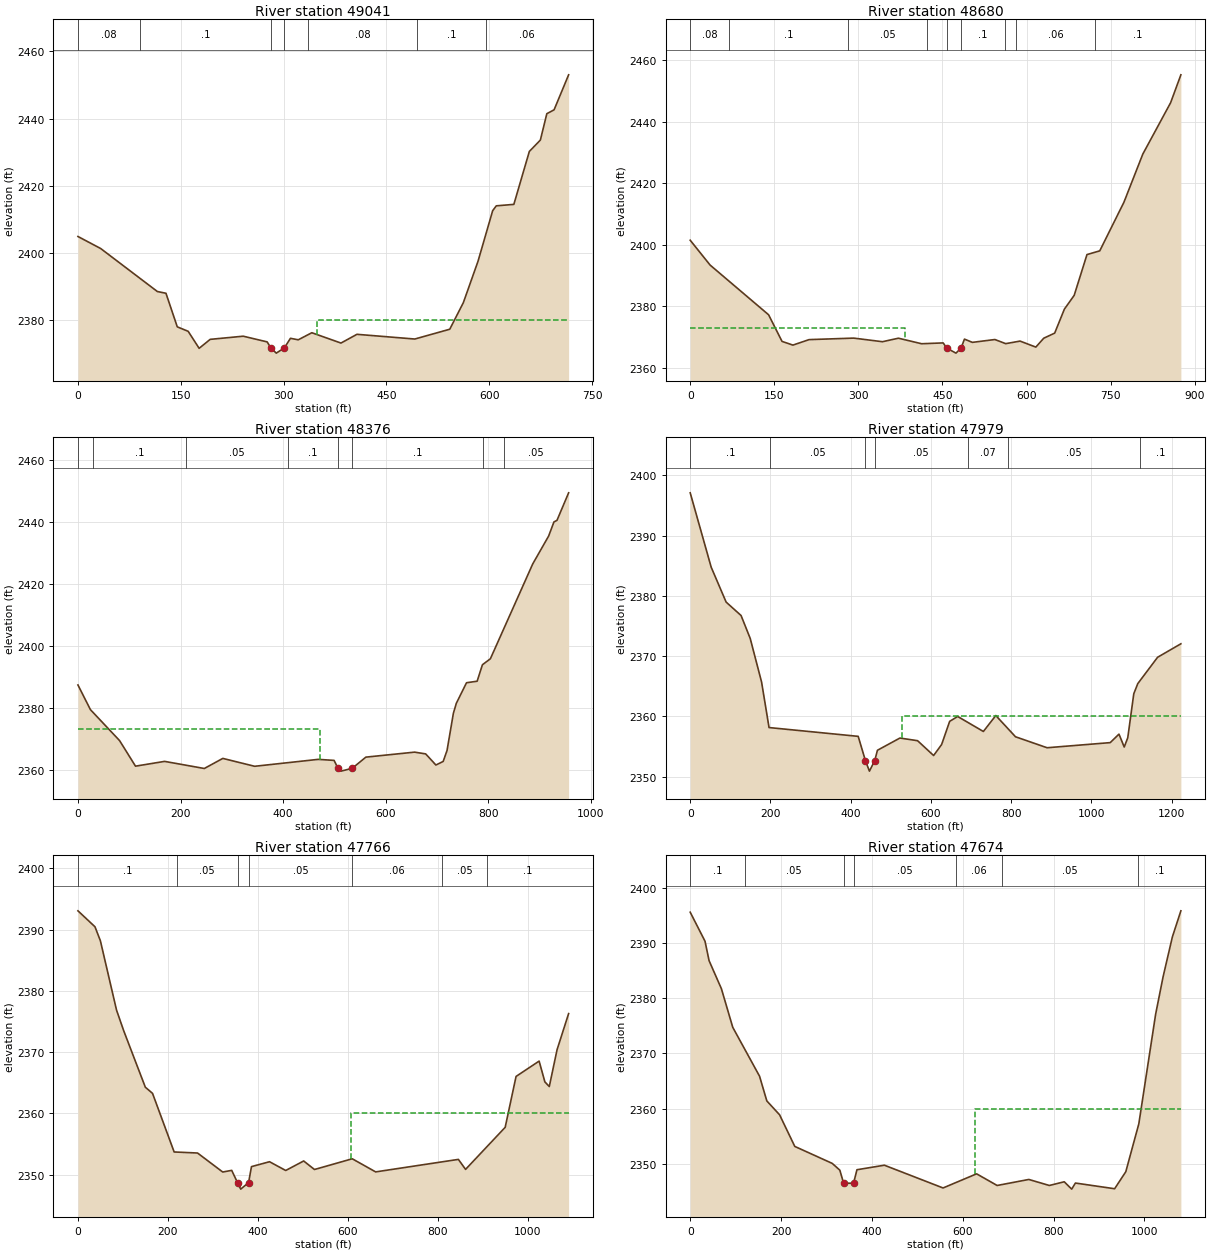
Type RM Length L Ch R = 1 ,49041   ,361.2,361.2,361.2
XS GIS Cut Line= 3
2200952.02753233615143.0189452792201092.54154841615106.144443352
 2201518.9273068614727.139271971
#Sta/Elev= 30
       0 2404.95    33.2 2401.37   115.9 2388.59   128.4 2388.08   144.9  2378.1
   160.8 2376.77   176.8 2371.72   192.9 2374.38   241.1 2375.32     276 2373.63
   281.7 2371.76   289.3 2370.29  301.022371.822     310 2374.69   321.4 2374.25
   341.2 2376.35   383.7 2373.28     407 2375.88   491.4 2374.48   542.4 2377.39
   562.2 2385.28   583.6 2397.57     605 2412.61   610.3 2414.06   635.9 2414.49
   658.5 2430.22   674.6 2433.61     684 2441.44   694.6 2442.59   715.8 2452.99
#Mann= 7 ,-1,0
       0     .08       0      90      .1       0   281.7    .045       0
  301.02      .1       0  335.27     .08       0  495.27      .1       0
  595.27     .06       0
#XS Ineff= 2 , 0
                        349.3647            2380
Permanent Ineff=
       F       F
Bank Sta=281.7,301.02
XS Rating Curve= 0 ,0
Exp/Cntr=0.3,0.1

Type RM Length L Ch R = 1 ,48680   ,304,304,304
XS GIS Cut Line= 3
2201068.83253436615428.4316836222201240.23144393615441.918051962
2201733.67714796614940.811476318
#Sta/Elev= 30
       0 2401.51    35.5 2393.44   139.8 2377.29   163.8 2368.63   183.2 2367.43
     212 2369.21   291.6  2369.7   342.9 2368.53   371.4 2369.67   412.8 2367.87
   451.2 2368.14  457.762366.429     474 2364.82  483.01 2366.43   489.2 2369.37
   503.3 2368.32   543.5 2369.24   562.7  2367.9   588.4 2368.73   616.5 2366.78
   630.6 2369.67   650.1 2371.32   667.4 2379.11   684.9  2383.6   707.7 2396.85
   730.5 2398.06   773.6 2413.85   807.3 2429.51   856.9 2446.21   875.2 2455.27
#Mann= 9 ,-1,0
       0     .08       0      70      .1       0  281.93     .05       0
  421.93      .1       0  457.76    .045       0  483.01      .1       0
  561.93     .08       0  581.93     .06       0  721.93      .1       0
#XS Ineff= 2 , 0
        383.6376    2373
Permanent Ineff=
       F       F
Bank Sta=457.76,483.01
XS Rating Curve= 0 ,0
Exp/Cntr=0.3,0.1

Type RM Length L Ch R = 1 ,48376   ,397.2,397.2,397.2
XS GIS Cut Line= 2
2201213.34148089615792.0160818692201954.31557207615187.371125011
#Sta/Elev= 30
       0 2387.35    24.3  2379.4    81.1 2369.43   112.2 2361.18   168.9 2362.72
   246.3 2360.43   282.4 2363.68   344.4 2361.14   468.3 2363.37   499.3 2363.04
  506.882360.464   512.9 2359.58  534.612360.485   561.2 2364.09   656.1  2365.7
   677.8 2365.13   697.7 2361.55   711.9  2362.7   719.4 2366.22   731.8 2378.24
   737.5 2381.43   757.4 2388.07   778.1 2388.56   788.4 2393.87   803.9 2395.79
   886.5 2426.38   917.5 2435.36   927.8  2439.9   933.7  2440.4   956.4 2449.28
#Mann= 8 ,-1,0
       0     .08       0      30      .1       0     210     .05       0
     410      .1       0  506.88    .045       0  534.61      .1       0
     790     .06       0     830     .05       0
#XS Ineff= 2 , 0
        472.5322    2373
Permanent Ineff=
       F       F
Bank Sta=506.88,534.61
XS Rating Curve= 0 ,0
Exp/Cntr(USF)=0,0
Exp/Cntr=0.3,0.1

Type RM Length L Ch R = 1 ,47979   ,213.3,213.3,213.3
XS GIS Cut Line= 4
2201259.18443145615921.1910006712201441.04907831615813.176576146
2201991.25602681615810.5506755392202413.34156616615996.508295347
#Sta/Elev= 30
       0  2397.1    52.3 2384.76    89.5 2378.97   126.8 2376.74   149.6 2372.93
   177.9  2365.7   196.5 2358.15   418.7 2356.69   436.82352.642   446.7 2350.92
   459.8 2352.64   466.7 2354.38   522.7 2356.41   566.7 2355.97   606.7 2353.51
   626.7 2355.34   646.7 2359.18   666.7 2359.99   730.7  2357.5   761.7 2360.15
   810.8 2356.62   889.5  2354.8  1046.9 2355.65  1068.7 2357.06  1081.8 2354.92
  1090.6 2356.46  1105.6 2363.75  1115.5 2365.43  1164.9 2369.81    1223 2372.05
#Mann= 7 ,-1,0
       0      .1       0     200     .05       0   436.8    .045       0
   459.8     .05       0  691.52     .07       0  791.74     .05       0
 1121.74      .1       0
#XS Ineff= 2 , 0
                        528.9468            2360
Permanent Ineff=
       F       F
Bank Sta=436.8,459.8
XS Rating Curve= 0 ,0
Exp/Cntr=0.3,0.1

Type RM Length L Ch R = 1 ,47766   ,91.5,91.5,91.5
XS GIS Cut Line= 3
2201310.29349451616035.5330372562202282.26972996616007.762287671
2202371.89351271616086.025309227
#Sta/Elev= 30
       0 2393.05    37.9 2390.45    49.9 2388.17    85.9 2376.84   101.9 2373.47
   149.9 2364.28   165.9 2363.28     214 2353.72     266 2353.55     322 2350.45
     342 2350.72  354.962348.716     362 2347.66  379.532348.718     386 2351.33
   426.1 2352.13   462.1  2350.7   502.1 2352.25   526.1 2350.86   610.1 2352.61
   662.2 2350.47   846.2 2352.51   862.2 2350.88   950.3 2357.74   974.5 2366.04
  1025.8 2368.54  1038.6 2365.15  1048.4 2364.39  1065.7  2370.4  1091.4 2376.29
#Mann= 7 ,-1,0
       0      .1       0     220     .05       0  354.96    .045       0
  379.53     .05       0     610     .06       0     810     .05       0
     910      .1       0
#XS Ineff= 1 ,-1
606.50481091.358    2360
Permanent Ineff=
       F
Bank Sta=354.96,379.53
XS Rating Curve= 0 ,0
Exp/Cntr(USF)=0,0
Exp/Cntr=0.3,0.1

Type RM Length L Ch R = 1 ,47674   ,38.7,38.7,38.7
XS GIS Cut Line= 6
2201311.56167862616054.560861486 2201523.9168345616062.805148153
2201597.13062886616095.6251249342201673.98198296616119.594436574
2201770.06666036616238.2657932532202310.33397046616363.234166383
#Sta/Elev= 30
       0 2395.57    32.6 2390.32    41.6 2386.79    68.7 2381.72    93.7 2374.73
   152.7 2365.88   168.7 2361.41   196.8  2358.9   230.3 2353.17   312.7  2350.1
   329.5 2348.87   337.8 2346.51  359.65 2346.51   367.2 2348.95   427.6 2349.77
   556.8 2345.65   630.7 2348.21   675.9  2346.1   745.7 2347.19   790.9  2346.1
   823.7 2346.77     840 2345.44   848.3 2346.54   934.6 2345.51   959.2 2348.59
   987.9 2357.27  1024.9  2377.1  1041.3 2383.87  1061.8 2391.11  1080.5 2395.82
#Mann= 7 ,-1,0
       0      .1       0     120     .05       0   337.8    .045       0
  359.65     .05       0  585.94     .06       0  685.94     .05       0
  985.94      .1       0
#XS Ineff= 2 , 0
                          627.61            2360
Permanent Ineff=
       F       F
Bank Sta=337.8,359.65
XS Rating Curve= 0 ,0
Exp/Cntr=0.3,0.1

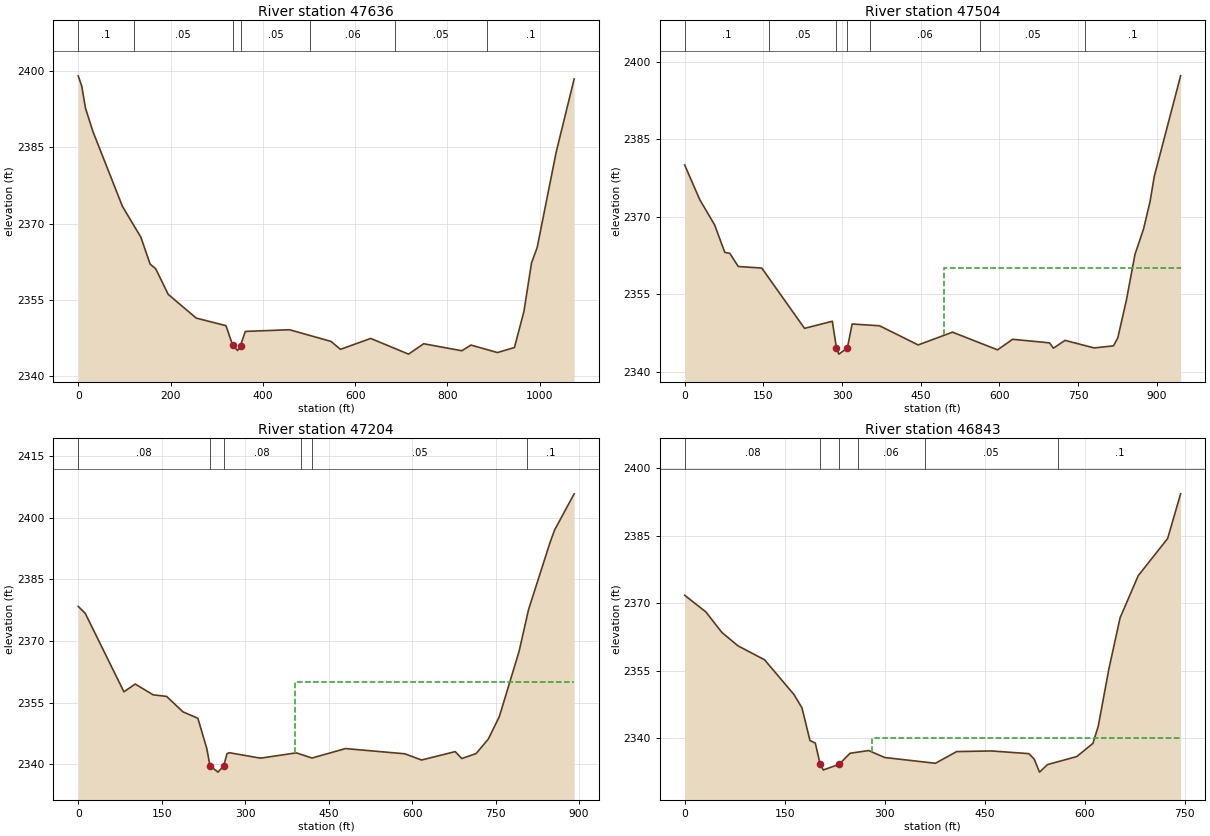
Type RM Length L Ch R = 1 ,47636   ,131.7,131.7,131.7
XS GIS Cut Line= 6
2201312.45566376616094.4888315362201524.81081964616102.733118203
  2201598.024614616135.553094984 2201674.8759681616159.522406624
 2201770.9606455616278.1937633032202306.37554925616397.500995693
#Sta/Elev= 30
       0 2399.04     7.7 2396.99    15.7 2392.71    31.7 2388.14    95.8 2373.41
   135.8 2367.34   155.8 2362.07     168 2361.13     195 2356.12   255.7 2351.46
   320.1 2349.97  334.83 2346.09   345.3 2345.09  351.64 2346.06     362 2348.84
   457.7 2349.17   547.7 2346.88   568.2 2345.32   633.7 2347.46   715.7 2344.38
   748.5 2346.42   831.1 2345.04   850.9 2346.16   908.3 2344.69   945.2 2345.68
   965.7 2352.77   982.1 2362.29   994.4 2365.32  1035.5 2384.02  1074.5 2398.43
#Mann= 7 ,-1,0
       0      .1       0     120     .05       0  334.83    .045       0
  351.64     .05       0  503.25     .06       0  685.94     .05       0
  885.94      .1       0
Bank Sta=334.83,351.64
XS Rating Curve= 0 ,0
Exp/Cntr=0.3,0.1

Type RM Length L Ch R = 1 ,47504   ,300.2,300.2,300.2
XS GIS Cut Line= 3
2201375.93344807616335.9620554862201702.87090909616271.584408722
2202301.20433195616401.602009049
#Sta/Elev= 30
       0 2380.02    28.8  2373.3    57.1 2368.42    76.5  2363.1    85.9 2362.93
   102.2 2360.37     147 2360.07   228.5  2348.4   281.5 2349.77  289.31 2344.61
   293.8 2343.41   310.1 2344.57   319.3 2349.24   371.4  2348.9   445.1 2345.19
   510.6 2347.66   596.5 2344.24   625.2 2346.28   695.5 2345.59     703 2344.56
   725.1 2346.07   780.7 2344.61   817.6 2345.01   825.8 2346.58   842.1 2353.85
   858.5 2362.71   874.9 2367.66   887.2 2372.91   895.3 2377.82   945.5 2397.27
#Mann= 7 ,-1,0
       0      .1       0     160     .05       0  289.31    .045       0
   310.1     .05       0  353.22     .06       0  563.22     .05       0
  763.22      .1       0
#XS Ineff= 2 , 0
                        494.4732            2360
Permanent Ineff=
       F       F
Bank Sta=289.31,310.1
XS Rating Curve= 0 ,0
Exp/Cntr(USF)=0,0
Exp/Cntr=0.3,0.1

Type RM Length L Ch R = 1 ,47204   ,361.1,361.1,361.1
XS GIS Cut Line= 3
2201422.19902853616588.9911097042202165.64121553616515.568201067
2202301.29753868 616563.92410669
#Sta/Elev= 30
       0 2378.43    12.6 2376.75    82.1 2357.65   102.5 2359.53   134.6 2356.91
   158.9 2356.52   188.2 2352.77     215  2351.2   231.1 2343.81  236.792339.631
   251.2  2338.1  261.46 2339.63   267.3 2342.58   271.3 2342.83   327.6  2341.5
   391.9 2342.79     420 2341.53   480.3 2343.83   586.9 2342.56     617 2341.05
   677.3 2343.09   689.3 2341.41     715 2342.62   736.9 2346.16   756.6 2351.59
   792.2  2367.5   809.2 2377.67   847.4 2393.82   855.9    2397   891.1 2405.82
#Mann= 6 ,-1,0
       0     .08       0  236.79    .045       0  261.46     .08       0
     400     .06       0     420     .05       0  807.06      .1       0
#XS Ineff= 2 , 0
                        388.6266            2360
Permanent Ineff=
       F       F
Bank Sta=236.79,261.46
XS Rating Curve= 0 ,0
Exp/Cntr=0.3,0.1

Type RM Length L Ch R = 1 ,46843   ,372.6,372.6,372.6
XS GIS Cut Line= 2
2201464.35966037616894.2602408532202207.71810884616928.545116883
#Sta/Elev= 30
       0  2371.8    31.8 2368.09    55.9 2363.52    79.9 2360.56   119.9 2357.44
     164 2349.72     176 2346.75     188 2339.48     196 2338.92   203.3 2334.21
     208 2332.94   231.8 2334.21   248.1 2336.66   276.1 2337.26   300.1 2335.71
   376.2 2334.43   408.1 2337.03   460.3 2337.17   516.4 2336.57   524.4 2335.37
   532.4 2332.46   544.4 2334.14   588.3 2335.92   612.5 2338.85   620.5 2342.65
   636.5 2355.44   653.3 2366.79   680.5 2376.15   724.6 2384.42   744.1 2394.36
#Mann= 6 ,-1,0
       0     .08       0   203.3    .045       0   231.8     .08       0
     260     .06       0     360     .05       0     560      .1       0
#XS Ineff= 2 , 0
                        281.6483            2340
Permanent Ineff=
       F       F
Bank Sta=203.3,231.8
XS Rating Curve= 0 ,0
Exp/Cntr(USF)=0,0
Exp/Cntr=0.3,0.1