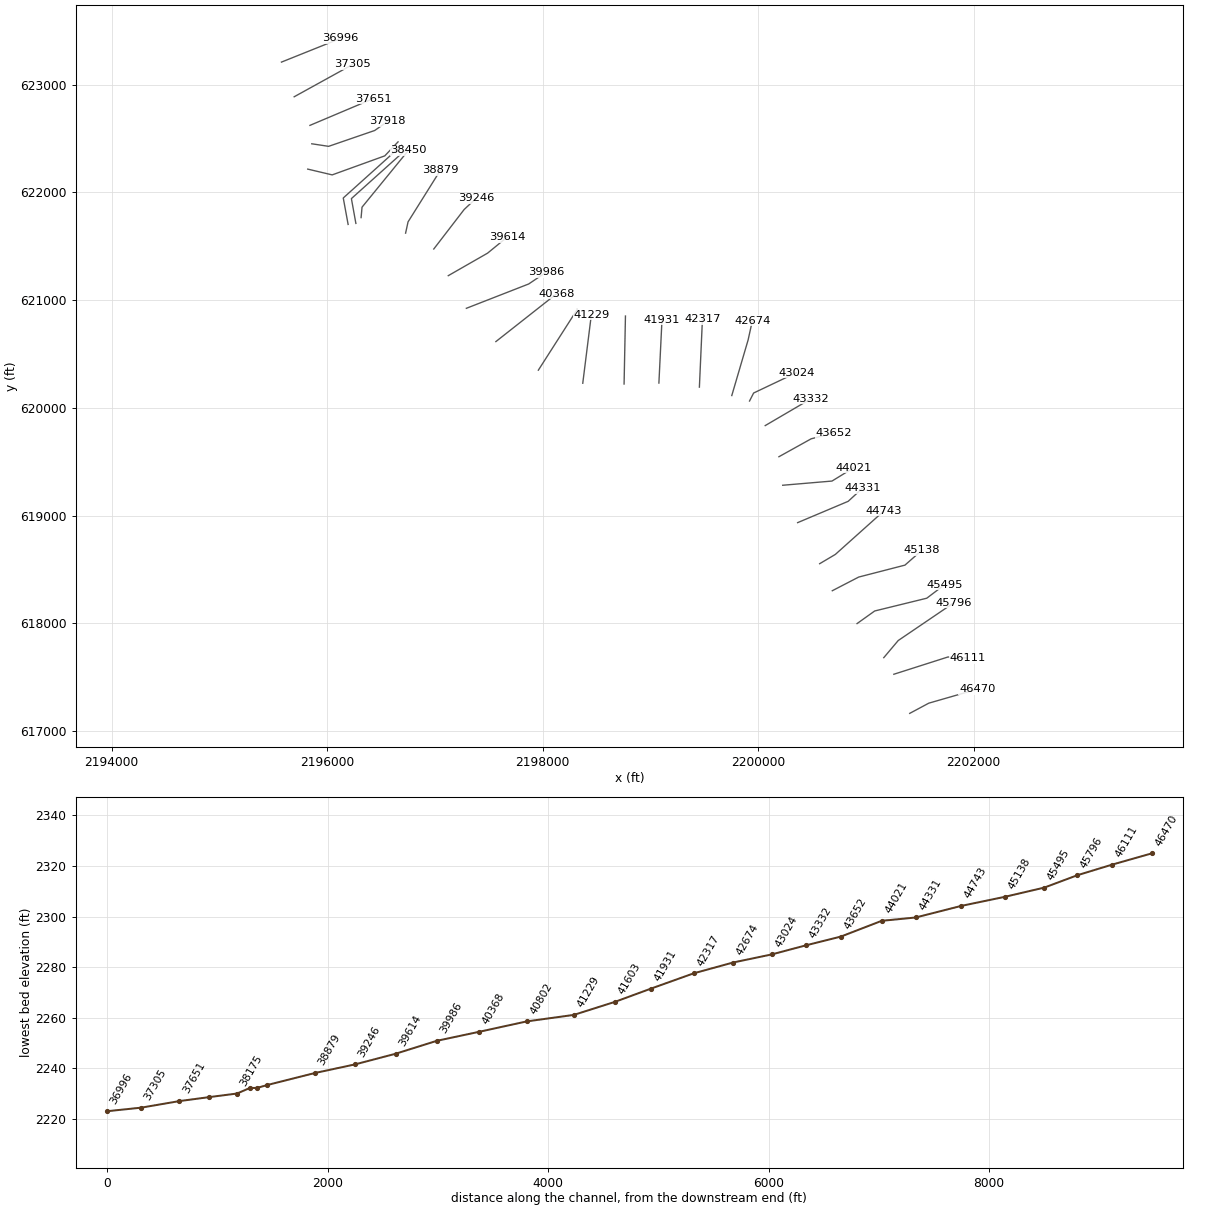
HEC-RAS study LFRFBUCRV.prj: LFRFBUCRV

--- LFRFBUCRV.g01 (geometry) --- (continued)

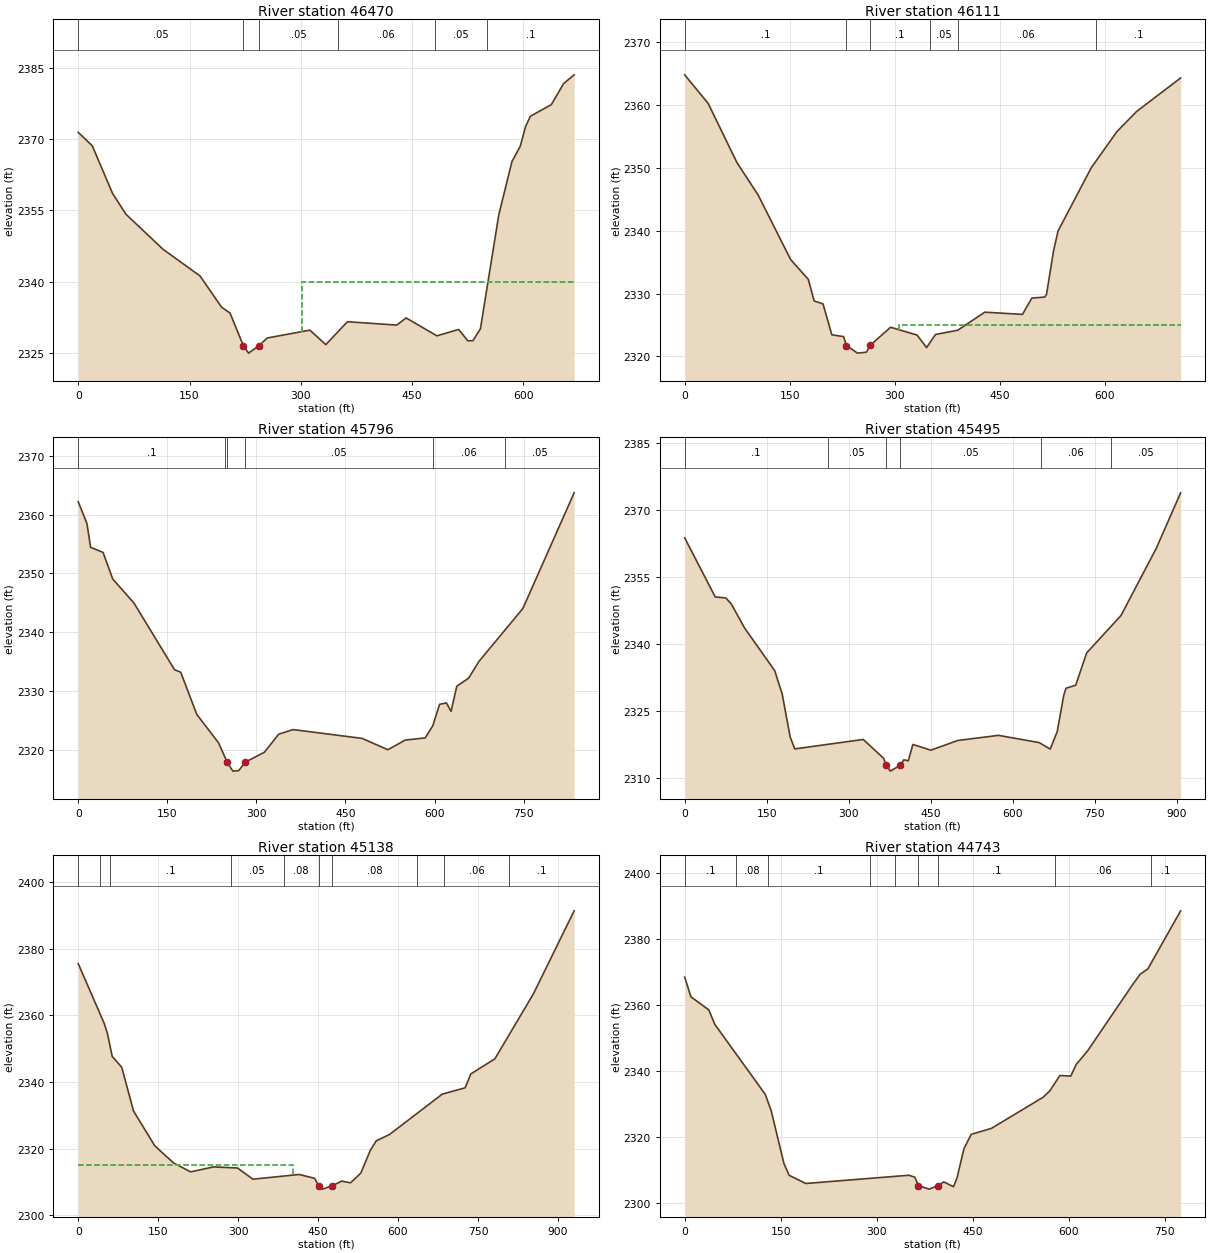
Type RM Length L Ch R = 1 ,46470   ,359.4,359.4,359.4
XS GIS Cut Line= 3
2201407.46783544617164.1836626492201584.35672647617258.926649536
2202033.79605485617388.387697208
#Sta/Elev= 30
       0 2371.46      19  2368.6    46.2 2358.62    64.3 2354.22   114.2 2346.85
   164.2 2341.22   193.3 2334.64   204.6 2333.42  222.512326.581   229.6 2324.98
   243.9 2326.58   254.6 2328.16   312.2 2329.82   333.7 2326.77   362.8 2331.59
   429.4 2330.88   441.9 2332.39   483.5 2328.62   512.7 2329.97   525.2 2327.55
     532 2327.61   542.1 2330.11   566.8 2354.07   584.5 2365.27   595.9 2368.58
   603.1 2372.75   609.5 2374.84   637.6 2377.27   654.2 2381.71   668.4 2383.55
#Mann= 6 ,-1,0
       0     .05       0  222.51    .045       0   243.9     .05       0
  350.66     .06       0  480.66     .05       0  550.66      .1       0
#XS Ineff= 2 , 0
                        301.3875            2340
Permanent Ineff=
       F       F
Bank Sta=222.51,243.9
XS Rating Curve= 0 ,0
Exp/Cntr=0.3,0.1

Type RM Length L Ch R = 1 ,46111   ,314.5,314.5,314.5
XS GIS Cut Line= 3
2201260.06244927617527.2364898542201762.76479787617687.660365884
2201942.88105184617677.279740807
#Sta/Elev= 30
       0 2364.85    33.5  2360.3    74.8 2350.84   105.1 2345.67   151.3 2335.43
   176.5 2332.28   184.9 2328.84   197.5 2328.37   210.1 2323.45   226.9 2323.16
  230.992321.744   246.7 2320.53   259.5 2320.68   264.6 2321.75     294 2324.65
   331.8 2323.41   345.4 2321.41   358.1  2323.5     390 2324.18   428.4 2327.05
   482.3  2326.7   495.6 2329.29   514.1 2329.46   516.6 2329.86   526.8  2336.9
   533.1 2339.97   580.6 2350.07   617.2 2355.81     645 2358.99   708.1 2364.35
#Mann= 6 ,-1,0
       0      .1       0  230.99    .045       0   264.6      .1       0
     350     .05       0     390     .06       0  587.68      .1       0
#XS Ineff= 1 ,-1
 305.976 708.095    2325
Permanent Ineff=
       F
Bank Sta=230.99,264.6
XS Rating Curve= 0 ,0
Exp/Cntr=0.3,0.1

Type RM Length L Ch R = 1 ,45796   ,300.9,300.9,300.9
XS GIS Cut Line= 3
2201166.70460029617681.253986087 2201300.7272975617840.211138589
2201819.67564831618192.410319625
#Sta/Elev= 30
       0  2362.2    14.7 2358.49    20.9 2354.43    41.8 2353.58    58.1 2349.05
    94.1 2344.92   162.1 2333.62   172.6 2333.18   199.7    2326   236.3 2321.17
  250.752317.882   260.4 2316.35   270.1 2316.42  281.392317.882   313.6 2319.57
   337.6 2322.64   361.9 2323.42     478 2321.92   521.5 2319.99   550.5 2321.63
   584.3 2322.01     597 2324.05   608.5 2327.72     620 2327.96   627.8 2326.52
   637.5  2330.8   657.5 2332.18   674.7 2335.01   748.7 2344.02   835.1 2363.71
#Mann= 6 ,-1,0
       0      .1       0  247.92     .05       0  250.75    .045       0
  281.39     .05       0  597.92     .06       0  717.92     .05       0
Bank Sta=250.75,281.39
XS Rating Curve= 0 ,0
Exp/Cntr(USF)=0,0
Exp/Cntr=0.3,0.1

Type RM Length L Ch R = 1 ,45495   ,356.6,356.6,356.6
XS GIS Cut Line= 4
2200918.69338316617997.5255071332201082.55081367618114.490146829
  2201565.655885618232.9288094782201731.58682419618358.543414709
#Sta/Elev= 30
       0 2363.81    55.9 2350.54    75.4 2350.32    85.4 2348.93   109.8 2343.52
   164.6 2334.01   178.4  2328.7   192.9 2319.11   201.3 2316.43   326.5 2318.55
   363.7 2314.33  368.382312.787     376 2311.44   394.62312.789   400.7 2313.98
   408.9 2313.76   417.2 2317.43   450.1 2316.14   499.3 2318.32   573.7 2319.47
   648.1 2317.85   668.4 2316.39   681.2 2320.33   693.1 2328.44   697.2 2330.05
     715 2330.73     735 2337.98   797.8 2346.38   862.4 2361.49   906.8 2373.92
#Mann= 6 ,-1,0
       0      .1       0  261.32     .05       0  368.38    .045       0
   394.6     .05       0  651.32     .06       0  778.73     .05       0
Bank Sta=368.38,394.6
XS Rating Curve= 0 ,0
Exp/Cntr=0.3,0.1

Type RM Length L Ch R = 1 ,45138   ,395.2,395.2,395.2
XS GIS Cut Line= 4
     2200688.922      618302.3832200933.80723367618429.192616837
2201363.06343573618539.934290292     2201521.928      618679.285
#Sta/Elev= 30
       0 2375.49      49 2357.47    54.9 2354.47    63.8 2347.65    81.6 2344.41
   103.8 2331.25   143.3 2320.91   155.8 2319.02   179.3 2315.63   210.9 2312.99
   253.8 2314.48   298.9 2314.15   327.8 2310.79   414.5 2312.21   443.5 2311.06
  450.922308.854   458.3 2307.81   476.5 2308.81   494.4 2310.23   510.9 2309.69
   530.2 2312.64   547.9 2319.43   559.1  2322.3   583.9  2324.2   683.1 2336.33
   725.9 2338.22   736.5 2342.38   781.6  2346.9     854 2366.43   930.4 2391.34
#Mann= 10 ,-1,0
       0      .1       0      40     .08       0      60      .1       0
  285.77     .05       0  385.77     .08       0  450.92    .045       0
   476.5     .08       0  635.77      .1       0  685.77     .06       0
  809.08      .1       0
#XS Ineff= 2 , 0
        402.7278    2315
Permanent Ineff=
       F       F
Bank Sta=450.92,476.5
XS Rating Curve= 0 ,0
Exp/Cntr=0.3,0.1

Type RM Length L Ch R = 1 ,44743   ,412.6,412.6,412.6
XS GIS Cut Line= 3
2200571.75320735618553.201841471 2200717.0926514618639.227447055
2201168.26300375619043.298606551
#Sta/Elev= 30
       0 2368.54     9.8 2362.55    37.7 2358.59      47 2354.22     126 2332.93
   135.3 2327.88     155 2312.01   163.2 2308.41   189.1 2305.93   350.2 2308.43
   359.4 2307.84   365.1 2305.31   381.7 2304.22   396.2 2305.28   404.7 2306.42
     420 2304.94   425.4 2307.63   436.1 2316.45   447.6 2320.84   479.1 2322.65
   559.6 2332.06   570.4 2334.04     586 2338.69     603  2338.5   611.5 2342.02
   629.5 2346.21   699.3 2366.16   711.4 2369.41   723.4 2371.01   774.6 2388.64
#Mann= 9 ,-1,0
       0      .1       0      80     .08       0     130      .1       0
  288.89     .05       0  328.89      .1       0   365.1    .045       0
   396.2      .1       0  578.89     .06       0  728.89      .1       0
Bank Sta=365.1,396.2
XS Rating Curve= 0 ,0
Exp/Cntr=0.3,0.1

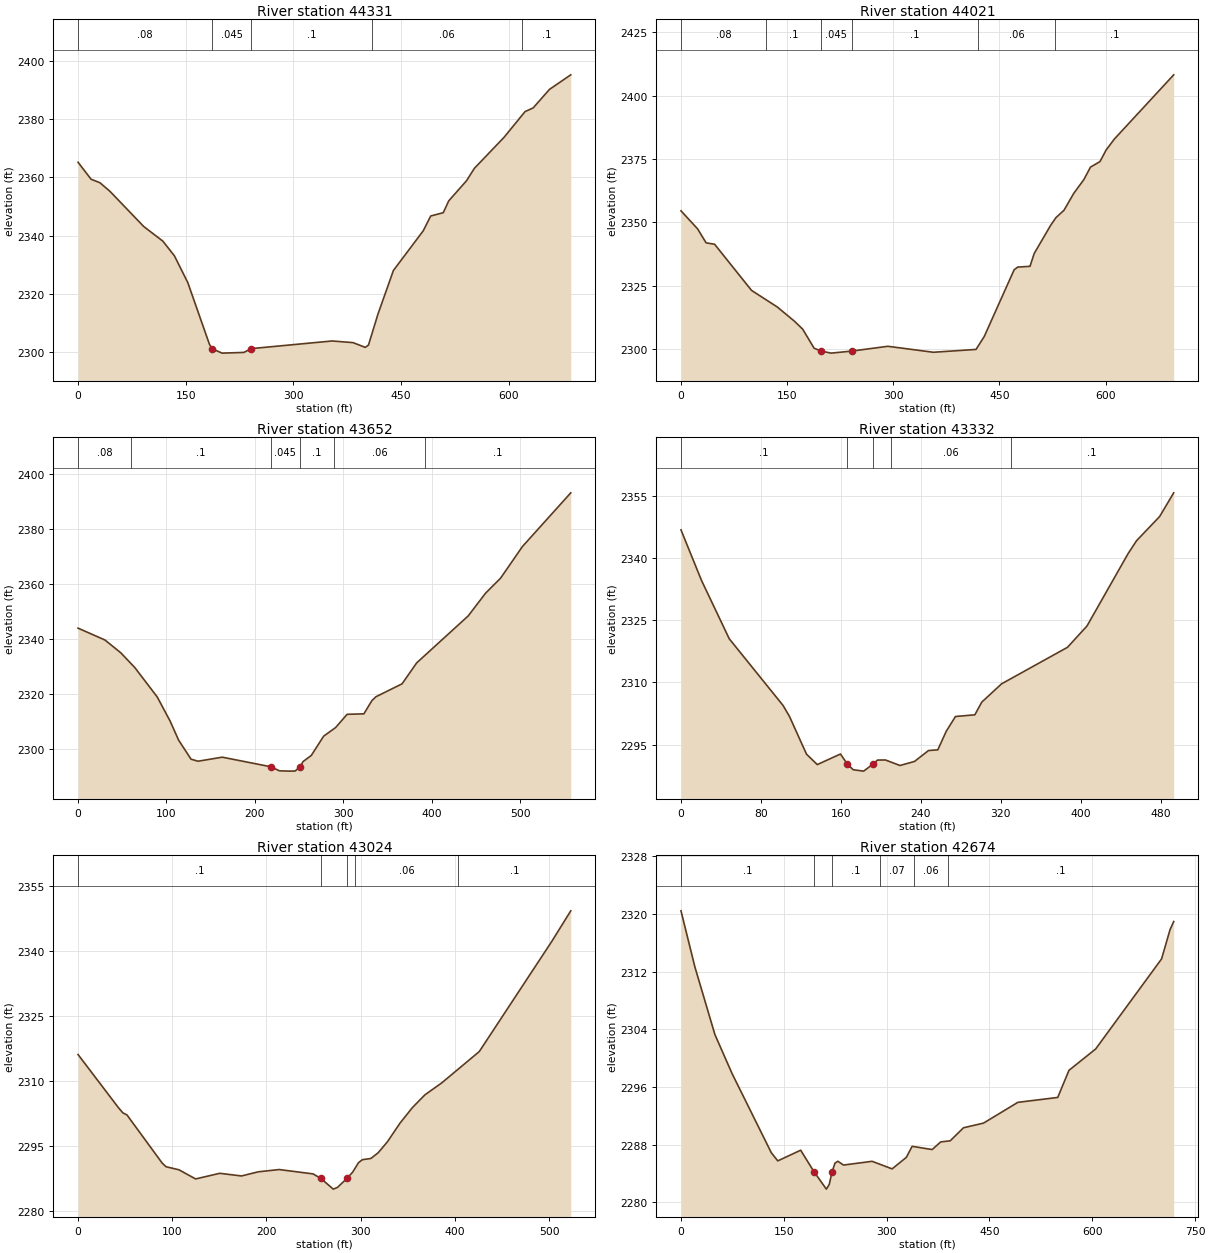
Type RM Length L Ch R = 1 ,44331   ,309.5,309.5,309.5
XS GIS Cut Line= 3
2200367.24362741618934.2103646372200836.32306764619132.127603538
2200967.22895793619252.124669642
#Sta/Elev= 30
       0 2365.16    18.2 2359.32    30.5 2358.13    44.4  2355.2    91.5 2343.11
   118.2 2338.08   134.3 2333.04     153 2323.83   183.1 2302.68  186.612301.187
   200.7 2299.64   231.1 2299.88   241.32301.184   354.1 2303.81   383.1 2303.25
   400.4 2301.61   404.8 2302.43   417.8 2312.91   439.5 2328.01     481  2341.6
   491.5 2346.71     509 2347.85   516.6  2351.9   541.5 2358.84   552.3 2363.06
   593.6 2373.69     623 2382.55   634.3 2383.82     657 2390.17   686.7 2395.17
#Mann= 5 ,-1,0
       0     .08       0  186.61    .045       0   241.3      .1       0
     410     .06       0  619.12      .1       0
Bank Sta=186.61,241.3
XS Rating Curve= 0 ,0
Exp/Cntr(USF)=0,0
Exp/Cntr=0.3,0.1

Type RM Length L Ch R = 1 ,44021   ,369.3,369.3,369.3
XS GIS Cut Line= 3
2200228.79927346619281.2416972082200686.20090456619320.158821178
2200888.40175507619444.229489854
#Sta/Elev= 30
       0 2354.49    23.5 2347.36    35.5 2341.85    47.5  2341.3    99.7 2323.08
   135.9 2316.56     160 2310.99     172 2307.77   188.1 2300.25  197.962299.134
   212.1 2298.31  241.032299.106   292.4 2301.01   356.7 2298.65   416.9 2299.77
   428.5 2304.84   470.8 2331.22   475.8 2332.27   493.2 2332.58   499.2 2337.68
   522.3 2348.72   529.8 2351.78   541.2  2354.7   555.2 2361.45   569.3  2366.8
   578.7 2371.75   592.1 2373.93   600.8  2378.5   612.5 2382.85   696.3 2408.18
#Mann= 6 ,-1,0
       0     .08       0     120      .1       0  197.96    .045       0
  241.03      .1       0     420     .06       0  529.05      .1       0
Bank Sta=197.96,241.03
XS Rating Curve= 0 ,0
Exp/Cntr=0.3,0.1

Type RM Length L Ch R = 1 ,43652   ,319.7,319.7,319.7
XS GIS Cut Line= 3
2200193.60050111 619545.946734782200493.10087302619712.408824191
2200701.15029978619765.130374923
#Sta/Elev= 30
       0 2344.04    30.4 2339.74    48.4 2335.07    64.3 2329.68    89.6 2319.02
   104.3 2310.17   113.7 2303.38   127.8 2296.43   135.7 2295.69   163.1 2297.16
  218.042293.677   227.8  2292.2   239.6 2292.09   245.6 2292.14     251 2293.68
   254.6 2295.59   263.8 2297.78   277.8  2304.8   291.3 2307.92   304.3 2312.73
   323.3 2312.91   332.4 2317.73     337 2319.13   366.5 2323.81     383 2331.42
   441.3 2348.49     461 2356.78   477.9  2362.2   502.6 2373.69   557.3 2393.21
#Mann= 6 ,-1,0
       0     .08       0      60      .1       0  218.04    .045       0
     251      .1       0     290     .06       0  392.65      .1       0
Bank Sta=218.04,251
XS Rating Curve= 0 ,0
Exp/Cntr=0.3,0.1

Type RM Length L Ch R = 1 ,43332   ,308.5,308.5,308.5
XS GIS Cut Line= 2
2200066.47176042619834.9675621522200491.91590388620084.312115098
#Sta/Elev= 30
       0 2346.81    20.5 2334.63    48.3 2320.53   102.2 2304.42   108.6 2301.78
   125.6 2292.69   136.4 2290.17   159.6 2292.72   166.6 2290.24   166.6 2290.23
   172.4 2288.92   182.8 2288.59  191.842290.223   196.7 2291.26   204.6 2291.28
   219.2 2289.95   233.8 2290.94   247.7 2293.56     257 2293.72   265.4 2298.18
   274.7 2301.77   294.1 2302.18     301 2305.24   320.8 2309.65   386.8 2318.47
   406.3 2323.61   447.4 2341.06   455.9 2344.19     479 2350.03   493.1 2355.75
#Mann= 5 ,-1,0
       0      .1       0   166.6    .045       0  191.84      .1       0
     210     .06       0     330      .1       0
Bank Sta=166.6,191.84
XS Rating Curve= 0 ,0
Exp/Cntr(USF)=0,0
Exp/Cntr=0.3,0.1

Type RM Length L Ch R = 1 ,43024   ,349.6,349.6,349.6
XS GIS Cut Line= 3
2199920.90213522620062.9047460342199958.94192196620137.297832599
2200355.92083544620325.865397429
#Sta/Elev= 30
       0 2316.08      43 2303.78    47.5 2302.64      52 2302.12    89.3 2291.03
    93.4 2290.19   107.1 2289.48   124.8 2287.37   150.4 2288.67   173.5 2288.06
   191.2 2289.01   213.5 2289.54   249.5 2288.53   257.6 2287.51   270.9 2285.02
   275.3 2285.41   285.5  2287.5   291.5 2288.95   297.7 2291.13   301.9 2291.82
   310.8 2292.09   318.6 2293.42   328.5 2295.98   341.8 2300.27     355 2303.86
   368.3  2306.8     386 2309.53   425.9 2316.77   502.8 2342.17     523 2349.24
#Mann= 5 ,-1,0
       0      .1       0   257.6    .045       0   285.5      .1       0
  293.55     .06       0  403.55      .1       0
Bank Sta=257.6,285.5
XS Rating Curve= 0 ,0
Exp/Cntr=0.3,0.1

Type RM Length L Ch R = 1 ,42674   ,357.5,357.5,357.5
XS GIS Cut Line= 3
2199756.18424191620113.6663252982199907.76274905620629.804287726
2199946.67340044620806.417296765
#Sta/Elev= 30
       0 2320.44    20.3 2312.65    49.5 2303.27    74.5 2297.87   131.7 2286.89
   141.2 2285.75   174.6 2287.23  193.982284.254   212.1 2281.83   216.3 2282.49
  220.492284.255   224.6 2285.43   228.8  2285.7   237.1 2285.17   278.8 2285.69
     308 2284.64   328.8 2286.24   337.2 2287.77   366.4 2287.32   378.9 2288.38
   392.7 2288.53   412.1 2290.34   441.4 2290.99   491.4 2293.87   549.6 2294.55
     566 2298.31   604.9 2301.27   701.1 2313.77   713.4 2317.81   718.8 2318.96
#Mann= 6 ,-1,0
       0      .1       0  193.98    .045       0  220.49      .1       0
     290     .07       0     340     .06       0     390      .1       0
Bank Sta=193.98,220.49
XS Rating Curve= 0 ,0
Exp/Cntr=0.3,0.1

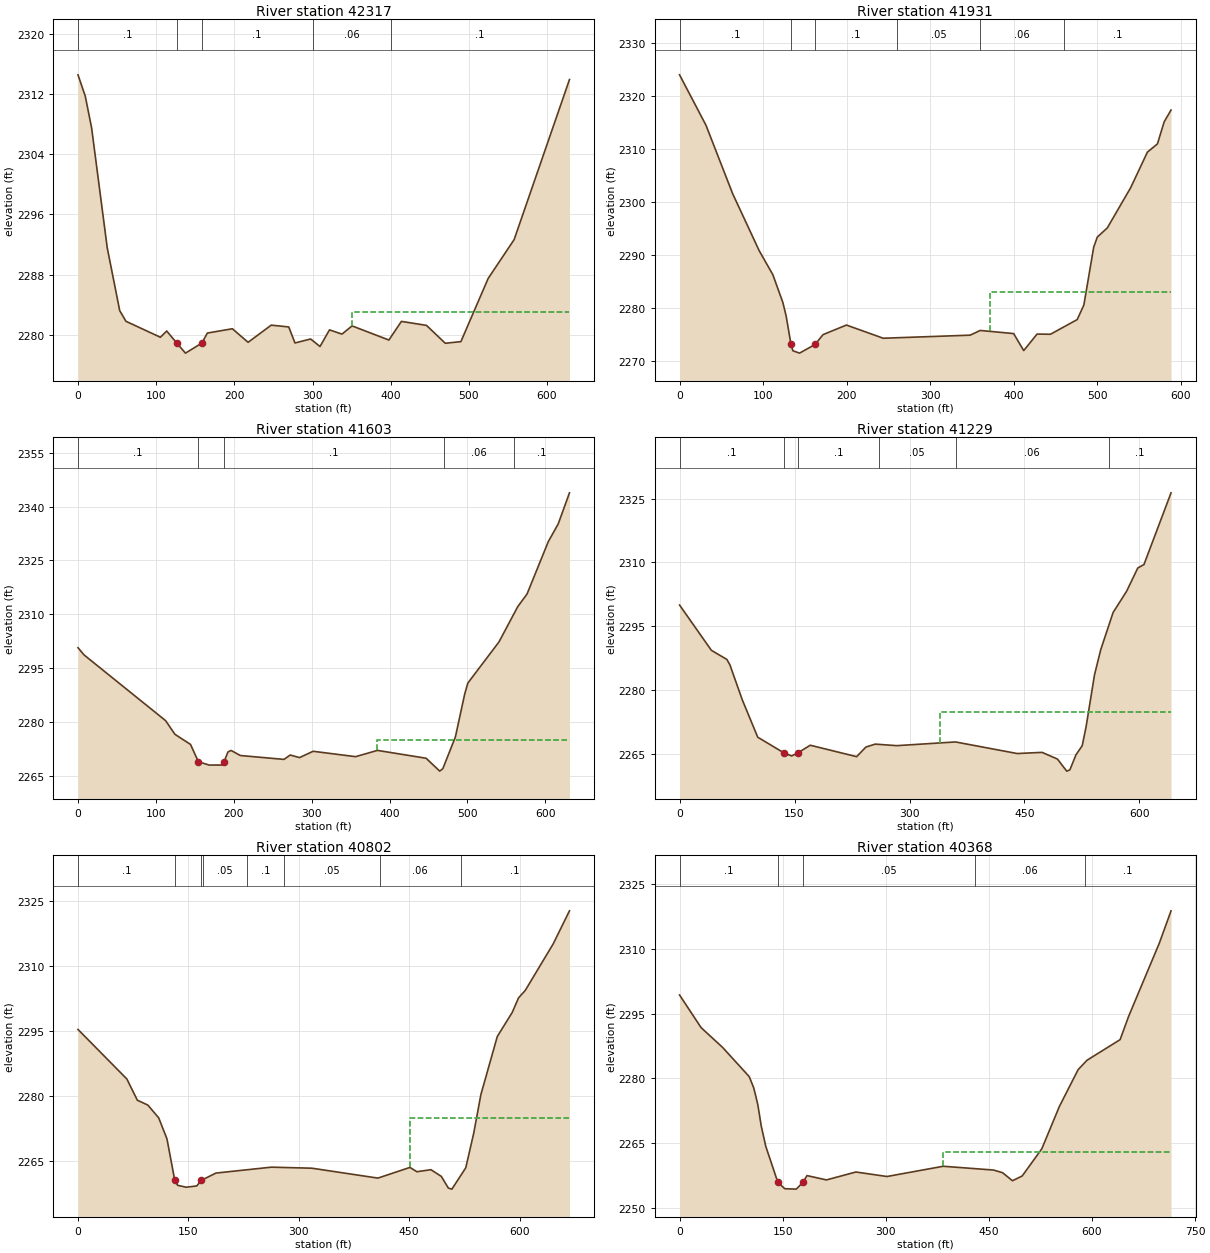
Type RM Length L Ch R = 1 ,42317   ,385.2,385.2,385.2
XS GIS Cut Line= 2
 2199455.5776057620191.8419535552199483.62886791620819.878546286
#Sta/Elev= 30
       0 2314.55     9.3 2311.72    17.4 2307.52    37.4 2291.57    53.4 2283.19
    61.4 2281.78   105.4 2279.66   113.5 2280.49  126.732278.844   137.5 2277.55
  158.422278.881   165.5 2280.22   197.5 2280.79   217.6 2278.99   247.2 2281.27
   269.6 2281.03   277.6  2278.9   297.6 2279.43   309.6 2278.43   321.7 2280.64
   337.7 2280.08   350.6 2281.17   397.7 2279.29   413.7 2281.77   445.8 2281.24
   469.8 2278.86   489.8 2279.08   524.7 2287.48   557.9 2292.64   628.7 2313.92
#Mann= 5 ,-1,0
       0      .1       0  126.73    .045       0  158.42      .1       0
     300     .06       0     400      .1       0
#XS Ineff= 1 ,-1
350.3329628.6627    2283
Permanent Ineff=
       F
Bank Sta=126.73,158.42
XS Rating Curve= 0 ,0
Exp/Cntr(USF)=0,0
Exp/Cntr=0.3,0.1

Type RM Length L Ch R = 1 ,41931   ,327.9,327.9,327.9
XS GIS Cut Line= 2
2199079.76017882620229.6136739022199108.48121941620817.419982721
#Sta/Elev= 30
       0 2324.07    31.6 2314.57    63.6 2301.63    95.4 2290.86   111.7 2286.35
   123.7  2281.1   127.7  2278.5  133.422273.181   135.7 2271.99   143.7 2271.54
  162.352273.184   171.8 2275.03   199.8 2276.84   243.9 2274.35     348 2274.93
     360 2275.82     400 2275.23   412.1 2272.02   428.1 2275.14   444.1  2275.1
   476.1 2277.87   484.1 2280.61   495.9 2291.54   500.2 2293.44   512.2 2295.18
   540.2 2302.78   560.2 2309.48   572.2 2311.03   580.3 2315.21   588.5 2317.42
#Mann= 6 ,-1,0
       0      .1       0  133.42    .045       0  162.35      .1       0
     260     .05       0     360     .06       0     460      .1       0
#XS Ineff= 2 , 0
                             372            2283
Permanent Ineff=
       F       F
Bank Sta=133.42,162.35
XS Rating Curve= 0 ,0
Exp/Cntr=0.3,0.1

Type RM Length L Ch R = 1 ,41603   ,374.5,374.5,374.5
XS GIS Cut Line= 2
2198756.66178963620220.724218608     2198769.382      620851.735
#Sta/Elev= 30
       0 2300.67     7.8 2298.66   112.5 2280.35   124.5 2276.54   144.5 2273.72
  154.582268.909   168.4 2267.97   184.5 2267.98  187.532268.866   192.5  2271.6
   196.5 2272.05   208.5 2270.63   264.5 2269.55   272.5 2270.77   284.5 2270.05
   301.9 2271.81   356.5 2270.31   384.5 2272.06     447 2269.87   464.5 2266.28
   468.5 2266.97   484.6 2275.79   496.6 2287.79   500.6 2290.82   540.6 2302.29
   564.7 2312.12   576.6 2315.63   603.9 2330.23   616.6 2335.15   631.1 2343.83
#Mann= 5 ,-1,0
       0      .1       0  154.58    .045       0  187.53      .1       0
     470     .06       0     560      .1       0
#XS Ineff= 2 , 0
                           384.3            2275
Permanent Ineff=
       F       F
Bank Sta=154.58,187.53
XS Rating Curve= 0 ,0
Exp/Cntr=0.3,0.1

Type RM Length L Ch R = 1 ,41229   ,426.9,426.9,426.9
XS GIS Cut Line= 2
2198373.21211493620227.9695356662198452.90511794620864.154722727
#Sta/Elev= 30
       0 2300.03    41.5 2289.42    61.7 2287.28    65.7 2286.01    81.8 2277.83
     102 2269.05   135.82265.417   146.3 2264.66   154.7 2265.42   170.5 2267.17
     231 2264.49   243.1 2266.74   255.2 2267.43   283.4 2267.07     360 2267.94
   440.6 2265.22   472.9  2265.5     493 2263.93   505.1  2261.1   509.2 2261.39
   517.2 2264.93   525.3 2267.05   530.4 2271.54   541.4 2283.71   549.5 2289.57
   565.6 2298.28   583.3 2303.28   597.8 2308.71   605.9 2309.53   641.2 2326.33
#Mann= 6 ,-1,0
       0      .1       0   135.8    .045       0   154.7      .1       0
     260     .05       0     360     .06       0     560      .1       0
#XS Ineff= 2 , 0
                           339.8            2275
Permanent Ineff=
       F       F
Bank Sta=135.8,154.7
XS Rating Curve= 0 ,0
Exp/Cntr=0.3,0.1

Type RM Length L Ch R = 1 ,40802   ,434.4,434.4,434.4
XS GIS Cut Line= 2
2197961.06869149620349.240702602 2198321.0598898620911.824350185
#Sta/Elev= 30
       0 2295.32    66.4 2283.91    80.7 2279.01    94.9  2277.9   109.7 2274.95
   120.9 2270.12  131.462260.611   135.4 2259.41   147.1 2258.97   161.4 2259.27
  167.622260.562   187.5 2262.23   262.8 2263.59   317.8 2263.35   407.6 2261.07
   451.1 2263.53   460.6 2262.54   479.6 2263.01   493.8 2261.46   503.3 2258.77
   508.1 2258.53     527 2263.46   537.9 2271.51   547.5  2280.3   569.8 2293.69
   590.1 2299.24   598.7  2302.6   607.8 2304.31   645.8 2315.04   667.9 2322.65
#Mann= 8 ,-1,0
       0      .1       0  131.46    .045       0  167.62      .1       0
     170     .05       0     230      .1       0     280     .05       0
     410     .06       0     520      .1       0
#XS Ineff= 2 , 0
                           451.1            2275
Permanent Ineff=
       F       F
Bank Sta=131.46,167.62
XS Rating Curve= 0 ,0
Exp/Cntr(USF)=0,0
Exp/Cntr=0.3,0.1

Type RM Length L Ch R = 1 ,40368   ,381.3,381.3,381.3
XS GIS Cut Line= 2
2197566.83600301620614.4502298612198128.56797368621056.835930082
#Sta/Elev= 30
       0  2299.3    31.4 2291.74    62.6 2287.18   101.4 2280.41   107.9 2277.82
   111.1 2275.79     114  2273.8   118.8 2269.03   125.4 2264.31  143.052255.938
   153.1 2254.49   169.7 2254.39  179.412255.938   185.4 2257.52   213.7 2256.52
   256.5 2258.35   301.8 2257.31   383.6 2259.68     457  2258.8   469.9 2258.19
   484.3 2256.33   498.5 2257.44     527 2263.72   552.6 2273.53   579.8 2282.02
   592.7  2284.2   640.9 2288.97   653.4  2294.4   697.9 2311.27     715 2318.77
#Mann= 5 ,-1,0
       0      .1       0  143.05    .045       0  179.41     .05       0
     430     .06       0     590      .1       0
#XS Ineff= 2 , 0
                           383.6            2263
Permanent Ineff=
       F       F
Bank Sta=143.05,179.41
XS Rating Curve= 0 ,0
Exp/Cntr=0.3,0.1

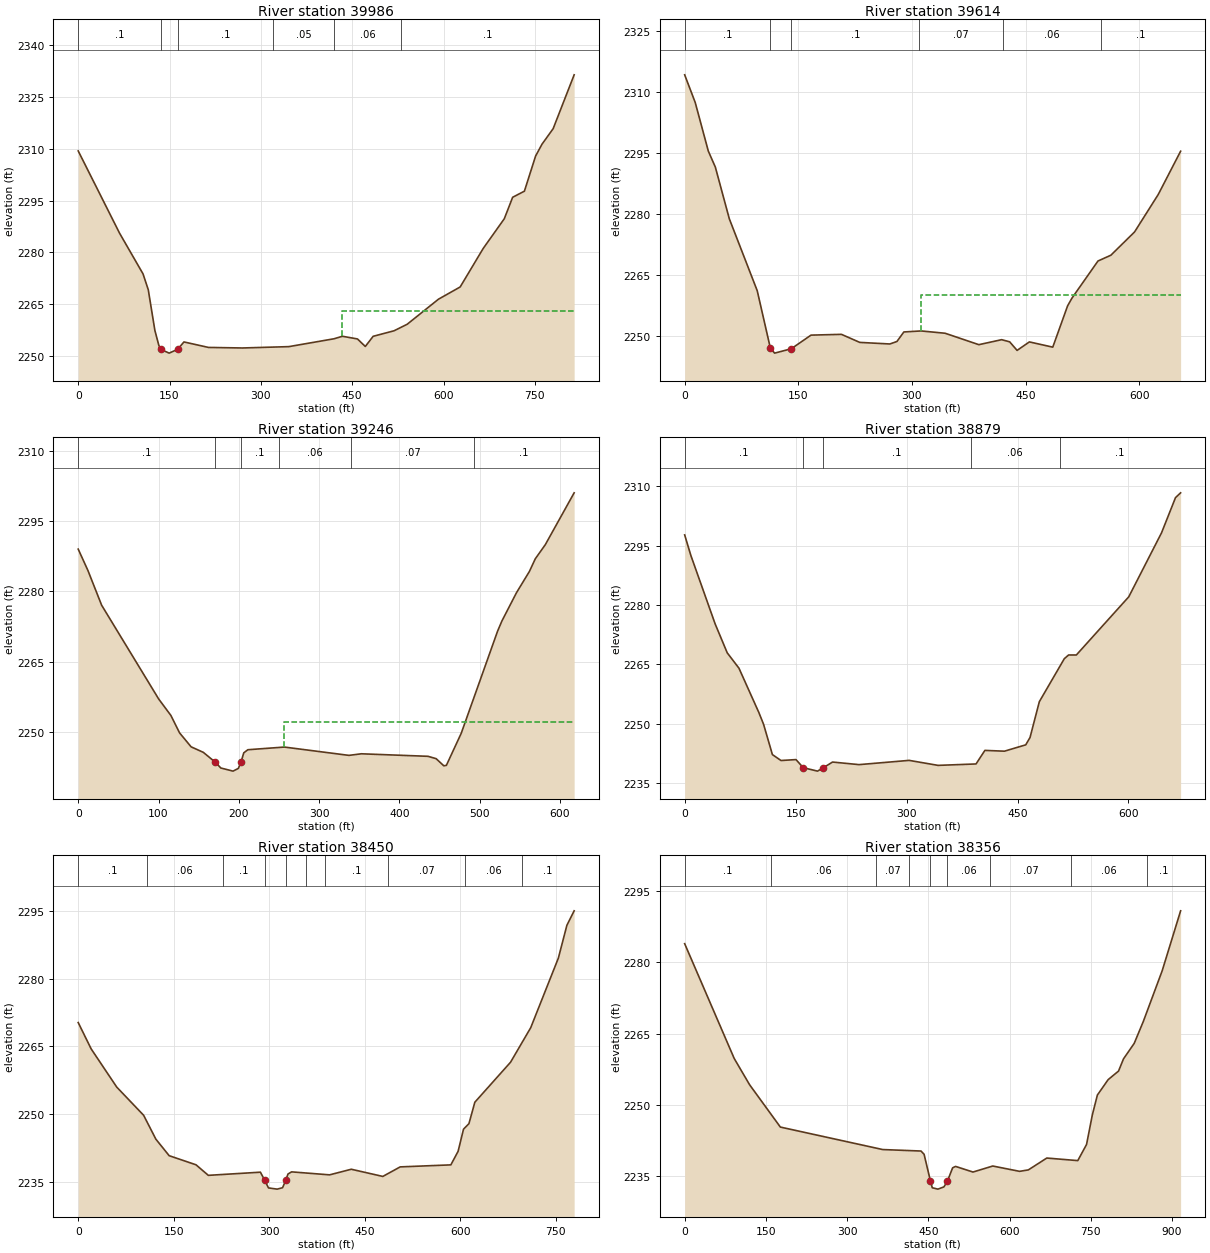
Type RM Length L Ch R = 1 ,39986   ,372.4,372.4,372.4
XS GIS Cut Line= 3
2197292.97464838620923.3783538312197871.72681214621149.317394416
2198031.91964236621257.290489854
#Sta/Elev= 30
       0  2309.4    67.8 2285.62   106.5 2273.78   115.1 2269.18   125.9 2257.44
   132.3 2253.16  135.392251.947   149.4 2250.85  163.292251.956   173.7 2254.09
   213.9  2252.5   269.7 2252.34   345.9 2252.73     420    2255   433.9 2255.73
   458.6 2254.96   471.5 2252.78   484.4 2255.72   518.7 2257.32   540.2  2259.2
   591.7 2266.47   627.3 2270.01   665.2 2281.18   699.8 2289.77   713.5 2295.98
   732.8 2297.75   751.2 2307.93   761.7 2311.35     780 2315.84   814.5 2331.44
#Mann= 6 ,-1,0
       0      .1       0  135.39    .045       0  163.29      .1       0
     320     .05       0     420     .06       0     530      .1       0
#XS Ineff= 2 , 0
                           433.9            2263
Permanent Ineff=
       F       F
Bank Sta=135.39,163.29
XS Rating Curve= 0 ,0
Exp/Cntr=0.3,0.1

Type RM Length L Ch R = 1 ,39614   ,367.5,367.5,367.5
XS GIS Cut Line= 3
2197125.06483243621226.2781697822197489.78297368621435.169924855
2197671.29403456621583.669838458
#Sta/Elev= 30
       0 2314.23    13.9 2307.44    31.2 2295.47    40.5 2291.52    58.9 2278.83
    95.8  2261.1  113.252246.894   118.8 2245.75   140.8 2246.83   166.8 2250.18
     207 2250.37   231.2 2248.39   270.9    2248   280.2 2248.61   289.4 2250.96
   312.2 2251.21   343.9 2250.64   388.4 2247.83   418.5 2249.06   429.1 2248.53
   438.9 2246.42   455.1 2248.51     486 2247.22   505.6 2257.39   511.5 2259.33
   545.7 2268.42   562.7 2269.84     594 2275.57   625.3  2284.8   654.8 2295.43
#Mann= 6 ,-1,0
       0      .1       0  113.25    .045       0   140.8      .1       0
     310     .07       0     420     .06       0   550.3      .1       0
#XS Ineff= 2 , 0
                           312.2            2260
Permanent Ineff=
       F       F
Bank Sta=113.25,140.8
XS Rating Curve= 0 ,0
Exp/Cntr=0.3,0.1

Type RM Length L Ch R = 1 ,39246   ,367.2,367.2,367.2
XS GIS Cut Line= 3
2196990.62842898621473.7157490472197272.47539442621840.211100664
2197385.88085574621946.233933895
#Sta/Elev= 30
       0 2289.05    12.1 2284.48    29.2 2277.04   100.2 2256.98   115.4 2253.46
   126.2 2249.73   140.6 2246.74   155.8 2245.56   170.9 2243.42   177.6 2242.21
   192.8 2241.54   199.4 2242.12  202.672243.446   206.2 2245.46   211.3 2246.12
   256.7 2246.69   337.2 2244.91   352.5 2245.25   435.6 2244.71   445.7 2244.21
   455.3 2242.68   458.5 2242.78     477 2249.65   522.2 2271.47   527.6 2273.66
   545.8 2279.73   561.9 2284.28   569.2 2286.98   581.7 2290.01   617.6  2301.1
#Mann= 6 ,-1,0
       0      .1       0   170.9    .045       0  202.67      .1       0
     250     .06       0     340     .07       0  492.34      .1       0
#XS Ineff= 2 , 0
                           256.7            2252
Permanent Ineff=
       F       F
Bank Sta=170.9,202.67
XS Rating Curve= 0 ,0
Exp/Cntr=0.3,0.1

Type RM Length L Ch R = 1 ,38879   ,429.2,429.2,429.2
XS GIS Cut Line= 3
2196729.11646311621620.945771929 2196751.7476097621725.310954169
2197051.00559786622203.027698903
#Sta/Elev= 30
       0 2297.68     8.4 2292.48    41.2 2275.23    57.5 2267.95    73.4 2264.06
   100.3 2252.88   106.7  2249.9   118.6 2242.27   130.2 2240.78   150.5 2241.01
   160.3 2238.97   179.6  2238.1  187.422238.944   199.9 2240.39   235.7 2239.74
   303.5 2240.81   342.6 2239.55   393.9 2239.91   405.9 2243.33   432.3 2243.13
   461.1 2244.73   466.9 2246.58   479.5 2255.62   513.3 2266.47   519.1  2267.4
   529.5 2267.39   600.4 2282.07   644.7 2298.21   663.6 2307.09   670.5  2308.3
#Mann= 5 ,-1,0
       0      .1       0   160.3    .045       0  187.42      .1       0
  386.79     .06       0  506.79      .1       0
Bank Sta=160.3,187.42
XS Rating Curve= 0 ,0
Exp/Cntr=0.3,0.1

Type RM Length L Ch R = 1 ,38450   ,94.3,94.3,94.3
XS GIS Cut Line= 3
2196316.08726581621764.9636643252196324.74506278621861.930990471
2196755.90335225622390.056606084
#Sta/Elev= 30
       0 2270.25    20.3 2264.43    60.5 2255.97   102.8 2249.72     122 2244.44
   142.9 2240.78     185 2238.77   204.4 2236.43   286.2 2237.13  293.142235.311
   298.9 2233.65   312.5 2233.38     321 2233.69  326.042235.309   329.5 2236.72
   335.2  2237.2   394.9 2236.54     429 2237.78   478.5 2236.19   505.8  2238.3
   585.4 2238.75   596.8 2241.75   605.3 2246.65   613.8 2247.87   623.1 2252.62
   679.2 2261.47   710.9 2269.12   754.3 2284.52   767.7 2291.78   779.1 2294.98
#Mann= 10 ,-1,0
       0      .1       0  107.35     .06       0  227.35      .1       0
  293.14    .045       0  326.04      .1       0  357.35     .06       0
  387.35      .1       0  487.35     .07       0  607.35     .06       0
  697.35      .1       0
Bank Sta=293.14,326.04
XS Rating Curve= 0 ,0
Exp/Cntr(USF)=0,0
Exp/Cntr=0.3,0.1

Type RM Length L Ch R = 1 ,38356   ,64.5,64.5,64.5
XS GIS Cut Line= 3
2196267.65167048621711.1731649842196226.09424499 621941.47056458
2196733.44114786622396.870685584
#Sta/Elev= 30
       0 2283.95    91.5 2259.75   119.9 2254.22   176.7  2245.3   365.8 2240.56
   436.4 2240.25   442.1 2239.56  453.92 2233.89   457.2 2232.51   467.6 2232.22
   478.7 2232.69   485.1 2233.88   494.8 2236.71   500.2 2237.01   532.4 2235.82
   568.9 2237.09   618.4 2235.97   634.6 2236.27   668.7 2238.77   725.9 2238.23
   742.1 2241.63   752.8 2247.87   762.1 2252.05     782  2255.3   801.2 2257.11
   810.3 2259.67   830.1 2262.94   847.1 2267.61   881.8 2278.26   915.8 2290.88
#Mann= 9 ,-1,0
       0      .1       0     160     .06       0  354.02     .07       0
  414.02     .06       0  453.92    .045       0   485.1     .06       0
  564.02     .07       0  714.02     .06       0  854.02      .1       0
Bank Sta=453.92,485.1
XS Rating Curve= 0 ,0
Exp/Cntr(USF)=0,0
Exp/Cntr=0.3,0.1

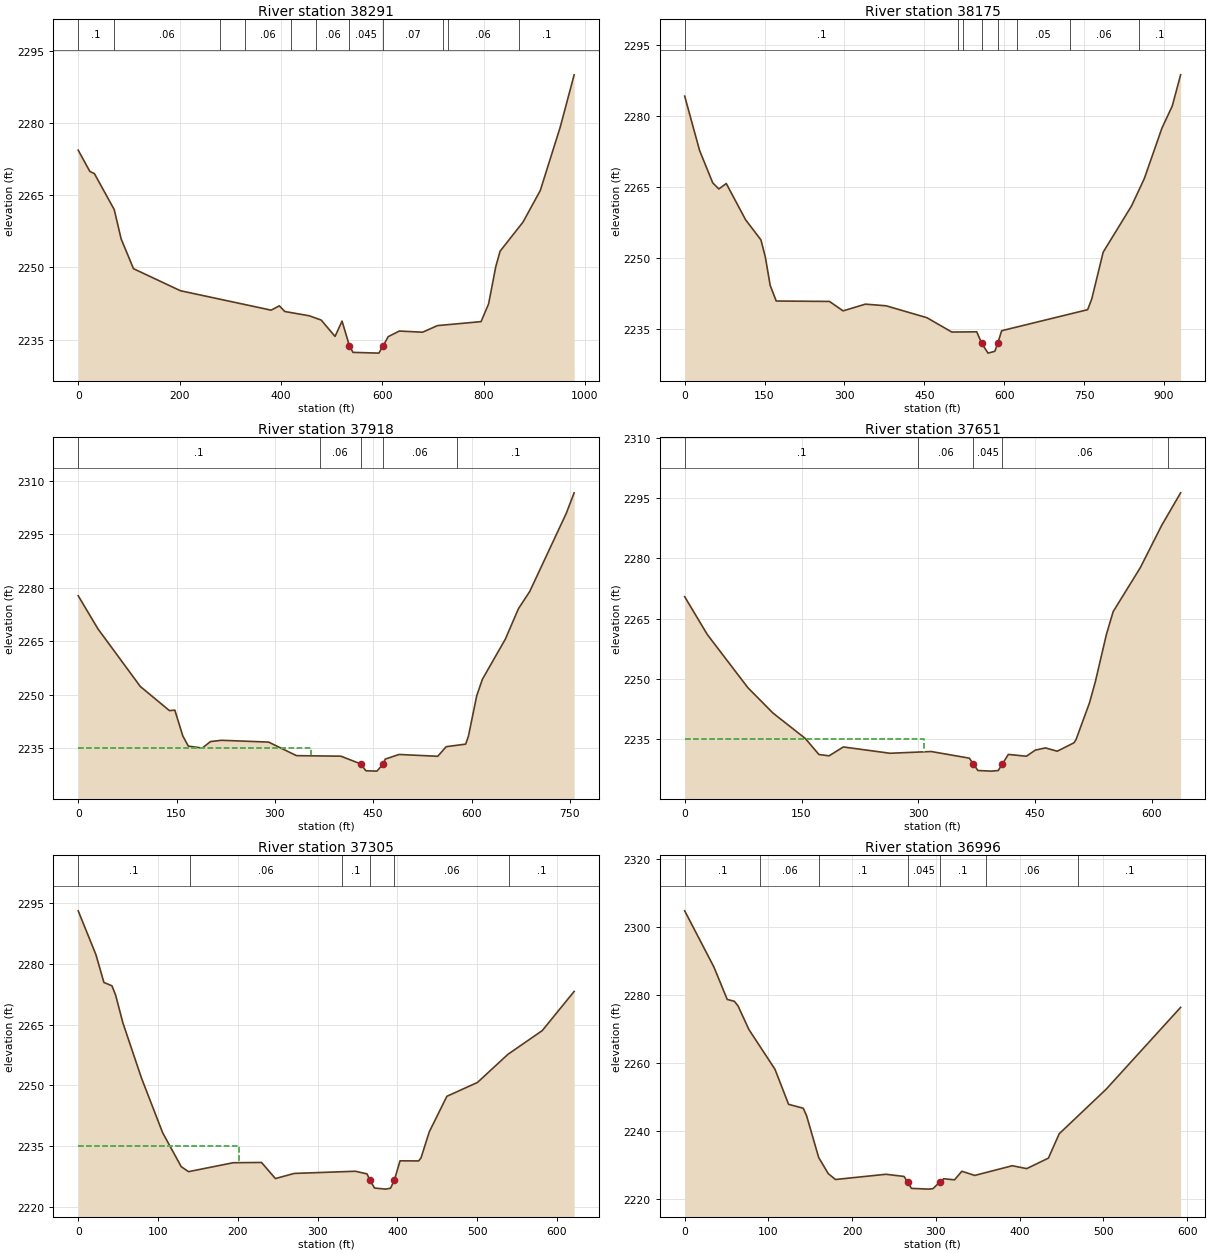
Type RM Length L Ch R = 1 ,38291   ,116.7,116.7,116.7
XS GIS Cut Line= 3
2196195.62933679621701.8344707362196150.59276993 621947.20814962
2196692.73108654622435.080256782
#Sta/Elev= 30
       0 2274.38      23 2269.96    31.9 2269.52    71.1 2262.03    84.7 2255.95
   109.1 2249.75   201.7 2245.17   380.7 2241.13   396.9 2242.03   407.8 2240.85
   456.1 2239.96   479.6 2239.07   506.9 2235.67   520.7 2238.86   535.2 2233.75
   542.2 2232.36   593.3  2232.2  602.25 2233.78   611.7 2235.62   633.7 2236.79
   679.7 2236.55     709 2237.92   795.1 2238.75     810 2242.45   824.1 2250.16
   832.6 2253.38   877.9 2259.44   911.9 2265.98   951.2 2279.13   978.8 2290.04
#Mann= 11 ,-1,0
       0      .1       0      70     .06       0  279.47     .07       0
  329.47     .06       0  419.47     .07       0  469.47     .06       0
   535.2    .045       0  602.25     .07       0  719.47     .05       0
  729.47     .06       0  869.47      .1       0
Bank Sta=535.2,602.25
XS Rating Curve= 0 ,0
Exp/Cntr(USF)=0,0
Exp/Cntr=0.3,0.1

Type RM Length L Ch R = 1 ,38175   ,256.6,256.6,256.6
XS GIS Cut Line= 4
2195820.86127871622215.1691071432196047.69555951622161.490765884
2196535.99530903 622338.109824222196658.93602611 622467.97677888
#Sta/Elev= 30
       0 2284.25    28.1 2272.74    52.7 2265.94    64.2 2264.65    78.1  2265.8
   114.4 2258.15   143.2  2253.9   151.4  2250.3   160.6 2244.29   171.9    2241
   271.9 2240.91   297.4 2238.92   339.4 2240.34   378.2 2239.99   454.8 2237.48
   501.6 2234.45   548.4  2234.5  557.652232.089   569.6    2230   582.4 2230.39
  587.832232.088   595.2 2234.73   756.6 2239.17   764.3 2241.41   785.8 2251.31
   839.2  2261.1   863.2 2266.89   896.1 2277.49   915.5 2282.16   931.2 2288.74
#Mann= 8 ,-1,0
       0      .1       0   513.1     .07       0   523.1     .06       0
  557.65    .045       0  587.83     .06       0   623.1     .05       0
   723.1     .06       0  852.36      .1       0
Bank Sta=557.65,587.83
XS Rating Curve= 0 ,0
Exp/Cntr(USF)=0,0
Exp/Cntr=0.3,0.1

Type RM Length L Ch R = 1 ,37918   ,267.4,267.4,267.4
XS GIS Cut Line= 4
2195858.47030237622450.100978436  2196014.795931622426.419353389
2196442.49110167622573.6019020022196562.20731315622657.542820754
#Sta/Elev= 30
       0 2277.71      30 2268.46    94.8 2252.27   139.2 2245.52   147.4 2245.65
   159.6 2238.41     168 2235.57   189.2 2235.03   201.9 2236.85   218.8  2237.2
   290.4  2236.7     333  2232.9   400.7 2232.75  431.112230.575   438.8 2228.67
   455.7 2228.56  465.352230.575   468.4 2231.93   489.5 2233.23   548.5 2232.72
   561.4 2235.41   591.1 2236.13   595.3 2238.35     608 2249.71   616.7 2254.33
   651.6 2265.54   671.6 2274.07   688.9 2278.93   744.4 2300.73   756.6 2306.55
#Mann= 5 ,-1,0
       0      .1       0  368.11     .06       0  431.11    .045       0
  465.35     .06       0  578.11      .1       0
#XS Ineff= 2 , 0
        355.6235    2235
Permanent Ineff=
       F       F
Bank Sta=431.11,465.35
XS Rating Curve= 0 ,0
Exp/Cntr=0.3,0.1

Type RM Length L Ch R = 1 ,37651   ,345.7,345.7,345.7
XS GIS Cut Line= 2
2195841.37048756622621.049545606 2196427.8885141622868.969615261
#Sta/Elev= 30
       0 2270.44    29.1 2261.01    81.2 2247.77   113.3 2241.48   154.9 2235.13
   172.4 2231.14   185.4 2230.81   203.7 2233.02   263.6 2231.45   316.6 2231.88
   365.5 2230.23  370.772228.751   376.5 2227.15   393.9    2227   402.6 2227.15
  407.852228.751   415.6 2231.16   438.7 2230.71   450.3 2232.24   463.2 2232.78
   478.4 2231.96   499.8 2234.05   502.5 2234.85   519.8 2244.01   527.3 2249.27
   541.5 2261.03   550.2 2266.73     585 2277.66   612.7 2288.28   636.8 2296.31
#Mann= 5 ,-1,0
       0      .1       0     300     .06       0  370.77    .045       0
  407.85     .06       0     620      .1       0
#XS Ineff= 2 , 0
        307.3279    2235
Permanent Ineff=
       F       F
Bank Sta=370.77,407.85
XS Rating Curve= 0 ,0
Exp/Cntr=0.3,0.1

Type RM Length L Ch R = 1 ,37305   ,309.2,309.2,309.2
XS GIS Cut Line= 2
2195695.12103626622886.4612293232196239.17526675623186.890247553
#Sta/Elev= 30
       0 2293.06    22.2 2282.25    32.2  2275.4    42.3 2274.56    46.9 2272.26
      56 2265.42    79.3 2251.81   105.8 2238.33   129.1 2229.95   138.3 2228.72
   194.1 2230.92   229.7 2230.99   247.1 2227.02   270.7 2228.28   347.2 2228.82
   361.9 2228.17  365.772226.575   371.3 2224.69     385 2224.41   391.4 2224.63
   396.12226.573   403.3 2231.39   426.7 2231.37   429.6 2232.12   439.9 2238.52
     462 2247.31   500.3 2250.72   538.5 2257.66   581.5 2263.51   621.5 2273.18
#Mann= 6 ,-1,0
       0      .1       0     140     .06       0     330      .1       0
  365.77    .045       0   396.1     .06       0     540      .1       0
#XS Ineff= 2 , 0
        201.1247    2235
Permanent Ineff=
       F       F
Bank Sta=365.77,396.1
XS Rating Curve= 0 ,0
Exp/Cntr(USF)=0,0
Exp/Cntr=0.3,0.1

Type RM Length L Ch R = 1 ,36996   ,384.8,384.8,384.8
XS GIS Cut Line= 2
2195577.02445439623208.1834046312196126.76702488623428.757580434
#Sta/Elev= 30
       0 2304.84    34.9 2288.33    50.8 2278.79    59.4 2278.23    63.7 2276.89
    76.7 2269.94   107.8 2258.27   124.1 2247.94   141.6 2246.79   145.6  2244.6
   160.1 2232.26   171.5 2227.56   180.1 2225.83   240.4 2227.37     262 2226.73
   266.3 2225.05   270.8 2223.22   291.8    2223   296.5 2223.13   304.6 2225.06
   309.4 2226.05   322.3 2225.74     331 2228.26   346.4 2227.03   391.3 2229.88
   408.5 2229.03   434.4 2232.12   447.3 2239.28   503.4 2252.39   592.3 2276.45
#Mann= 7 ,-1,0
       0      .1       0      90     .06       0     160      .1       0
   266.3    .045       0   304.6      .1       0     360     .06       0
     470      .1       0
Bank Sta=266.3,304.6
XS Rating Curve= 0 ,0
Exp/Cntr=0.3,0.1