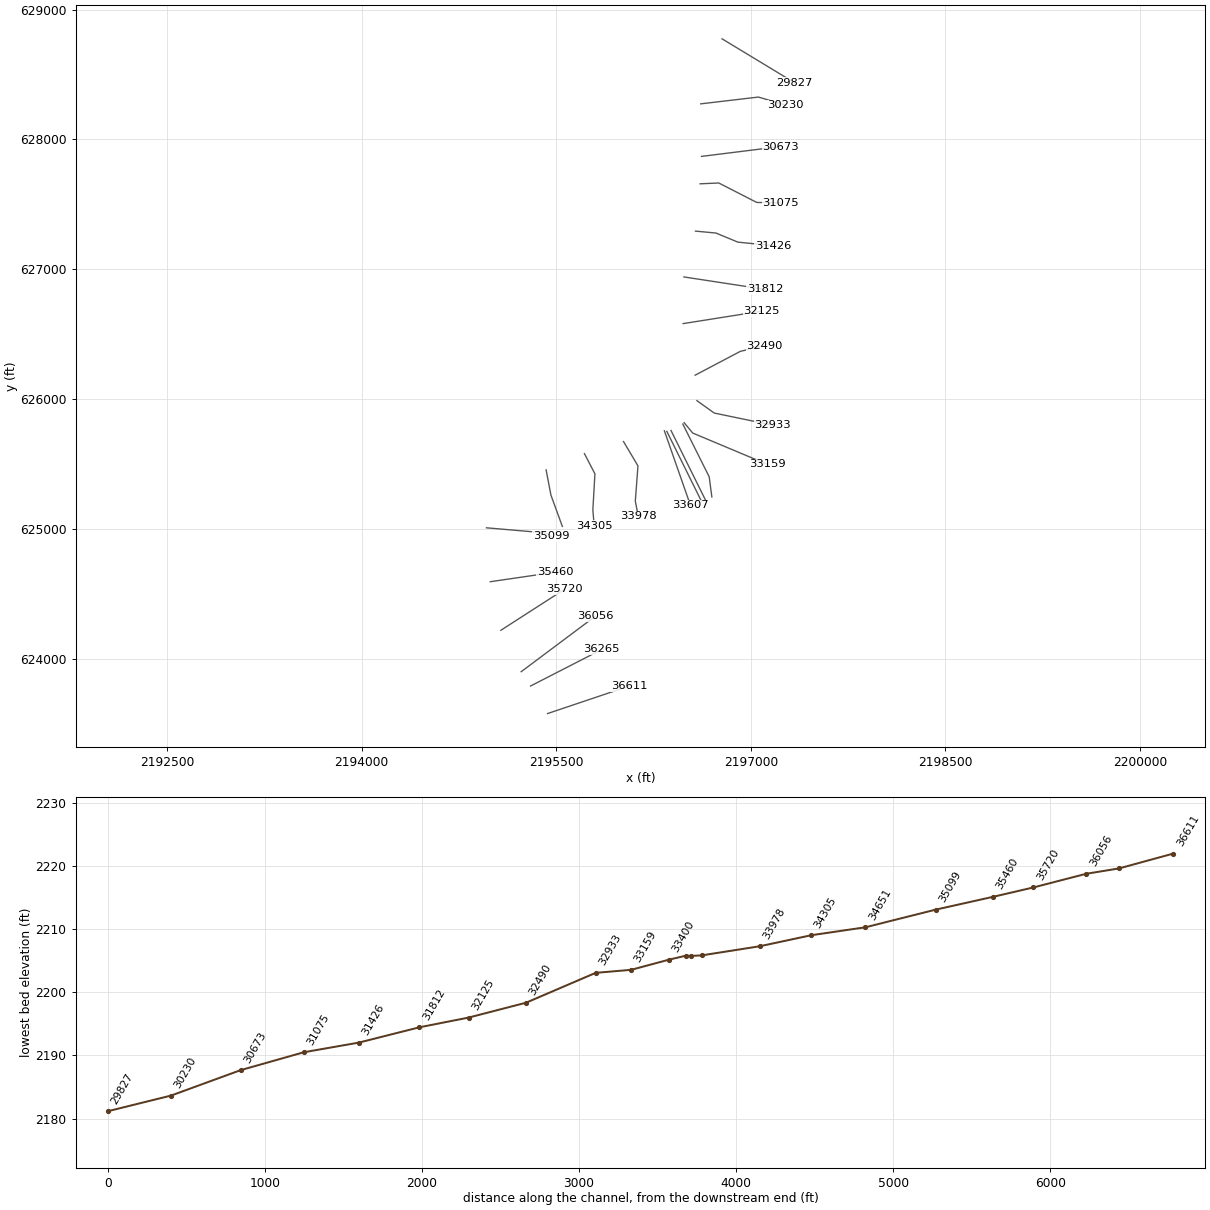
HEC-RAS study LFRFBUCRV.prj: LFRFBUCRV

--- LFRFBUCRV.g01 (geometry) --- (continued)

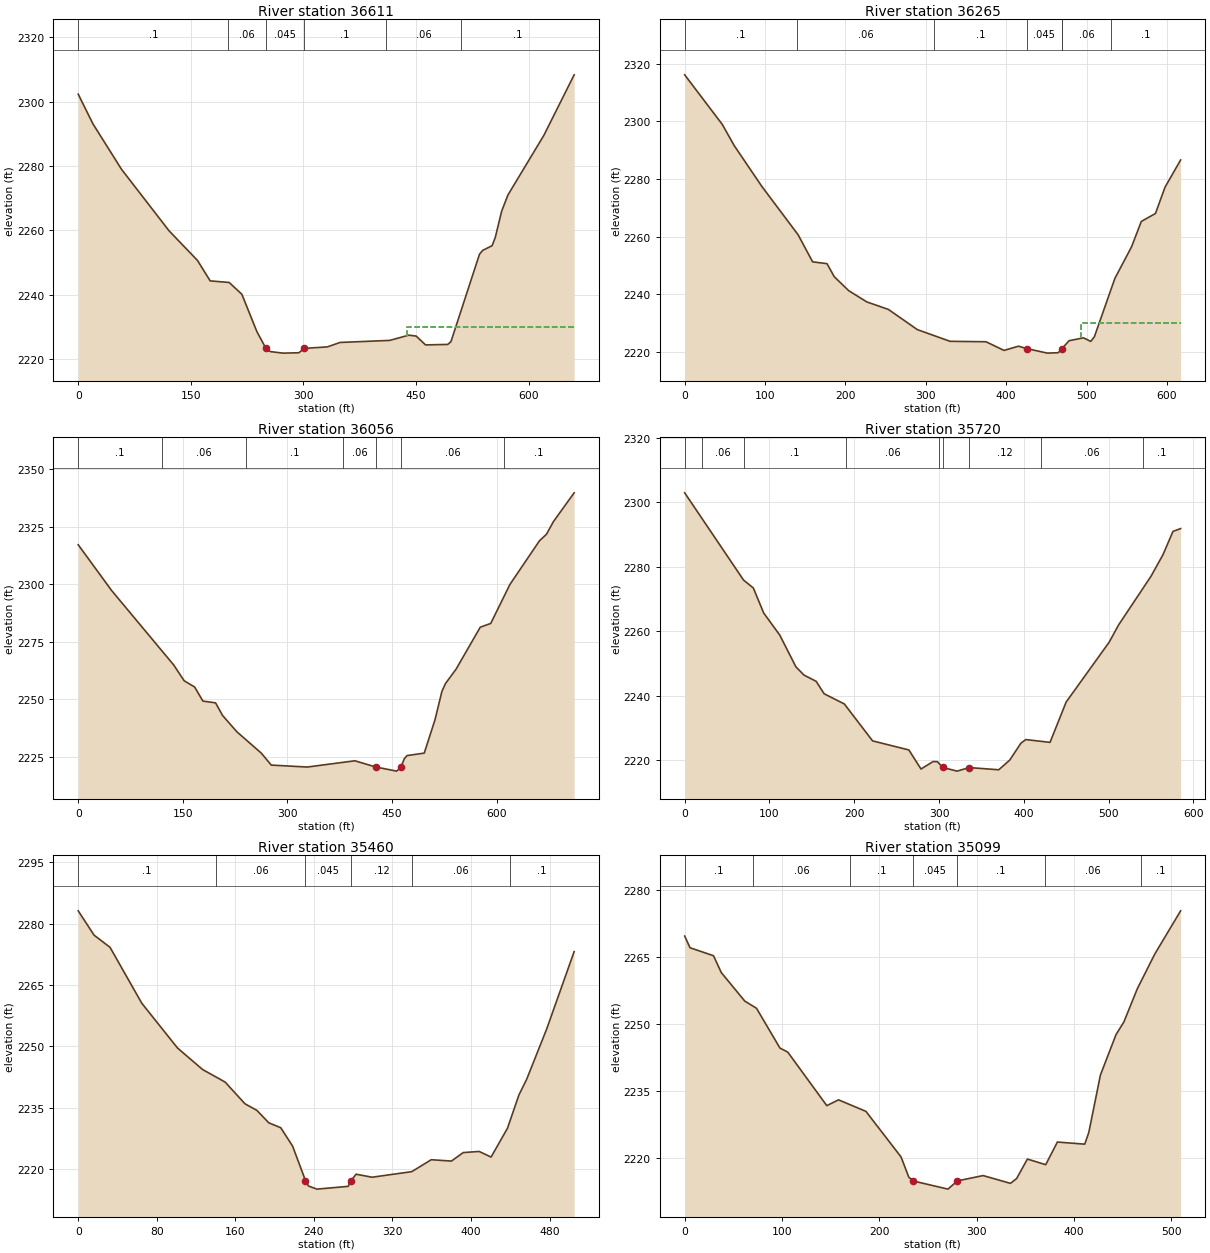
Type RM Length L Ch R = 1 ,36611   ,346.2,346.2,346.2
XS GIS Cut Line= 2
 2195433.5864179623578.1345223872196059.76600166623788.704510778
#Sta/Elev= 30
       0 2302.28    19.6 2293.08    57.6    2279   120.9 2259.92   158.9 2250.69
   175.8 2244.35   201.1 2243.86     218  2240.2   238.1 2228.55  250.082223.416
   255.9 2222.42   272.7 2221.94   293.9 2222.05  301.152223.415   331.9 2223.87
   348.8 2225.25     415 2225.89   440.3 2227.51   450.1 2227.23   462.7 2224.49
   492.3 2224.64   496.5  2225.5   534.5 2252.61   538.7 2253.81   551.3 2255.27
   555.6 2257.87     564 2265.95   572.4    2271   620.3 2289.52   660.6 2308.28
#Mann= 6 ,-1,0
       0      .1       0     200     .06       0  250.08    .045       0
  301.15      .1       0     410     .06       0     510      .1       0
#XS Ineff= 2 , 0
                        437.7569            2230
Permanent Ineff=
       F       F
Bank Sta=250.08,301.15
XS Rating Curve= 0 ,0
Exp/Cntr=0.3,0.1

Type RM Length L Ch R = 1 ,36265   ,208.8,208.8,208.8
XS GIS Cut Line= 2
2195302.54362168623790.2728976112195851.64707937624071.767313852
#Sta/Elev= 30
       0 2316.17    46.8 2298.96    61.6 2291.62    96.2 2277.38   141.2 2260.65
   159.2 2251.27   177.1 2250.64   186.1 2246.12   204.1 2241.27   226.6 2237.37
   253.6 2234.74   289.5 2227.75   330.2 2223.69   374.9 2223.54   397.4 2220.53
   415.4    2222  425.742221.165   451.3 2219.59   464.8 2219.73   469.3 2221.11
   478.3  2223.9   496.3  2224.9   505.3 2223.66   509.8 2225.27   535.3 2245.52
   556.1 2256.51   568.2 2265.29   585.8 2268.05   597.7 2277.18   617.1 2286.62
#Mann= 7 ,-1,0
       0      .1       0     140     .06       0     310      .1       0
  425.74    .045       0   469.3      .1       0     470     .06       0
     530      .1       0
#XS Ineff= 1 ,-1
493.1659617.0524    2230
Permanent Ineff=
       F
Bank Sta=425.74,469.3
XS Rating Curve= 0 ,0
Exp/Cntr(USF)=0,0
Exp/Cntr=0.3,0.1

Type RM Length L Ch R = 1 ,36056   ,336.2,336.2,336.2
XS GIS Cut Line= 2
2195230.47232732623900.5695291152195799.98837823624326.249409304
#Sta/Elev= 30
       0 2317.17    47.8 2297.31     137 2264.86   151.9 2258.03   166.9 2255.32
   178.8 2249.19   196.9 2248.43   206.9 2242.98   227.4 2235.87   262.5 2226.56
   276.8 2221.36   328.4 2220.52   396.6 2223.24   426.6 2220.53   456.6 2218.74
  462.752220.547   467.5 2224.12   471.5  2225.5   496.1 2226.58   511.5 2241.08
   521.5 2253.49   526.5  2256.8   541.8 2263.11   576.4 2281.32   591.4 2282.95
   618.9  2299.9   661.3  2318.9   671.3 2321.73   681.3 2327.24     711 2339.75
#Mann= 7 ,-1,0
       0      .1       0     120     .06       0     240      .1       0
     380     .06       0   426.6    .045       0  462.75     .06       0
     610      .1       0
Bank Sta=426.6,462.75
XS Rating Curve= 0 ,0
Exp/Cntr=0.3,0.1

Type RM Length L Ch R = 1 ,35720   ,259.7,259.7,259.7
XS GIS Cut Line= 2
2195073.79821905  624219.59079742195565.71743993624536.062530924
#Sta/Elev= 30
       0 2302.88    69.4 2275.84      81 2273.36    93.2 2265.61   112.2 2258.74
   131.2 2248.91   140.8 2246.35     155 2244.44   164.5 2240.57   188.3 2237.41
   221.6 2225.96   264.4 2223.15   278.7 2217.23     293 2219.55   298.1 2219.51
  304.222217.746   321.2 2216.58   335.6 2217.68   370.4    2217   383.3 2219.98
   396.5 2225.23   402.3 2226.37   430.9  2225.5   449.9    2238   500.7 2256.59
   511.7 2261.89   549.9 2276.98   564.1 2283.69   575.9 2290.92   584.9 2291.79
#Mann= 9 ,-1,0
       0      .1       0      20     .06       0      70      .1       0
     190     .06       0     300     .12       0  304.22    .045       0
   335.6     .12       0     420     .06       0     540      .1       0
Bank Sta=304.22,335.6
XS Rating Curve= 0 ,0
Exp/Cntr(USF)=0,0
Exp/Cntr=0.3,0.1

Type RM Length L Ch R = 1 ,35460   ,360.7,360.7,360.7
XS GIS Cut Line= 2
2194992.15023714624593.572325029 2195491.8942438624666.551101158
#Sta/Elev= 30
       0 2283.13    16.2 2277.17    32.4 2274.21    64.7 2260.55   101.1 2249.59
   126.7 2244.32   149.6 2241.26   169.8 2235.95   181.9 2234.34   194.1 2231.29
   206.2  2230.1   218.3  2225.6  231.432217.173   234.5 2215.84   243.1 2215.08
   274.9 2215.76  277.882217.173     283 2218.73   299.2 2217.99   339.6 2219.35
   359.5 2222.27     380 2221.94   392.1 2224.02   408.3 2224.29   420.4 2222.92
   437.1 2229.96   448.7 2238.06   456.8 2242.02     477 2254.21     505 2273.16
#Mann= 6 ,-1,0
       0      .1       0     140     .06       0  231.43    .045       0
  277.88     .12       0     340     .06       0     440      .1       0
Bank Sta=231.43,277.88
XS Rating Curve= 0 ,0
Exp/Cntr=0.3,0.1

Type RM Length L Ch R = 1 ,35099   ,448.6,448.6,448.6
XS GIS Cut Line= 3
 2194962.6837247625008.8058407962195419.93815401624969.267448145
2195462.60202821624942.242689875
#Sta/Elev= 30
       0 2269.63     5.5 2267.02    29.6 2265.24    37.6 2261.48    61.7 2255.11
    73.8 2253.49    97.9  2244.6   105.9  2243.7     146 2231.74   158.1 2233.03
   186.2 2230.46   222.3 2220.27   230.3 2215.73     235 2214.89   270.5 2213.08
   280.12214.916   306.6 2216.11   334.7 2214.37     341 2215.44   352.1  2219.8
   370.9 2218.54   382.9  2223.6     411 2223.13   415.2 2225.77   427.1 2238.57
   443.1 2247.59   451.2 2250.43     465 2257.85   482.9 2265.59   509.5 2275.27
#Mann= 7 ,-1,0
       0      .1       0      70     .06       0     170      .1       0
     235    .045       0   280.1      .1       0     370     .06       0
  468.96      .1       0
Bank Sta=235,280.1
XS Rating Curve= 0 ,0
Exp/Cntr=0.3,0.1

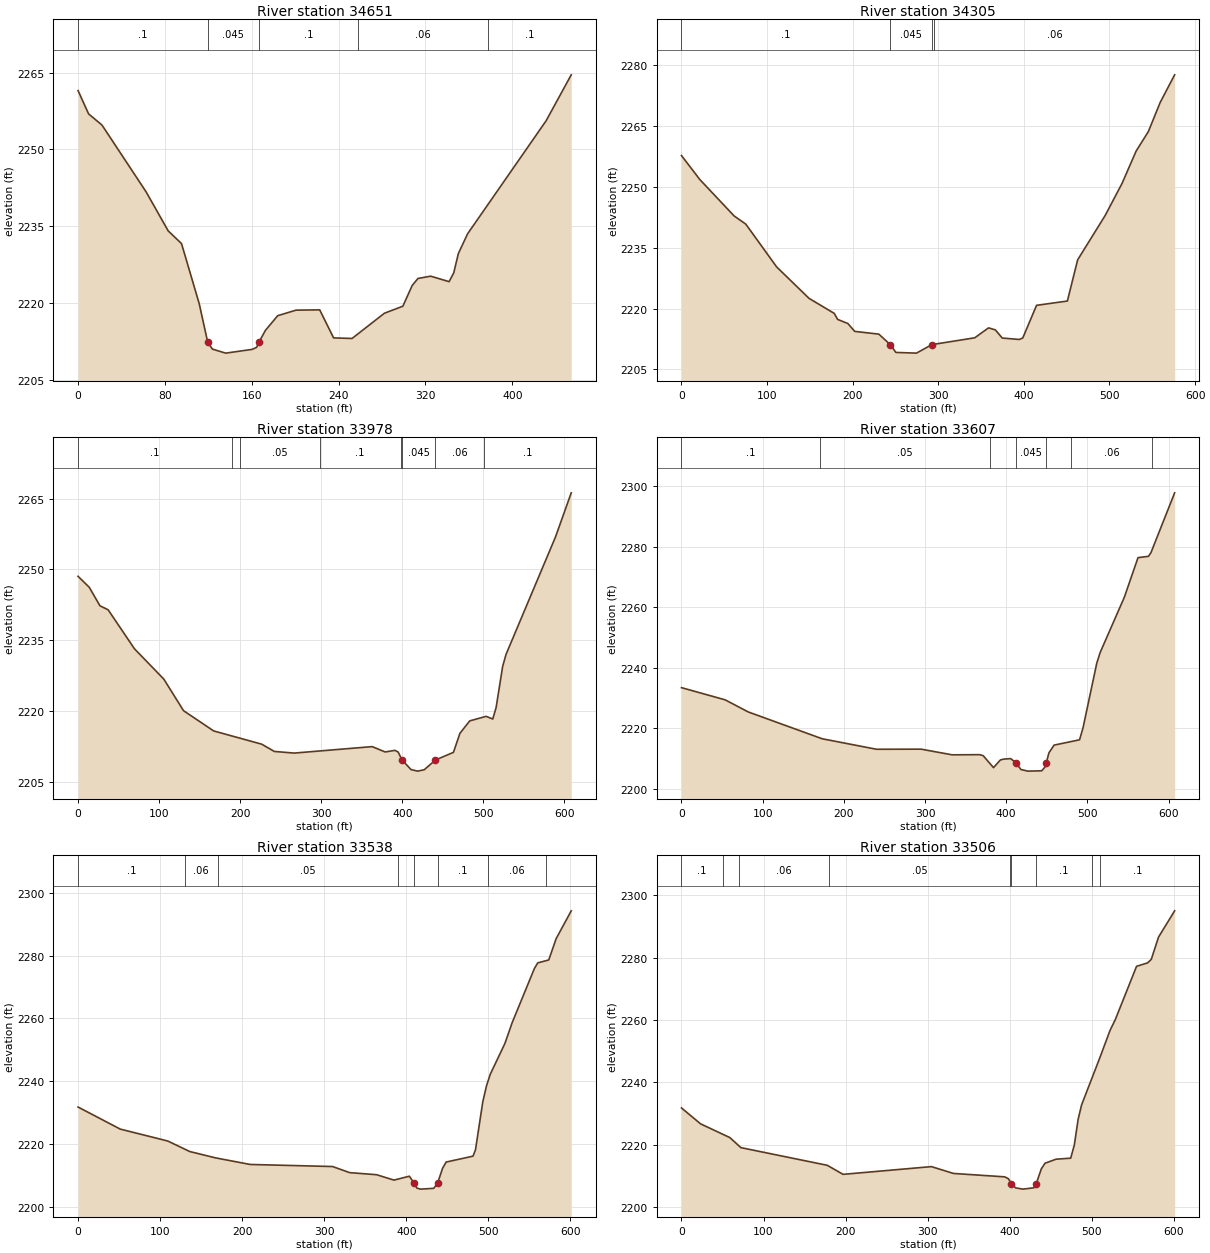
Type RM Length L Ch R = 1 ,34651   ,345.7,345.7,345.7
XS GIS Cut Line= 3
2195422.49666418625454.7468074742195459.65485821625260.641194032
2195547.57155524625019.468777604
#Sta/Elev= 30
       0 2261.48     9.7 2256.94      22 2254.77    62.7 2241.73      83 2234.13
    95.3 2231.64   111.6 2219.93  119.472212.377   123.8 2211.06     136 2210.28
   160.4 2211.01   164.5 2211.41  166.512212.375   172.6 2214.72   183.9 2217.58
   200.7 2218.66   222.6 2218.72   235.4 2213.25   252.4 2213.14   282.2 2218.06
   299.2 2219.43   307.8 2223.47   313.1 2224.84   324.8 2225.29   341.8 2224.22
   346.1 2225.95   350.3 2229.69   358.8 2233.54   431.2 2255.61   454.3 2264.56
#Mann= 5 ,-1,0
       0      .1       0  119.47    .045       0  166.51      .1       0
  257.63     .06       0  377.63      .1       0
Bank Sta=119.47,166.51
XS Rating Curve= 0 ,0
Exp/Cntr=0.3,0.1

Type RM Length L Ch R = 1 ,34305   ,327,327,327
XS GIS Cut Line= 4
2195718.02959174625579.8810381762195798.69099622625424.238609825
2195782.78593055625145.8999605822195793.01061562625024.339815811
#Sta/Elev= 30
       0 2257.76    21.4 2251.85    61.6 2242.84    75.1 2240.85   111.2 2230.28
     149 2222.53   178.4 2218.83   182.4 2217.34   194.4 2216.32   202.4 2214.38
   230.5 2213.71  243.942211.115   250.5 2209.19   274.5 2209.02   292.52211.116
   342.6  2212.8   358.7 2215.25   366.7 2214.75   374.7 2212.74   394.7 2212.39
   398.7 2212.76   414.8 2220.81   450.8 2221.87   462.8 2232.03     495 2242.99
   514.7  2250.9   531.1 2258.85   545.4 2263.67   559.2 2270.85   576.1 2277.67
#Mann= 4 ,-1,0
       0      .1       0  243.94    .045       0   292.5      .1       0
   295.3     .06       0
Bank Sta=243.94,292.5
XS Rating Curve= 0 ,0
Exp/Cntr(USF)=0,0
Exp/Cntr=0.3,0.1

Type RM Length L Ch R = 1 ,33978   ,370.8,370.8,370.8
XS GIS Cut Line= 4
2196019.08976337625673.0392799642196130.42522307 625485.58672027
2196109.97585292625214.0645277442196132.69737531625098.184763569
#Sta/Elev= 30
       0 2248.53    13.8 2246.21      27 2242.29    37.1 2241.44    69.6 2233.18
   105.8 2226.76   130.1 2220.08   167.3 2215.79   226.5 2212.99   242.1 2211.45
   266.6  2211.1   362.8 2212.47   378.9 2211.34   390.9 2211.68   394.9 2211.32
  399.662209.631   410.8 2207.61     419 2207.28     427 2207.57  440.872209.629
   463.1 2211.26   471.1 2215.29   483.2 2217.92   503.4 2218.88   511.6 2218.31
   515.7 2220.71   523.8 2229.45   527.9 2231.97     589 2256.87   608.4 2266.21
#Mann= 8 ,-1,0
       0      .1       0     190     .06       0     200     .05       0
  298.02      .1       0  398.02     .06       0  399.66    .045       0
  440.87     .06       0  500.31      .1       0
Bank Sta=399.66,440.87
XS Rating Curve= 0 ,0
Exp/Cntr(USF)=0,0
Exp/Cntr=0.3,0.1

Type RM Length L Ch R = 1 ,33607   ,69,69,69
XS GIS Cut Line= 2
2196334.02280845625755.8693091212196534.91586963625182.657677763
#Sta/Elev= 30
       0 2233.43    53.7 2229.41    82.3 2225.39   173.3 2216.53   240.2 2213.06
   295.3 2213.09   333.3 2211.22   367.4 2211.27   371.6 2210.94   384.3 2206.99
   392.8 2209.53     397  2209.8   405.5 2209.97   411.8 2208.59   418.2 2206.35
   426.7 2205.83   443.7 2205.94   447.9 2207.25  449.272208.586   452.6 2211.87
   458.9 2214.43   490.3 2216.19   494.5 2220.07   511.5 2241.52   515.7 2245.07
   545.4 2263.29   562.3 2276.42   575.1 2276.85   578.2 2278.05   607.4 2297.85
#Mann= 7 ,-1,0
       0      .1       0     170     .05       0     380      .1       0
   411.8    .045       0  449.27      .1       0     480     .06       0
     580      .1       0
Bank Sta=411.8,449.27
XS Rating Curve= 0 ,0
Exp/Cntr=0.3,0.1

Type RM Length L Ch R = 1 ,33538   ,32,32,32
XS GIS Cut Line= 2
2196353.16040454625751.1234594442196620.13829259625212.623378869
#Sta/Elev= 30
       0 2231.84    51.3 2224.84   109.3 2221.04   136.1  2217.7   167.4 2215.69
   209.7 2213.59   310.2 2212.93     331 2210.99   363.8 2210.33     385 2208.62
   403.7 2209.85   409.6 2207.66   412.9 2206.08   417.4 2205.75   433.5    2206
   438.1 2207.61   444.2 2212.37   448.6 2214.36   481.3 2216.23   484.3 2218.21
   493.2 2233.47   497.7 2238.56   502.3 2242.24   520.1    2252     529 2258.64
   556.1 2275.86   560.2 2277.66   573.6 2278.58   582.6 2285.34     601  2294.2
#Mann= 8 ,-1,0
       0      .1       0     130     .06       0     170     .05       0
     390      .1       0   409.6    .045       0   438.1      .1       0
     500     .06       0     570      .1       0
Bank Sta=409.6,438.1
XS Rating Curve= 0 ,0
Exp/Cntr(USF)=0,0
Exp/Cntr=0.3,0.1

Type RM Length L Ch R = 1 ,33506   ,106,106,106
XS GIS Cut Line= 2
2196385.24957777625758.0777535862196652.22746582625219.577673011
#Sta/Elev= 30
       0 2231.83    23.3 2226.71      59 2222.31    72.4 2219.09   177.7 2213.42
   196.9 2210.52   304.6    2213   331.4 2210.81   393.9 2209.72   398.4 2209.12
  402.04 2207.53   407.3 2206.17   416.2 2205.78   429.6 2206.21  432.36 2207.53
   438.5 2212.26     443 2214.08   456.5 2215.38   474.3  2215.7   478.7 2219.87
   483.4 2228.16   487.6 2232.79     510 2248.02   522.2 2256.64   528.9 2260.29
   554.6 2277.24     568 2278.34   572.5 2279.45   581.4 2286.63     601 2295.04
#Mann= 9 ,-1,0
       0      .1       0      50     .05       0      70     .06       0
     180     .05       0     400      .1       0  402.04    .045       0
  432.36      .1       0     500     .06       0     510      .1       0
Bank Sta=402.04,432.36
XS Rating Curve= 0 ,0
Exp/Cntr(USF)=0,0
Exp/Cntr=0.3,0.1

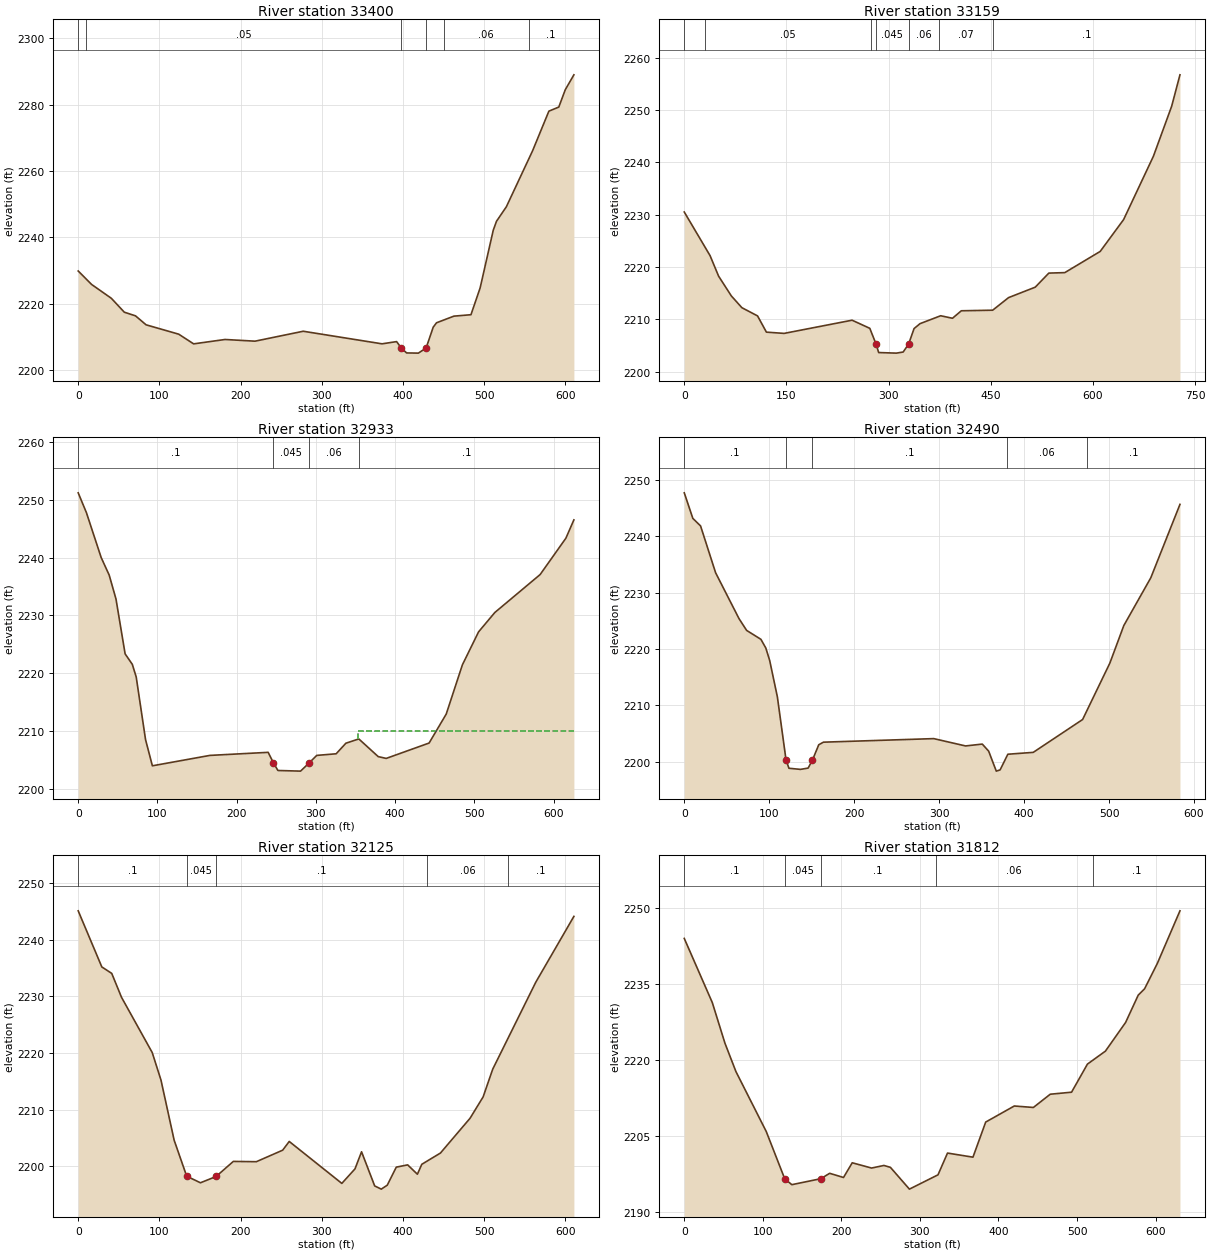
Type RM Length L Ch R = 1 ,33400   ,241.3,241.3,241.3
XS GIS Cut Line= 3
2196476.18508103625807.9409167212196679.54270639625401.225665991
2196699.99207654625246.719313759
#Sta/Elev= 30
       0  2229.9    16.5 2225.85    40.8 2221.68    56.8 2217.49    70.6 2216.39
    83.6 2213.69   123.8 2210.87   142.2 2207.95   180.9 2209.27   217.8 2208.76
   277.2 2211.75   374.3 2207.96   392.2 2208.63  398.052206.688   404.5 2205.22
     419 2205.16  428.562206.692   437.3 2212.97   441.4  2214.3   462.8  2216.3
   483.8 2216.73   495.1 2224.79   511.3 2242.21   515.3 2244.89   527.4 2249.24
   559.7  2266.1   579.8 2278.05     592 2279.28     600 2284.51   610.6 2288.99
#Mann= 6 ,-1,0
       0      .1       0      10     .05       0  398.05    .045       0
  428.56     .05       0     450     .06       0  554.72      .1       0
Bank Sta=398.05,428.56
XS Rating Curve= 0 ,0
Exp/Cntr(USF)=0,0
Exp/Cntr=0.3,0.1

Type RM Length L Ch R = 1 ,33159   ,225.9,225.9,225.9
XS GIS Cut Line= 3
2196486.44934476625818.3788164162196552.43708955625738.646489536
2197128.17569998625497.165896992
#Sta/Elev= 30
       0 2230.51    37.9 2222.17    50.4 2218.26    69.1 2214.48    84.6 2212.23
   107.6 2210.66   120.6 2207.56   146.6 2207.32   246.4 2209.84   272.4 2208.29
   281.7 2205.25   285.4 2203.66   311.4 2203.55   321.4 2203.76  329.352205.266
   337.4 2208.24   346.1 2209.18   376.5 2210.69   393.8 2210.21   406.8 2211.64
   452.8 2211.75   476.2 2214.16   515.3 2216.15   535.3 2218.84   558.7 2218.93
   610.7 2222.98   645.1 2229.07   688.8 2241.16   715.6 2250.71   727.8 2256.72
#Mann= 7 ,-1,0
       0      .1       0      30     .05       0   273.5     .06       0
   281.7    .045       0  329.35     .06       0   373.5     .07       0
   453.5      .1       0
Bank Sta=281.7,329.35
XS Rating Curve= 0 ,0
Exp/Cntr=0.3,0.1

Type RM Length L Ch R = 1 ,32933   ,442.8,442.8,442.8
XS GIS Cut Line= 3
2196584.57018208625988.093459697 2196718.4156403625892.675397007
2197169.89346716625798.968898497
#Sta/Elev= 30
       0 2251.22    10.4 2247.78      29 2240.02    39.1 2236.99    47.7 2232.84
    59.2 2223.36    68.3 2221.54    73.2 2219.36      85 2208.51    93.6 2203.99
   166.2 2205.79   239.7 2206.32   246.22204.552     252 2203.18   280.6 2203.07
  291.73 2204.53     301 2205.79   325.5 2206.07   337.8  2207.9   354.1 2208.64
   378.6 2205.58   388.7 2205.27   442.8 2207.93   464.4 2212.94   484.8 2221.46
   505.2 2227.16   525.7 2230.51   582.9 2237.08   615.4 2243.37   625.5 2246.54
#Mann= 4 ,-1,0
       0      .1       0   246.2    .045       0  291.73     .06       0
  354.38      .1       0
#XS Ineff= 2 , 0
                        353.5878            2210
Permanent Ineff=
       F       F
Bank Sta=246.2,291.73
XS Rating Curve= 0 ,0
Exp/Cntr=0.3,0.1

Type RM Length L Ch R = 1 ,32490   ,365.2,365.2,365.2
XS GIS Cut Line= 3
2196571.22275738626184.2735336742196920.03282984626368.078005962
2197104.57503135626409.762553732
#Sta/Elev= 30
       0 2247.75    10.1 2243.21    19.2 2241.87    36.9 2233.56    64.4 2225.43
    73.4 2223.33    90.2 2221.75      96  2220.2   100.5 2218.02   109.6 2211.53
  119.782200.353   123.2 2198.86   136.7 2198.66   145.8 2198.89  150.942200.322
   158.3 2203.03   163.8 2203.49   293.7 2204.12   331.1 2202.82   350.8 2203.15
   358.3  2201.9   367.3 2198.35   371.8 2198.57   380.9 2201.35   410.8 2201.68
   468.9 2207.51     501 2217.53   517.4 2224.19   549.2 2232.68   583.5  2245.7
#Mann= 5 ,-1,0
       0      .1       0  119.78    .045       0  150.94      .1       0
     380     .06       0  474.27      .1       0
Bank Sta=119.78,150.94
XS Rating Curve= 0 ,0
Exp/Cntr=0.3,0.1

Type RM Length L Ch R = 1 ,32125   ,313.5,313.5,313.5
XS GIS Cut Line= 2
2196479.38686715626581.606740297     2197082.587      626677.156
#Sta/Elev= 30
       0 2245.11    29.1 2235.21    41.3 2234.07    53.4 2229.84    91.2  2220.1
     102 2215.24   118.2 2204.64  133.642198.286   150.6 2197.12   169.9 2198.23
   191.1 2200.89   219.5 2200.84   251.9 2202.87     260 2204.41   324.8 2197.01
     341 2199.57   349.1 2202.59   365.3 2196.56   373.4    2196   380.8  2196.7
   391.9 2199.88   405.9 2200.28   417.9 2198.63   423.3 2200.38   446.3 2202.37
   482.8 2208.51   498.9 2212.28   510.7 2217.17   563.7  2232.5   610.7 2244.13
#Mann= 5 ,-1,0
       0      .1       0  133.64    .045       0   169.9      .1       0
     430     .06       0     530      .1       0
Bank Sta=133.64,169.9
XS Rating Curve= 0 ,0
Exp/Cntr=0.3,0.1

Type RM Length L Ch R = 1 ,31812   ,385.6,385.6,385.6
XS GIS Cut Line= 2
2196484.88097231626940.9002291662197108.58676184 626845.46983514
#Sta/Elev= 30
       0 2244.04    35.7 2231.35    51.8 2223.31    65.8  2217.7   104.4 2205.84
  127.832196.523   136.9 2195.34   173.82196.521   185.1 2197.59   202.7 2196.76
   213.8 2199.67   238.4 2198.63   254.2 2199.14   262.4 2198.77   286.6 2194.46
     323 2197.29   335.1 2201.59   367.5 2200.78   383.7 2207.72   420.1  2210.9
   444.4 2210.61   465.9 2213.23     493 2213.63   513.2 2219.18   536.1 2221.75
   561.8 2227.42   577.9 2232.83     586 2234.09   602.2  2239.1     631  2249.5
#Mann= 5 ,-1,0
       0      .1       0  127.83    .045       0   173.8      .1       0
     320     .06       0     520      .1       0
Bank Sta=127.83,173.8
XS Rating Curve= 0 ,0
Exp/Cntr(USF)=0,0
Exp/Cntr=0.3,0.1

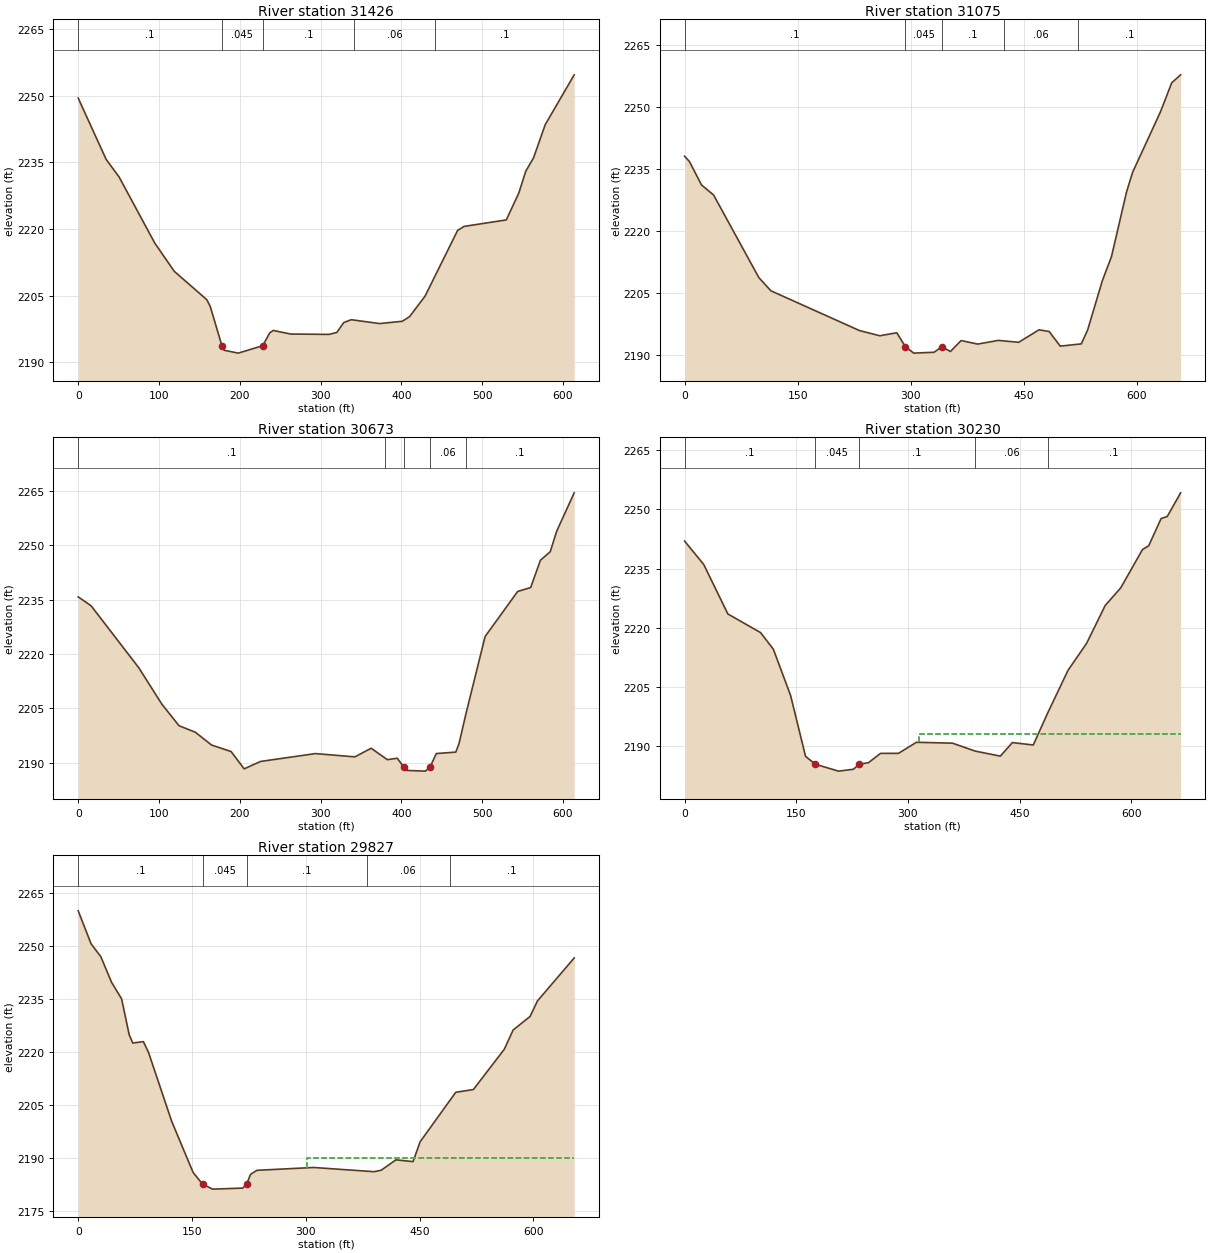
Type RM Length L Ch R = 1 ,31426   ,350.9,350.9,350.9
XS GIS Cut Line= 4
2196573.76326865627293.8561626872196731.45021791627279.032473126
2196900.68483199627209.014193334 2197171.8867194627181.772759688
#Sta/Elev= 30
       0 2249.49    34.6 2235.69    50.6 2231.73    94.8 2216.83   118.9 2210.48
   159.2 2204.08   163.5 2202.55   177.92193.722   180.8 2192.68   198.1 2192.04
   228.4 2193.71   237.1 2196.59   241.4 2197.15   263.1 2196.34   310.4 2196.26
   320.2  2196.7   328.8 2198.93     338 2199.57   373.2  2198.7   401.3 2199.22
   410.3 2200.27   429.5  2204.9   469.7 2219.67   477.7 2220.59     530 2222.05
   545.5  2228.1   554.1 2233.02   563.8 2236.06   578.2 2243.51   614.1 2254.74
#Mann= 5 ,-1,0
       0      .1       0   177.9    .045       0   228.4      .1       0
  341.53     .06       0  441.53      .1       0
Bank Sta=177.9,228.4
XS Rating Curve= 0 ,0
Exp/Cntr=0.3,0.1

Type RM Length L Ch R = 1 ,31075   ,402,402,402
XS GIS Cut Line= 4
2196609.75066716627658.2511940322196753.41817016627664.500144771
2197046.10257527627514.6186694412197231.94887911 627511.81023432
#Sta/Elev= 30
       0 2238.15     6.4 2236.88    22.4 2231.22    38.5 2228.77    98.5  2208.8
   114.5  2205.6   232.3 2195.96   259.2 2194.71   281.7 2195.44  293.072192.072
   304.2 2190.51   331.2 2190.72   341.5 2192.05   352.9  2190.9   367.1 2193.55
   389.1  2192.7   416.5 2193.59   443.5 2193.13   470.5 2196.15     484 2195.74
   498.7  2192.2   526.7 2192.75   535.2 2196.19   554.5 2207.99   566.7 2213.86
   586.7  2229.5   594.7 2234.24   631.7 2248.89   646.7 2255.93   658.5 2257.86
#Mann= 5 ,-1,0
       0      .1       0  293.07    .045       0   341.5      .1       0
   423.8     .06       0  522.63      .1       0
Bank Sta=293.07,341.5
XS Rating Curve= 0 ,0
Exp/Cntr=0.3,0.1

Type RM Length L Ch R = 1 ,30673   ,442.7,442.7,442.7
XS GIS Cut Line= 2
2196620.31685074627869.3871613442197229.64673941627945.219192394
#Sta/Elev= 30
       0 2235.78      16 2233.31      75 2216.21   103.6 2206.15   124.8 2200.21
     145 2198.42   165.1 2194.88   189.3 2193.08   205.4 2188.31   225.7 2190.35
   293.6 2192.52   342.5 2191.62   362.6 2193.99   382.8 2190.84   394.9 2191.24
   402.9 2188.88     407 2187.87   429.9 2187.68  435.682188.883   443.3 2192.53
   467.4 2192.93   471.5 2195.35     480 2203.53   503.7 2224.84     544 2237.27
   560.1 2238.36   572.2  2245.9   584.3 2248.24   592.4 2253.96     614  2264.5
#Mann= 5 ,-1,0
       0      .1       0     380     .06       0   402.9    .045       0
  435.68     .06       0     480      .1       0
Bank Sta=402.9,435.68
XS Rating Curve= 0 ,0
Exp/Cntr=0.3,0.1

Type RM Length L Ch R = 1 ,30230   ,403.5,403.5,403.5
XS GIS Cut Line= 3
2196614.78614238628274.0946367292197058.91635118628326.346141495
2197269.29107851 628264.44490508
#Sta/Elev= 30
       0 2241.96    25.7 2236.04    58.1  2223.5   102.1 2218.77   119.3 2214.54
   142.4 2202.85   162.5 2187.41  175.572185.414   206.8 2183.66   226.9 2184.13
  234.472185.413   247.1  2185.8   263.2 2188.16   287.4 2188.17   311.5 2190.97
   359.9 2190.75   390.6 2188.73   424.3 2187.46   440.4  2190.9   468.5 2190.28
   487.8 2198.36   515.2 2209.21   540.2 2216.05   565.1 2225.63   586.1 2230.13
   615.3 2239.83   623.6 2240.78   640.3 2247.68   648.6 2248.22   666.5  2254.2
#Mann= 5 ,-1,0
       0      .1       0  175.57    .045       0  234.47      .1       0
   390.6     .06       0   487.8      .1       0
#XS Ineff= 2 , 0
                           315.6            2193
Permanent Ineff=
       F       F
Bank Sta=175.57,234.47
XS Rating Curve= 0 ,0
Exp/Cntr=0.3,0.1

Type RM Length L Ch R = 1 ,29827   ,338.9,338.9,338.9
XS GIS Cut Line= 2
 2196778.6465171628774.8165505912197337.93679066628436.379474635
#Sta/Elev= 30
       0    2260    16.9 2250.68    29.8 2247.01    43.9 2239.79    57.2 2235.05
    67.2  2224.9    71.9 2222.56    85.9 2222.95    92.6 2219.94   123.3 2200.33
   151.4 2185.91  163.882182.584   177.1 2181.18   216.9 2181.47  221.912182.583
   227.2 2185.38   235.6 2186.51   310.4 2187.31   389.8 2186.12   399.2 2186.52
   418.8 2189.48   441.3 2188.97   450.6 2194.58   497.6 2208.61   520.8 2209.38
   561.6 2220.81   573.2 2226.24   595.6  2230.1   605.2 2234.46   653.7 2246.66
#Mann= 5 ,-1,0
       0      .1       0  163.88    .045       0  221.91      .1       0
     380     .06       0     490      .1       0
#XS Ineff= 2 , 0
                          301.01            2190
Permanent Ineff=
       F       F
Bank Sta=163.88,221.91
XS Rating Curve= 0 ,0
Exp/Cntr(USF)=0,0
Exp/Cntr=0.3,0.1