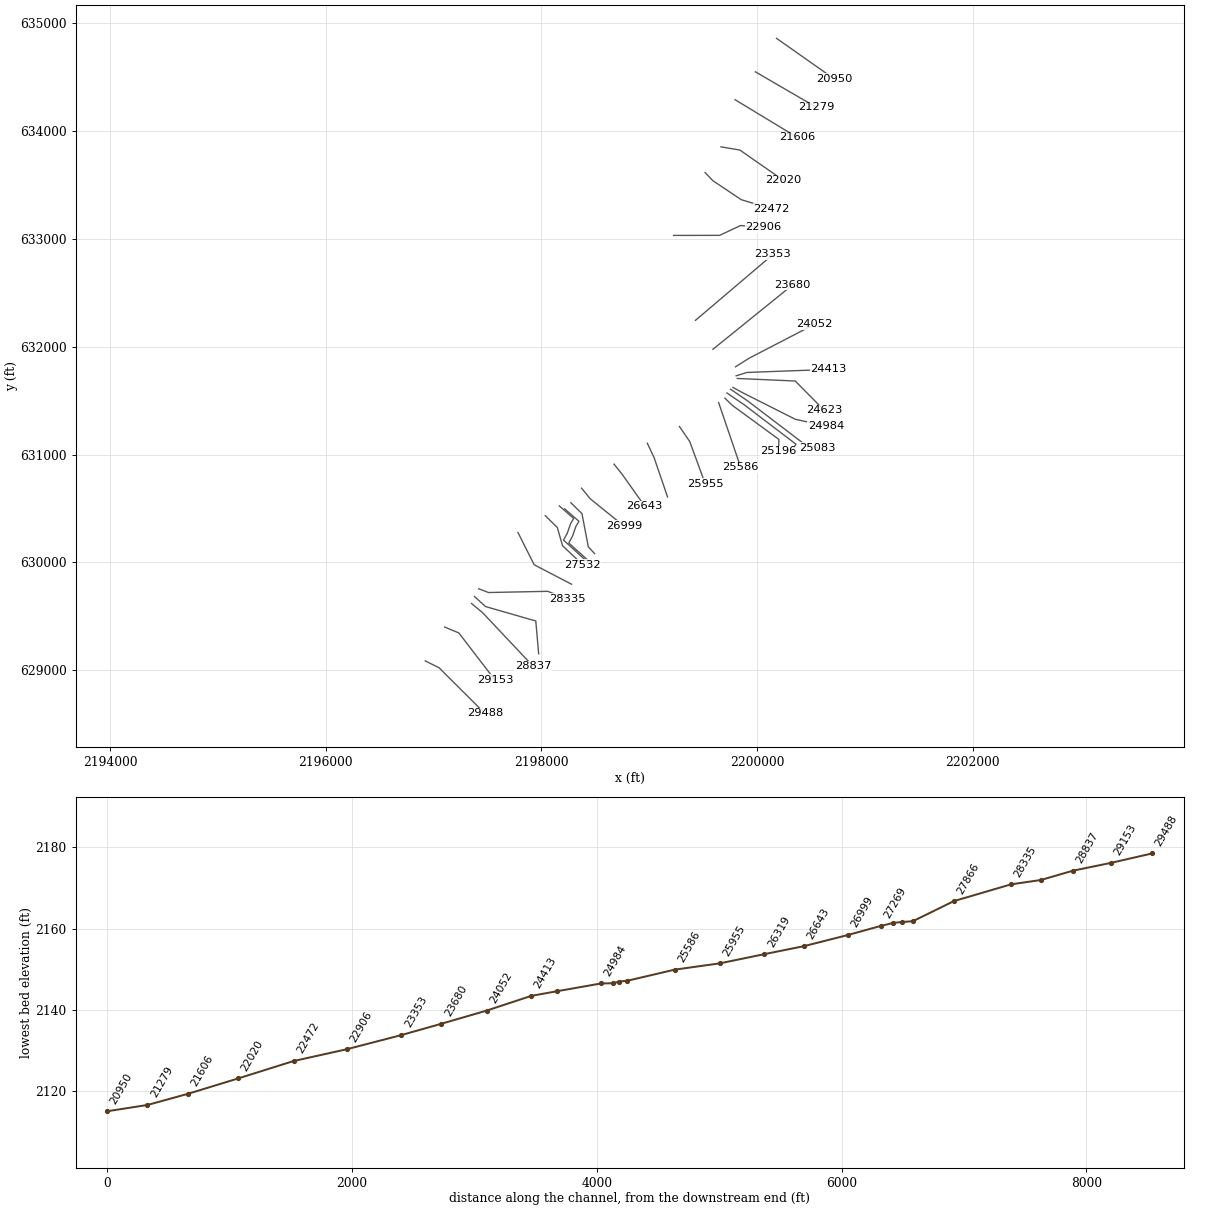
HEC-RAS study LFRFBUCRV.prj: LFRFBUCRV

--- LFRFBUCRV.g01 (geometry) --- (continued)

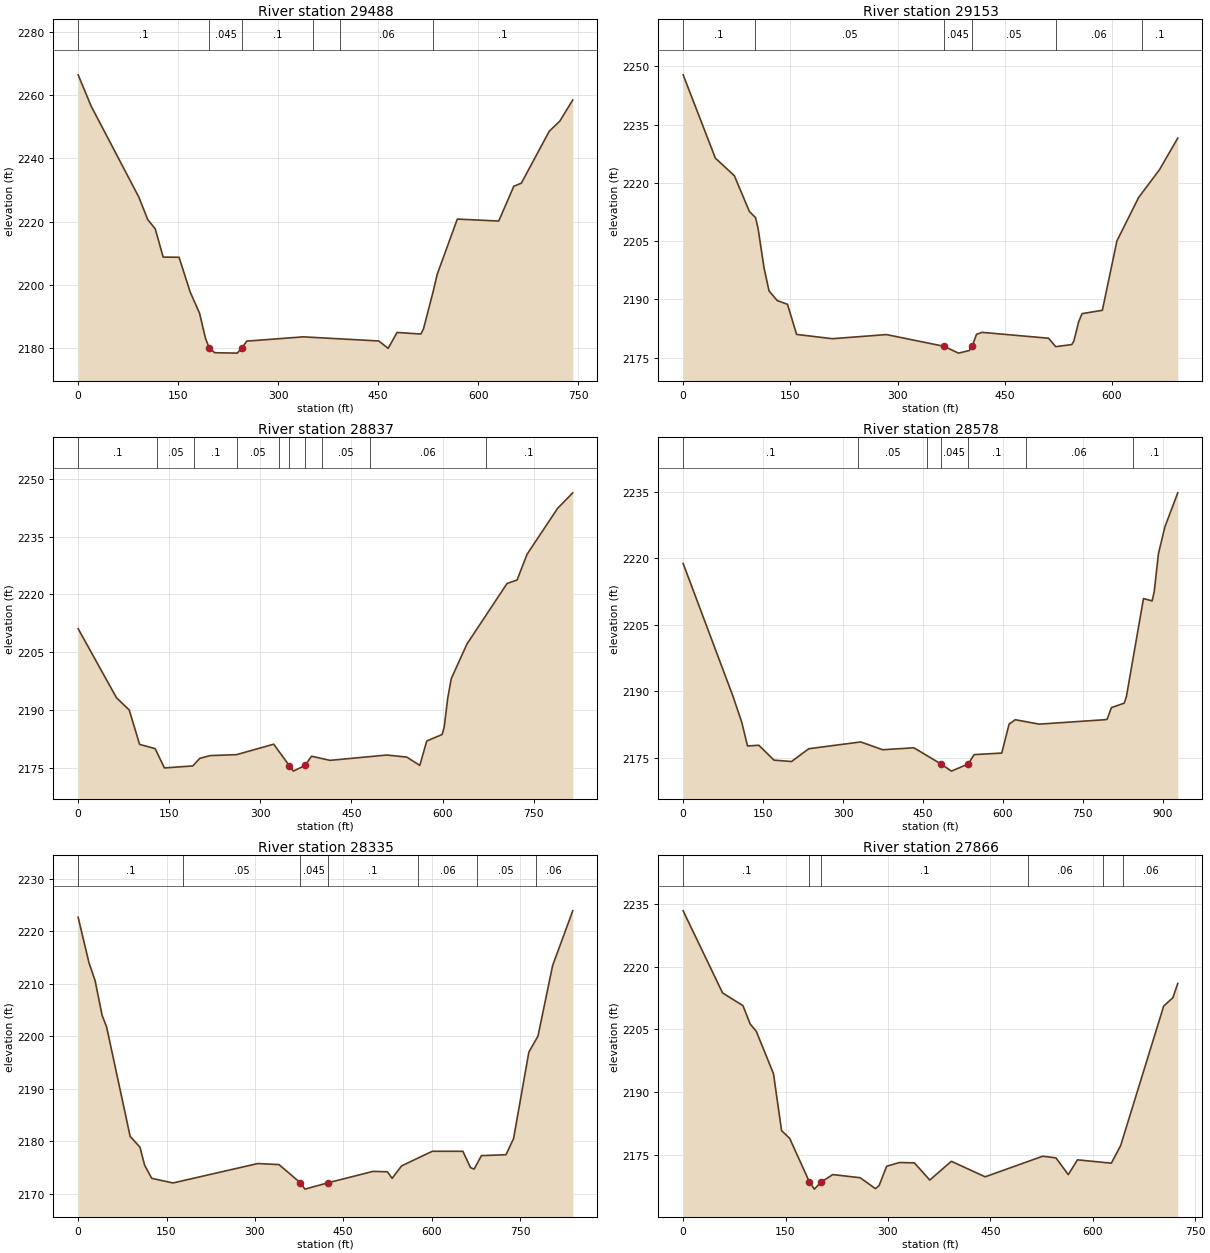
Type RM Length L Ch R = 1 ,29488   ,334.8,334.8,334.8
XS GIS Cut Line= 3
2196922.70808372629086.6375513412197050.62137015629023.146240739
2197474.76714582628600.337161344
#Sta/Elev= 30
       0 2266.41    19.5 2256.52      91  2227.8   104.3 2220.71   115.6 2217.76
   127.5 2208.84   151.3 2208.79   167.9 2197.88   182.1 2191.09   190.9 2183.23
  196.472180.206   204.7 2178.64   238.6 2178.51  245.772180.186   252.8  2182.3
   337.6 2183.65   450.8 2182.35   464.9 2180.02   478.2 2185.04   513.9 2184.54
   517.8 2186.13   532.8  2198.3   538.4 2203.38   568.6 2220.85   630.7 2220.23
   653.3 2231.21   664.6 2232.19   706.5  2248.6   722.3 2251.79   741.7 2258.46
#Mann= 6 ,-1,0
       0      .1       0  196.47    .045       0  245.77      .1       0
   352.8     .05       0   392.8     .06       0   532.8      .1       0
Bank Sta=196.47,245.77
XS Rating Curve= 0 ,0
Exp/Cntr=0.3,0.1

Type RM Length L Ch R = 1 ,29153   ,316,316,316
XS GIS Cut Line= 3
2197102.56565746629400.7345901542197233.94175926629346.017925813
2197568.55384209 628909.68857119
#Sta/Elev= 30
       0 2247.78    45.1 2226.35    71.7 2221.83    92.7 2212.63   101.4 2211.03
   104.9 2208.24   113.3 2198.02   120.2  2192.2   131.7 2189.72     146 2188.76
   158.8 2181.01   208.9 2179.91   284.5 2180.97   365.2 2177.95   385.3  2176.2
   400.5 2176.87  404.562178.013   410.5 2181.02   418.4 2181.54   511.4 2180.03
   521.4 2177.86   543.9  2178.4   546.8 2179.31   553.5 2184.24   558.2 2186.35
   586.7 2187.22   607.1 2205.08   637.4 2216.21   666.6 2223.37   692.2  2231.5
#Mann= 6 ,-1,0
       0      .1       0     100     .05       0   365.2    .045       0
  404.56     .05       0  522.32     .06       0  642.32      .1       0
Bank Sta=365.2,404.56
XS Rating Curve= 0 ,0
Exp/Cntr=0.3,0.1

Type RM Length L Ch R = 1 ,28837   ,259.2,259.2,259.2
XS GIS Cut Line= 3
2197351.43382313629618.8448265692197452.46005001629535.765201042
2197921.33797239629038.475377911
#Sta/Elev= 30
       0 2211.14    63.1 2193.25    84.1 2190.08   101.2 2181.16   126.8 2180.07
     142 2175.07   188.7 2175.58   200.3 2177.56   217.8 2178.27   260.8 2178.51
     322 2181.22   347.5 2175.69   354.3 2174.24  373.522175.704   384.3  2178.1
   414.7 2177.03   508.2 2178.41   541.2 2177.87   562.5 2175.71   573.9 2182.04
   599.3 2183.74   602.7  2185.7   608.5 2193.17   614.3  2198.2   640.1 2207.16
   706.1 2222.84   722.6 2223.74   739.1 2230.42   789.3  2242.3   814.3 2246.33
#Mann= 10 ,-1,0
       0      .1       0     130     .05       0   190.8      .1       0
   260.8     .05       0   330.8      .1       0   347.5    .045       0
  373.52      .1       0   400.8     .05       0   480.8     .06       0
   670.8      .1       0
Bank Sta=347.5,373.52
XS Rating Curve= 0 ,0
Exp/Cntr=0.3,0.1

Type RM Length L Ch R = 1 ,28578   ,243,243,243
XS GIS Cut Line= 4
2197378.83553095629683.7910536892197481.08238169629590.746419513
2197947.32802108629456.8030450412197973.91220227629153.129898337
#Sta/Elev= 30
       0 2218.85    93.8 2188.79     110    2183   120.8 2177.65     142 2177.81
   170.6 2174.45   203.4 2174.14   235.8 2177.03   333.2 2178.56   374.5  2176.8
     433 2177.24  483.082173.641   503.5 2171.97   535.1  2173.6   546.1  2175.7
   597.9 2176.05   611.7 2182.59   623.3 2183.58   668.1 2182.58   791.6 2183.58
   795.6 2183.67   803.7 2186.31   827.8 2187.32   831.8 2188.77   863.9 2210.94
     880  2210.4     884 2212.43     892 2221.08     904  2227.1   928.2 2234.81
#Mann= 7 ,-1,0
       0      .1       0  328.25     .05       0  458.25      .1       0
  483.08    .045       0   535.1      .1       0  643.35     .06       0
  843.35      .1       0
Bank Sta=483.08,535.1
XS Rating Curve= 0 ,0
Exp/Cntr(USF)=0,0
Exp/Cntr=0.3,0.1

Type RM Length L Ch R = 1 ,28335   ,469.1,469.1,469.1
XS GIS Cut Line= 4
2197417.72912253629755.7495470182197508.89338911629720.836948216
2198057.75461988629731.8470735382198237.97741329629662.852798958
#Sta/Elev= 30
       0 2222.66    18.4 2214.01    28.7 2210.64    40.7 2203.99    48.4 2201.75
    88.3 2180.94   104.9 2178.91   112.9 2175.45   124.9 2172.97   160.9 2172.08
   304.9 2175.78     341 2175.58     377 2172.14     385 2170.91  424.032172.115
   500.7 2174.29     525 2174.21     533 2172.96     549 2175.33     601 2178.11
   653.1 2178.11     666 2175.02   672.2 2174.72   684.6 2177.29   726.3 2177.46
   739.1 2180.52   765.1    2197   780.6 2200.05   805.4 2213.46   839.6 2223.89
#Mann= 7 ,-1,0
       0      .1       0  177.62     .05       0     377    .045       0
  424.03      .1       0  577.62     .06       0  676.59     .05       0
  776.59     .06       0
Bank Sta=377,424.03
XS Rating Curve= 0 ,0
Exp/Cntr=0.3,0.1

Type RM Length L Ch R = 1 ,27866   ,333.6,333.6,333.6
XS GIS Cut Line= 3
2197782.23523055630276.8815365042197932.60807696629977.829288887
2198278.40803383 629797.87571082
#Sta/Elev= 30
       0 2233.37    57.8 2213.72    87.6 2210.69    98.2 2206.28   107.1 2204.55
   132.3 2194.43   144.2 2180.78   156.1 2178.91  184.982168.489   192.2 2166.77
   202.1 2168.45   219.1 2170.25   259.3  2169.5   281.7 2166.89   287.2 2167.66
   298.1 2172.24     317 2173.14   338.8 2173.05   361.3 2168.94   392.9 2173.43
   442.5 2169.72   526.8 2174.65   546.2 2174.24   564.2 2170.24   577.7 2173.78
   627.3 2172.98   640.9 2177.17     704 2210.58   717.5 2212.59   724.6    2216
#Mann= 6 ,-1,0
       0      .1       0  184.98    .045       0   202.1      .1       0
  504.73     .06       0  614.73      .1       0  644.73     .06       0
Bank Sta=184.98,202.1
XS Rating Curve= 0 ,0
Exp/Cntr=0.3,0.1

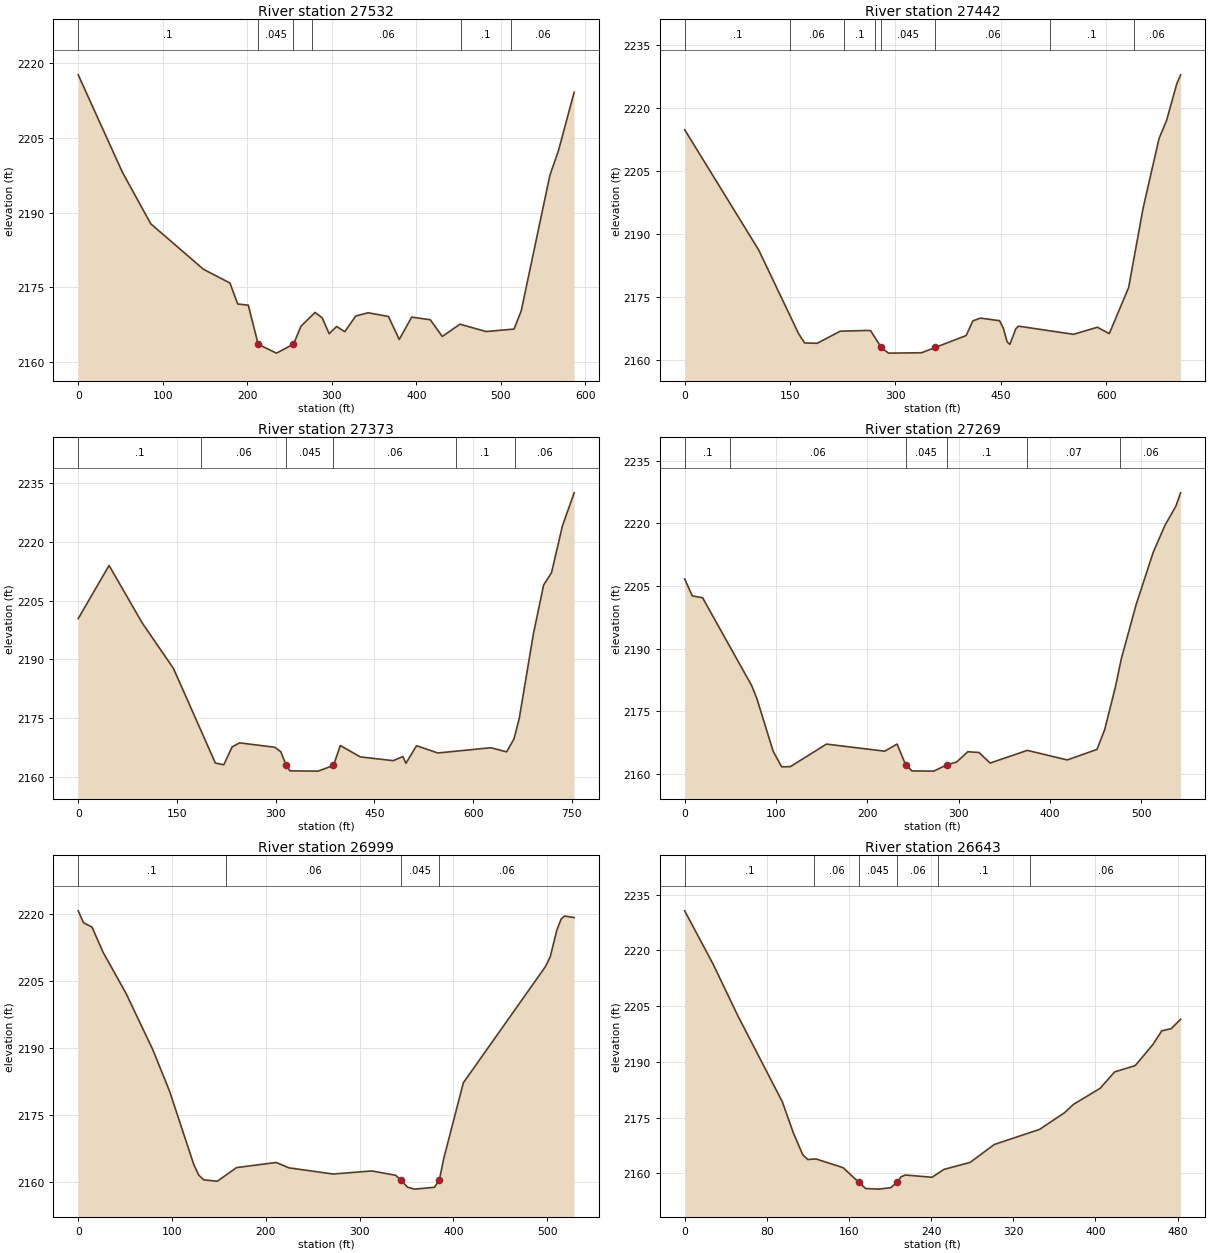
Type RM Length L Ch R = 1 ,27532   ,90.2,90.2,90.2
XS GIS Cut Line= 4
 2198034.8863811630433.6602872382198146.69331239630324.089494577
2198195.14298261630154.8883385642198379.99710901629980.469525757
#Sta/Elev= 30
       0 2217.63    52.2 2198.13    85.8 2187.77   148.3 2178.63   179.5 2175.89
   188.7 2171.69   201.2 2171.45  212.96  2163.6   234.5 2161.84  254.63 2163.62
   263.6 2167.25   280.2    2170   288.6 2168.93   296.9 2165.73   305.7 2167.19
   315.4 2166.13   328.3 2169.28     343 2169.93     367 2169.19   379.8 2164.58
   394.5 2169.06   416.5 2168.53   430.7 2165.18   451.6 2167.64   482.5 2166.17
   515.6 2166.66   524.1 2170.32     558 2197.49   568.2 2202.46   586.7 2214.15
#Mann= 6 ,-1,0
       0      .1       0  212.96    .045       0  254.63      .1       0
  276.55     .06       0  452.55      .1       0  512.55     .06       0
Bank Sta=212.96,254.63
XS Rating Curve= 0 ,0
Exp/Cntr(USF)=0,0
Exp/Cntr=0.3,0.1

Type RM Length L Ch R = 1 ,27442   ,68.8,68.8,68.8
XS GIS Cut Line= 6
2198165.61224135630523.4260725892198298.89034101630407.474869676
2198270.44924681630360.5891627372198239.05386051630270.025548395
2198204.19963819630206.6751515042198430.92833171630000.581296177
#Sta/Elev= 30
       0 2214.83   105.5 2186.16   162.2 2166.27   170.7 2164.07   188.7 2163.98
   221.4 2166.86   260.5 2167.04   264.7 2166.99   279.82163.005   290.1 2161.64
   337.4 2161.73   356.6 2162.98   400.7 2165.82   410.4 2169.33   421.2 2169.98
   448.3 2169.36   453.7 2167.59   459.1 2164.32     463 2163.73   471.5 2167.46
   475.3 2168.06   553.6 2166.12   587.6  2167.8   604.6 2166.29   632.1 2177.27
   652.7 2196.15   675.4 2212.74   686.1 2217.02   700.8 2225.84   706.1 2227.89
#Mann= 8 ,-1,0
       0      .1       0     150     .06       0  226.66      .1       0
  271.49     .06       0   279.8    .045       0   356.6     .06       0
  519.65      .1       0  639.65     .06       0
Bank Sta=279.8,356.6
XS Rating Curve= 0 ,0
Exp/Cntr(USF)=0,0
Exp/Cntr=0.3,0.1

Type RM Length L Ch R = 1 ,27373   ,104.6,104.6,104.6
XS GIS Cut Line= 6
2198214.29781826630497.0024928982198347.57591792630381.051289985
2198319.13482372630334.1655830462198287.73943742630243.601968704
 2198252.8852151630180.251571813  2198446.134827630006.115021663
#Sta/Elev= 30
       0  2200.4    46.9 2213.99    97.2 2199.32   144.7 2187.68   208.4  2163.5
   221.2 2163.05   233.9 2167.63   245.3 2168.65   298.4 2167.54   307.8  2166.4
  315.98 2162.89   321.8  2161.5   364.5 2161.43  387.89 2162.89   398.3 2167.97
   428.6 2165.07   478.7  2164.1   493.3 2165.17     498 2163.44   514.1 2167.92
   546.4 2166.07   627.1 2167.41   650.9 2166.35   662.2 2169.65   670.2 2174.92
   691.7 2196.53   707.2 2208.99   719.2 2212.14   735.9 2224.17   753.6 2232.55
#Mann= 6 ,-1,0
       0      .1       0  186.92     .06       0  315.98    .045       0
  387.89     .06       0  573.47      .1       0  663.47     .06       0
Bank Sta=315.98,387.89
XS Rating Curve= 0 ,0
Exp/Cntr(USF)=0,0
Exp/Cntr=0.3,0.1

Type RM Length L Ch R = 1 ,27269   ,269.6,269.6,269.6
XS GIS Cut Line= 4
2198272.52191381630553.200170122 2198375.3842906630451.828552423
2198434.26927441630144.7321811562198492.40887868630081.374920093
#Sta/Elev= 30
       0 2206.66     8.3 2202.61    19.6 2202.16    73.3 2181.17      79 2178.07
    96.9 2165.43   106.2  2161.7   115.7 2161.74   155.3 2167.14   219.1 2165.44
   232.6 2167.15  241.912162.223   248.9 2160.72   272.7 2160.67   287.5 2162.21
   297.8 2162.85     310 2165.31   322.3 2165.13   334.5  2162.6   375.2 2165.64
   418.9 2163.35   451.5 2165.86   459.9 2170.57   471.8  2180.9   478.2  2187.6
   494.5  2200.6   513.2 2213.09   526.1 2219.56   537.9 2224.07   543.1 2227.27
#Mann= 6 ,-1,0
       0      .1       0      50     .06       0  241.91    .045       0
   287.5      .1       0  374.42     .07       0  477.11     .06       0
Bank Sta=241.91,287.5
XS Rating Curve= 0 ,0
Exp/Cntr(USF)=0,0
Exp/Cntr=0.3,0.1

Type RM Length L Ch R = 1 ,26999   ,356.4,356.4,356.4
XS GIS Cut Line= 3
2198371.50068806 630688.550062692198452.08874776  630589.7271582
2198763.99052537630337.565565655
#Sta/Elev= 30
       0 2220.69     5.7 2218.02    14.7 2217.06    26.4 2211.46    50.8 2202.29
    79.6 2189.58    97.3 2180.38   123.1 2163.99   128.4 2161.59   133.7 2160.52
   148.2 2160.19   168.8 2163.25   211.1 2164.39   224.7 2163.19   271.7 2161.81
   312.9  2162.5   338.4 2161.53   343.7 2160.45   351.1 2158.87   358.4 2158.43
   379.7 2158.84  384.932160.483   389.6 2165.27   410.5 2182.22     498 2208.21
   503.1 2210.41   510.1 2216.33   514.8 2218.89   518.5 2219.53   528.6 2219.18
#Mann= 4 ,-1,0
       0      .1       0  157.52     .06       0   343.7    .045       0
  384.93     .06       0
Bank Sta=343.7,384.93
XS Rating Curve= 0 ,0
Exp/Cntr=0.3,0.1

Type RM Length L Ch R = 1 ,26643   ,324.2,324.2,324.2
XS GIS Cut Line= 3
  2198672.781746630910.9409254952198745.49061764630820.054835946
2198957.93685196630521.266816556
#Sta/Elev= 30
       0 2230.68    27.9 2216.21      52 2202.29    95.1 2179.24   106.1 2170.66
     115 2164.97   119.9 2163.69   127.9 2163.84   154.3 2161.49   169.3 2157.63
   176.2 2155.88   188.6 2155.71   200.7 2156.09  206.972157.618   210.8 2159.05
     215 2159.51   240.9  2158.9   252.4 2161.01   278.1 2162.92   301.5 2167.73
   345.7 2171.81   369.9 2176.28   378.5 2178.51   404.6 2182.87   418.7 2187.28
   438.8 2188.99     456 2194.66   464.6 2198.34   473.9 2198.95     483 2201.47
#Mann= 6 ,-1,0
       0      .1       0  126.39     .06       0   169.3    .045       0
  206.97     .06       0  246.39      .1       0  336.39     .06       0
Bank Sta=169.3,206.97
XS Rating Curve= 0 ,0
Exp/Cntr(USF)=0,0
Exp/Cntr=0.3,0.1

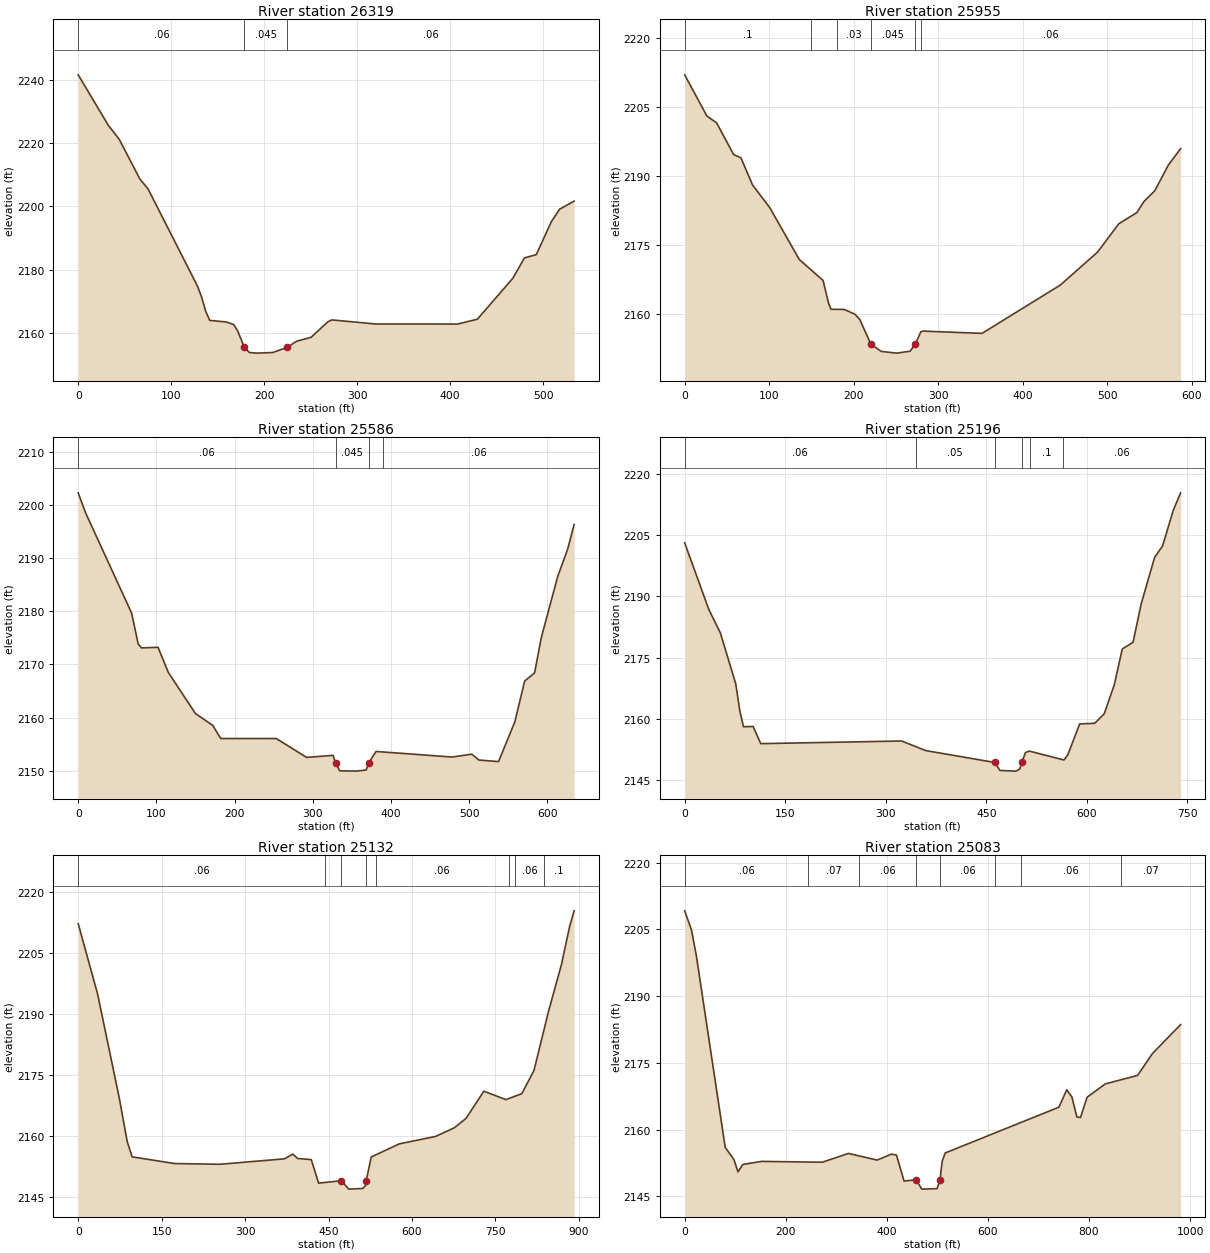
Type RM Length L Ch R = 1 ,26319   ,363.2,363.2,363.2
XS GIS Cut Line= 3
2198981.18855819631105.1528268652199044.09567014630971.414397007
2199168.86482686630606.694341784
#Sta/Elev= 30
       0 2241.52    32.3 2225.63    44.2 2221.15    66.3 2208.66    75.1 2205.54
   128.2  2174.9   132.6 2171.52     137 2167.01   141.4 2164.07   159.1 2163.57
   167.1 2162.77   171.3 2160.83  178.762155.545     184 2153.94   192.4 2153.74
   209.3 2153.94   224.72155.545   234.7 2157.47   250.4 2158.73   268.5 2163.63
   272.8 2164.22   319.7 2162.93     408 2162.91   429.2 2164.43   467.2 2177.29
   479.9 2183.78   492.6 2184.81   508.7 2195.14   517.5 2199.09   533.3  2201.7
#Mann= 3 ,-1,0
       0     .06       0  178.76    .045       0   224.7     .06       0
Bank Sta=178.76,224.7
XS Rating Curve= 0 ,0
Exp/Cntr=0.3,0.1

Type RM Length L Ch R = 1 ,25955   ,369,369,369
XS GIS Cut Line= 3
2199278.87739701631260.4008761262199374.87678776631119.978931456
2199518.26906865630728.487341784
#Sta/Elev= 30
       0 2212.05    26.3 2203.08    37.8  2201.6    57.9 2194.71    66.6 2193.98
    80.3 2188.09   100.8 2183.12   135.6 2171.87   163.8  2167.3   170.1 2162.47
   173.1 2161.02   188.9 2160.99   201.4 2159.96   207.2 2158.84  220.262153.452
   232.7 2151.85   251.2 2151.48   266.8  2151.9     2732153.452   279.6 2156.15
   282.4 2156.27     352 2155.78   444.6 2166.29   488.6 2173.45   513.9 2179.65
   535.2 2182.07   543.7  2184.5   556.5 2186.83   572.4 2192.39     587 2195.99
#Mann= 6 ,-1,0
       0      .1       0     150     .06       0   180.1     .03       0
  220.26    .045       0     273     .03       0   280.1     .06       0
Bank Sta=220.26,273
XS Rating Curve= 0 ,0
Exp/Cntr=0.3,0.1

Type RM Length L Ch R = 1 ,25586   ,390.2,390.2,390.2
XS GIS Cut Line= 2
2199642.49128358  631481.81592092199847.00854626630881.319244768
#Sta/Elev= 30
       0 2202.28     9.1 2198.63    68.3 2179.66    76.7 2173.87      81 2173.11
   102.1 2173.22   115.3 2168.49     150 2160.76     172 2158.54   182.4 2156.06
   253.4 2156.06   292.2 2152.51     326  2152.9  329.122151.514   334.5    2150
   354.9 2149.93   368.3 2150.13  371.442151.457     381 2153.63   478.2 2152.58
   503.5 2153.12   512.5 2152.02   537.7 2151.72   558.5 2159.19   571.1 2166.87
   583.8  2168.4   592.3    2175   613.3 2186.51   626.1 2191.69   634.4 2196.33
#Mann= 4 ,-1,0
       0     .06       0  329.12    .045       0  371.44     .07       0
     390     .06       0
Bank Sta=329.12,371.44
XS Rating Curve= 0 ,0
Exp/Cntr=0.3,0.1

Type RM Length L Ch R = 1 ,25196   ,63.9,63.9,63.9
XS GIS Cut Line= 4
2199700.93063402631522.1498777092199769.09520118631456.257462786
2200200.80412654631140.428301605 2200198.5319743631030.228918027
#Sta/Elev= 30
       0  2203.1    35.9 2186.83    53.2 2181.04    76.2 2168.57    82.4 2161.84
    87.7 2158.06   102.1 2158.11   113.5 2153.91   323.6 2154.56   359.7 2152.21
   462.7  2149.3   470.3 2147.35   494.2 2147.18   499.9 2147.69  503.022149.314
   508.5 2151.75   514.2 2152.09   565.8 2149.91   571.5 2151.12   589.3 2158.74
   611.8  2158.9   625.9 2161.21     641 2168.34   652.8 2177.08     669 2178.77
     681 2188.11     701 2199.48     713 2202.36     729  2211.1   739.9 2215.35
#Mann= 6 ,-1,0
       0     .06       0  344.81     .05       0   462.7    .045       0
  503.02     .05       0  514.81      .1       0  564.81     .06       0
Bank Sta=462.7,503.02
XS Rating Curve= 0 ,0
Exp/Cntr(USF)=0,0
Exp/Cntr=0.3,0.1

Type RM Length L Ch R = 1 ,25132   ,48.9,48.9,48.9
XS GIS Cut Line= 4
2199719.42201274631571.1062333412199879.88648769631461.202946421
2200359.52844023 631095.843913982200310.67608895631015.497876382
#Sta/Elev= 30
       0 2212.29    34.9 2194.96    73.9 2169.35    88.2 2158.65    96.9 2154.94
   173.3 2153.29   254.7 2153.11   370.8 2154.45   385.9  2155.6   394.5 2154.53
     419 2154.25   432.2 2148.47   472.72149.072   486.5    2147   511.5 2147.16
   516.7 2147.89  517.75 2149.08   526.7  2154.9   577.2 2158.13   642.4 2159.96
   676.4  2162.1   697.1  2164.4   729.2 2171.08   768.8 2169.01   797.4 2170.47
   819.3 2176.18   845.5 2190.75   868.8 2202.29   883.3 2211.58   891.5 2215.44
#Mann= 8 ,-1,0
       0     .06       0  444.49     .05       0   472.7    .045       0
  517.75     .05       0  534.49     .06       0  774.49      .1       0
  784.49     .06       0  837.44      .1       0
Bank Sta=472.7,517.75
XS Rating Curve= 0 ,0
Exp/Cntr(USF)=0,0
Exp/Cntr=0.3,0.1

Type RM Length L Ch R = 1 ,25083   ,99.8,99.8,99.8
XS GIS Cut Line= 4
2199753.14536873631605.5675886182199913.60984368631495.664301698
2200428.94778672631103.0635922982200561.39349244 631061.23164971
#Sta/Elev= 30
       0 2209.19    13.4 2204.93    23.1  2199.1    80.2 2155.98    97.4 2153.25
   105.5 2150.47   115.2 2152.14   152.1 2152.83   272.3 2152.64     324 2154.62
   380.8 2153.12   408.9 2154.46     419 2154.25   434.1  2148.4   457.8  2148.7
   469.2 2146.59   499.4 2146.71  505.18 2148.71   509.5 2152.86   515.4 2154.72
   740.4 2165.02   755.9 2168.93   766.1 2167.31     776 2162.83   783.2 2162.72
   796.1 2167.26   832.3 2170.26   896.1 2172.17   925.4 2177.08   981.2  2183.6
#Mann= 8 ,-1,0
       0     .06       0  244.49     .07       0  344.49     .06       0
   457.8    .045       0  505.18     .06       0  614.49     .07       0
  664.49     .06       0  862.34     .07       0
Bank Sta=457.8,505.18
XS Rating Curve= 0 ,0
Exp/Cntr(USF)=0,0
Exp/Cntr=0.3,0.1

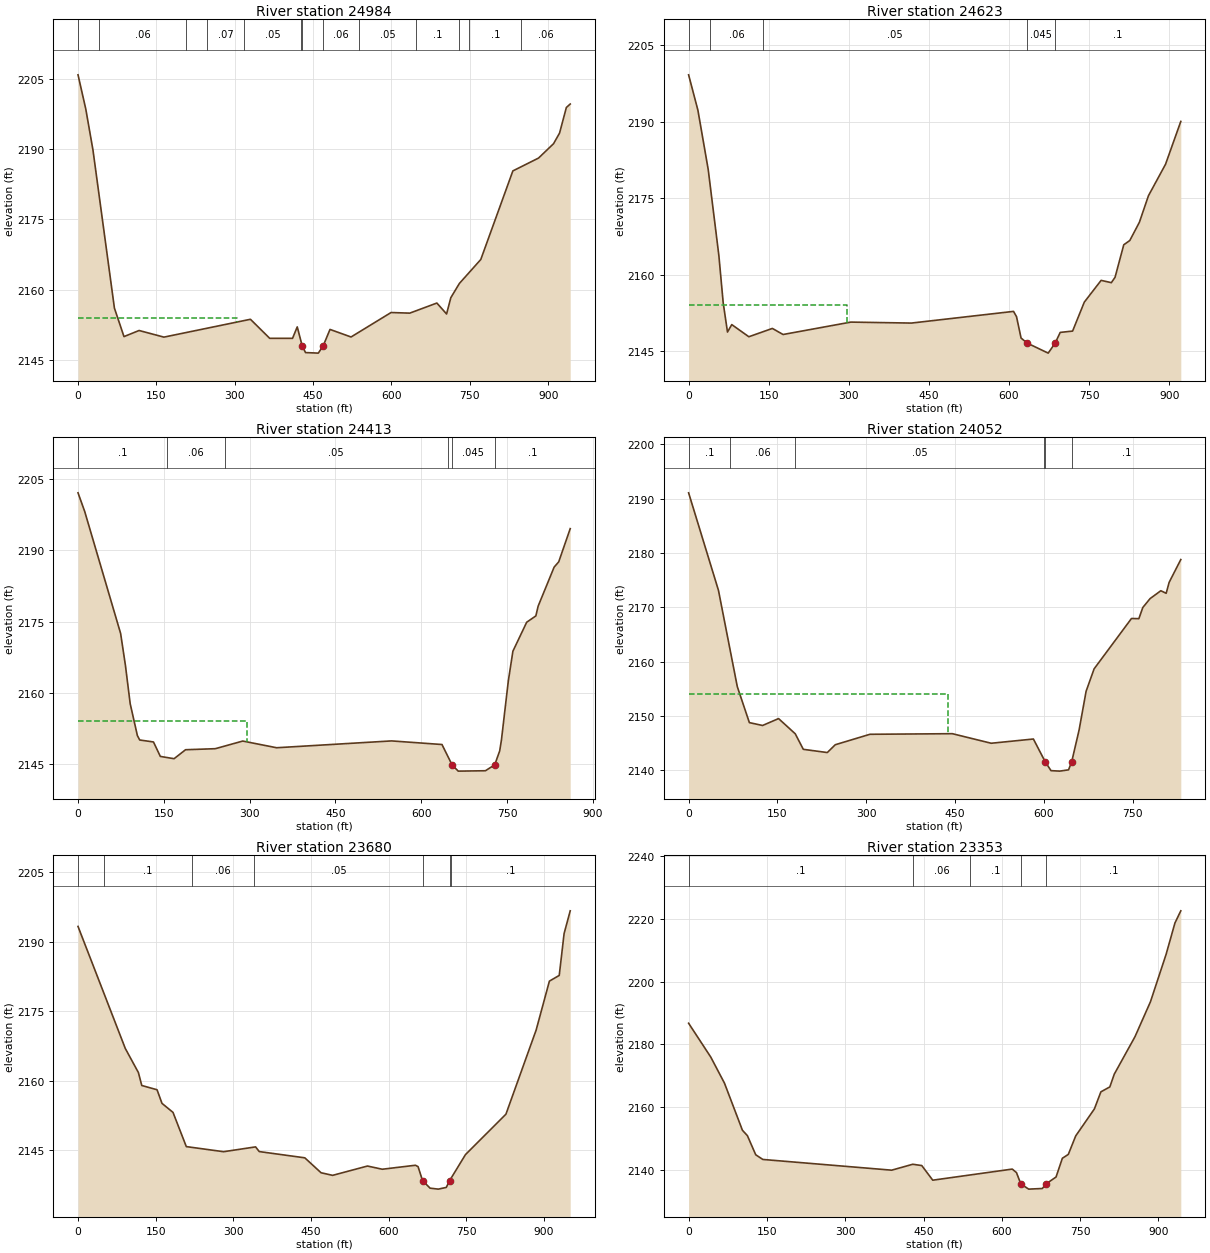
Type RM Length L Ch R = 1 ,24984   ,360.5,360.5,360.5
XS GIS Cut Line= 4
2199775.12843534631622.6192985822199860.60619875631575.405074712
2200352.93816835631327.2363523482200639.34275063631264.107236254
#Sta/Elev= 30
       0 2205.82    14.9 2198.51    28.6  2189.8    69.7 2156.11      88 2150.05
   116.9 2151.35   164.5 2149.94   330.1 2153.74     367 2149.68   410.7 2149.68
   419.7 2152.12  429.112148.096   435.5 2146.65     460 2146.53  469.422148.092
   482.4 2151.58   522.7 2149.97   599.3 2155.18   635.1 2155.05     687  2157.2
   705.6 2154.87   713.7 2158.34   730.1 2161.37   771.1 2166.48   832.5 2185.35
   881.7 2188.09   910.4 2191.15   921.9 2193.41   934.9 2198.86   942.3  2199.6
#Mann= 13 ,-1,0
       0      .1       0      40     .06       0  207.65     .05       0
  247.65     .07       0  317.65     .05       0  427.65      .1       0
  429.11    .045       0  469.42     .06       0  537.65     .05       0
  647.65      .1       0  728.99     .05       0  748.99      .1       0
  848.99     .06       0
#XS Ineff= 2 , 0
        303.8141    2154
Permanent Ineff=
       F       F
Bank Sta=429.11,469.42
XS Rating Curve= 0 ,0
Exp/Cntr=0.3,0.1

Type RM Length L Ch R = 1 ,24623   ,210.1,210.1,210.1
XS GIS Cut Line= 3
2199815.48476651631705.2960203042200352.33220783631681.725898238
2200622.85577626631408.825970493
#Sta/Elev= 30
       0 2199.16    17.4 2192.23    36.7 2180.61    56.7 2163.72    64.8 2154.45
    72.8 2148.75    80.8 2150.21   112.8 2147.83   156.8 2149.46   176.9 2148.27
   303.8  2150.7   417.1 2150.51   608.4  2152.8     614 2151.76   622.5 2147.58
   633.7  2146.6   673.3 2144.62  686.472146.606   695.8 2148.68     719 2148.94
   740.9 2154.61   772.4 2158.88   791.6 2158.43   798.5 2159.49   814.8 2165.85
   826.1 2166.69     844 2170.25     861 2175.46     893 2181.63   921.6 2190.03
#Mann= 5 ,-1,0
       0      .1       0      40     .06       0     140     .05       0
   633.7    .045       0  686.47      .1       0
#XS Ineff= 2 , 0
        296.6432    2154
Permanent Ineff=
       F       F
Bank Sta=633.7,686.47
XS Rating Curve= 0 ,0
Exp/Cntr(USF)=0,0
Exp/Cntr=0.3,0.1

Type RM Length L Ch R = 1 ,24413   ,361.5,361.5,361.5
XS GIS Cut Line= 3
2199804.97427161631729.9612133812199906.51208935631761.216635566
 2200660.2842821631788.795340327
#Sta/Elev= 30
       0 2202.14    11.7  2198.2    74.5 2172.48    82.9 2165.74    91.2 2157.69
   103.8 2150.95   107.9 2150.03   131.9 2149.62   143.9 2146.57   167.9 2146.09
     188 2147.98     240  2148.2     288 2149.81   347.2  2148.4   548.2 2149.84
   636.3 2149.08  653.912144.797   664.7 2143.47   712.3 2143.55  728.482144.798
   737.2 2147.73   740.3 2150.08   752.3  2162.5   760.3 2168.75   784.4 2174.86
   800.4 2176.19   804.4 2178.24   832.4 2186.48   840.4 2187.59   860.5 2194.59
#Mann= 6 ,-1,0
       0      .1       0  156.24     .06       0  256.24     .05       0
  646.24      .1       0  653.91    .045       0  728.48      .1       0
#XS Ineff= 2 , 0
        294.8672    2154
Permanent Ineff=
       F       F
Bank Sta=653.91,728.48
XS Rating Curve= 0 ,0
Exp/Cntr=0.3,0.1

Type RM Length L Ch R = 1 ,24052   ,371.2,371.2,371.2
XS GIS Cut Line= 3
2199798.54158228631813.2911938512199925.28961049631893.258620976
2200530.08352369632206.693213381
#Sta/Elev= 30
       0  2191.1    50.4 2173.16    82.2 2155.44   102.6 2148.81   124.9 2148.28
   151.9 2149.55   180.1 2146.75   193.7 2143.89   234.2  2143.3   247.7 2144.74
   306.2 2146.66   445.3 2146.77     511 2145.01   582.2 2145.79  602.01 2141.63
   611.9 2139.97   626.7 2139.88   641.6 2140.12  646.942141.631   659.4 2147.47
   671.2 2154.58   684.7  2158.7   747.8 2167.97   760.3 2167.94   766.9 2169.99
   779.3 2171.64   797.4 2173.08   806.4 2172.61   811.4 2174.62   831.1 2178.82
#Mann= 6 ,-1,0
       0      .1       0      70     .06       0  179.87     .05       0
  599.87      .1       0  602.01    .045       0  646.94      .1       0
#XS Ineff= 2 , 0
        437.6422    2154
Permanent Ineff=
       F       F
Bank Sta=602.01,646.94
XS Rating Curve= 0 ,0
Exp/Cntr=0.3,0.1

Type RM Length L Ch R = 1 ,23680   ,327.5,327.5,327.5
XS GIS Cut Line= 2
2199589.53282642631975.8087914452200328.68358555632573.300676439
#Sta/Elev= 30
       0 2193.28    91.3 2166.96   116.6 2161.77   123.1 2158.98   152.6 2158.06
   162.1 2155.13   183.4 2153.18   209.1  2145.8   281.1  2144.7   342.9 2145.74
   349.9 2144.73   437.9 2143.38   469.3 2140.16   491.6  2139.6   558.9 2141.61
   587.6 2140.92   651.5 2141.78   656.6 2141.48  665.322138.449   679.8 2136.84
   695.7 2136.63   711.1    2137  717.45 2138.45   748.1 2144.07   826.3  2152.8
   884.6 2170.94   910.2 2181.49   929.2 2182.72   938.6 2191.76   950.4 2196.65
#Mann= 7 ,-1,0
       0     .05       0      50      .1       0     220     .06       0
     340     .05       0  665.32    .045       0  717.45     .05       0
     720      .1       0
Bank Sta=665.32,717.45
XS Rating Curve= 0 ,0
Exp/Cntr(USF)=0,0
Exp/Cntr=0.3,0.1

Type RM Length L Ch R = 1 ,23353   ,447.2,447.2,447.2
XS GIS Cut Line= 2
2199427.79355262632244.2322915012200146.27087305632854.892116818
#Sta/Elev= 30
       0 2186.73    42.5 2175.93    68.7 2167.63   103.1 2152.61   112.6  2150.9
   128.6 2144.79   142.2  2143.3     389 2139.88   429.4 2141.77   446.7 2141.35
   467.7 2136.69     620 2140.23   628.1 2139.11  636.522135.476   651.5 2133.84
   677.7 2134.04  684.522135.476   703.9  2137.7     716 2143.68   727.4 2144.91
   741.6 2150.81   777.4 2159.42   789.8 2164.86   806.9 2166.42   815.4 2170.48
   855.1 2182.43   884.7 2193.55   914.7 2208.68   931.7 2218.71   942.9 2222.57
#Mann= 5 ,-1,0
       0      .1       0     430     .06       0     540      .1       0
  636.52    .045       0  684.52      .1       0
Bank Sta=636.52,684.52
XS Rating Curve= 0 ,0
Exp/Cntr=0.3,0.1

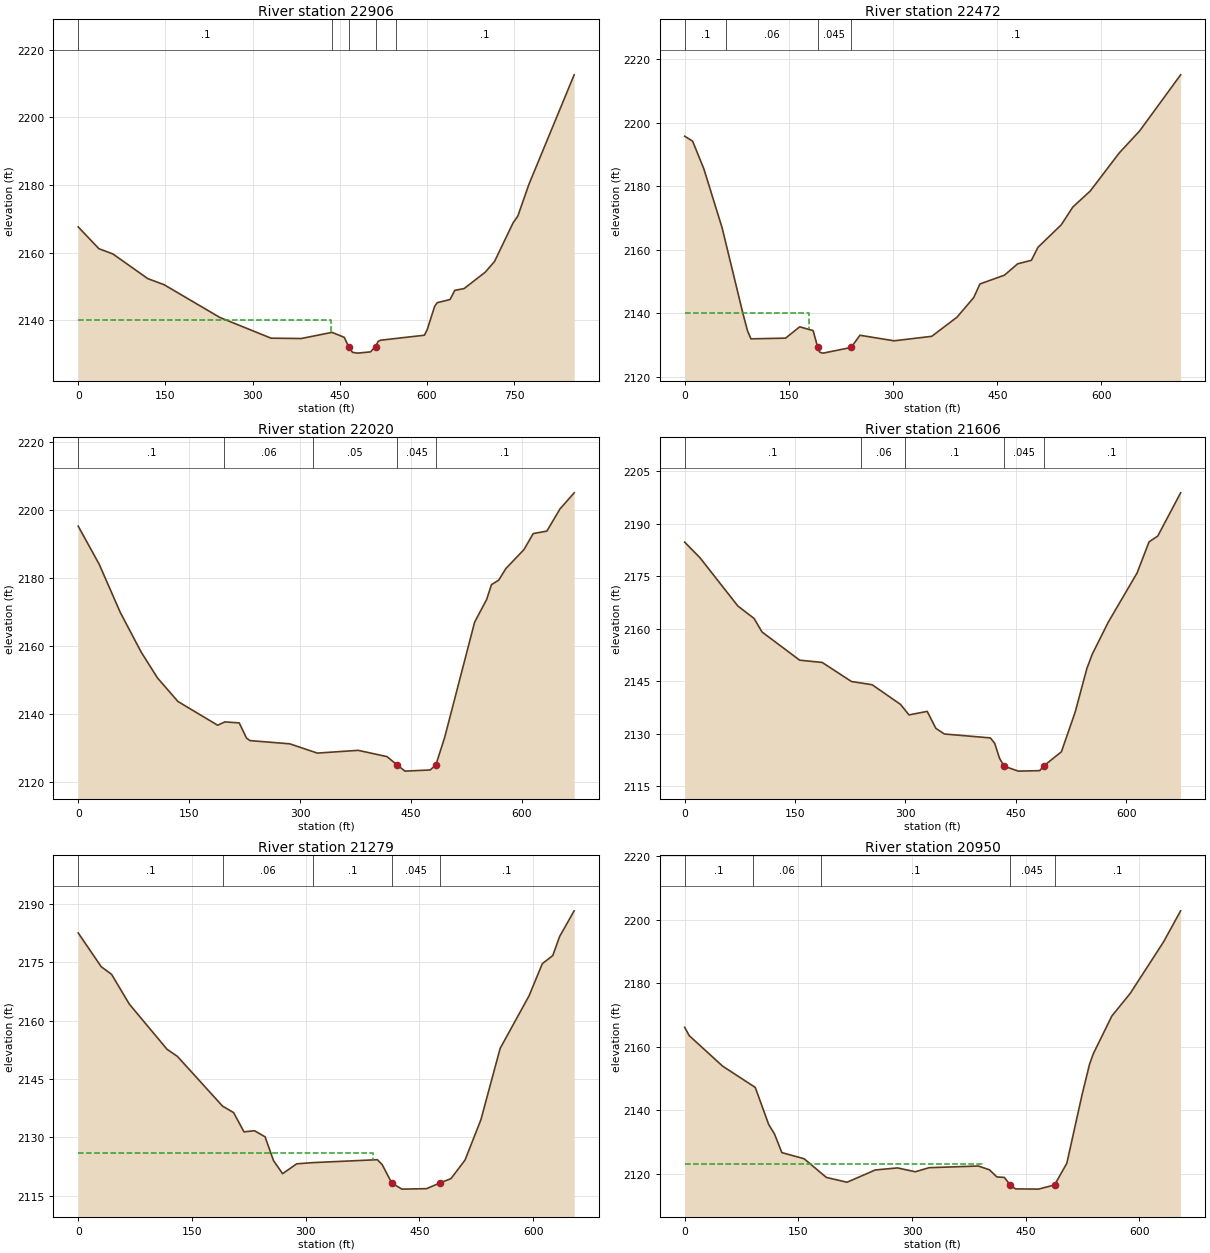
Type RM Length L Ch R = 1 ,22906   ,433.2,433.2,433.2
XS GIS Cut Line= 4
2199224.47498011633031.498292227 2199651.6156792633032.230699459
 2199846.2018756633123.1054156832200056.76354322633106.004660398
#Sta/Elev= 30
       0 2167.65    35.7  2161.2    59.7 2159.66   119.7 2152.37   147.7 2150.58
   243.7 2140.89   331.7 2134.77   383.7 2134.67   436.6 2136.49   457.7 2135.02
  465.332132.217   471.9 2130.58   480.7 2130.35   502.8 2130.72   511.6  2132.3
   516.1 2133.85   520.5 2134.17   595.5 2135.64   600.3 2137.25   613.2 2144.17
   617.6 2145.26   639.7 2146.19   647.9  2148.9   663.9 2149.43   700.1 2154.25
   716.2 2157.43   748.2 2168.87   756.2 2170.81   775.4 2180.24   853.2  2212.6
#Mann= 5 ,-1,0
       0      .1       0  437.14     .06       0  465.33    .045       0
   511.6     .06       0  547.14      .1       0
#XS Ineff= 2 , 0
         435.696    2140
Permanent Ineff=
       F       F
Bank Sta=465.33,511.6
XS Rating Curve= 0 ,0
Exp/Cntr=0.3,0.1

Type RM Length L Ch R = 1 ,22472   ,452,452,452
XS GIS Cut Line= 4
2199517.05669006633614.2023309242199588.13026331633539.666659446
2199851.81212804633362.9437075472200132.70865027633277.759427487
#Sta/Elev= 30
       0 2195.77    11.4 2194.23    27.7 2185.44    53.9 2166.92    84.3 2139.54
    90.6  2134.4    95.4 2131.96   145.2 2132.18   165.6 2135.74   184.9 2134.56
  191.59 2129.24   194.5 2127.72   199.3 2127.46  239.53 2129.24   252.3 2133.09
   301.4 2131.34   355.6 2132.75     392 2138.78     416 2144.93     425 2149.24
   460.3 2152.01   479.3 2155.58   499.1  2156.7   508.6  2160.8     542 2167.85
   558.7 2173.45   583.8 2178.51   625.6 2190.51   654.9 2197.43   713.9  2215.1
#Mann= 4 ,-1,0
       0      .1       0      60     .06       0  191.59    .045       0
  239.53      .1       0
#XS Ineff= 2 , 0
        179.3023    2140
Permanent Ineff=
       F       F
Bank Sta=191.59,239.53
XS Rating Curve= 0 ,0
Exp/Cntr=0.3,0.1

Type RM Length L Ch R = 1 ,22020   ,414.2,414.2,414.2
XS GIS Cut Line= 3
2199664.16988354633852.8805725132199839.18906005 633822.98440773
2200243.92541736633541.654126946
#Sta/Elev= 30
       0 2195.18    28.4 2183.98    56.8 2169.87    85.2 2158.15   107.2 2150.57
   134.9 2143.65   188.5 2136.68   198.2 2137.66   217.7 2137.36   227.5 2132.92
   232.3 2132.16   285.9 2131.22   323.3 2128.49   378.5  2129.3   417.5 2127.45
  431.072125.023   441.8 2123.19   475.9 2123.53  483.542125.022   495.4 2133.06
   535.9 2166.94   552.2 2173.65   558.7 2177.99   568.5 2179.31   578.2 2182.73
   602.6 2188.29   615.2 2193.01   633.6 2193.73   651.3 2200.23   670.5 2204.98
#Mann= 5 ,-1,0
       0      .1       0  197.55     .06       0  317.55     .05       0
  431.07    .045       0  483.54      .1       0
Bank Sta=431.07,483.54
XS Rating Curve= 0 ,0
Exp/Cntr=0.3,0.1

Type RM Length L Ch R = 1 ,21606   ,327.2,327.2,327.2
XS GIS Cut Line= 2
2199794.30704052634290.0379234652200370.76047886633940.799708997
#Sta/Elev= 30
       0 2184.79    20.9 2180.31    72.3 2166.54    94.3 2162.99   105.1 2159.13
   156.3 2151.07   186.9 2150.42   226.7 2144.97   254.7 2144.06   293.2 2138.46
   304.9 2135.43   329.6 2136.44   341.3 2131.61   352.9 2129.98   415.5 2128.86
   421.4 2127.29   427.8  2123.1  433.872120.799   453.4 2119.37   482.5 2119.51
  487.652120.798     512  2124.9   530.7 2136.24   546.6 2148.69     554 2152.81
   575.7 2161.94   614.8 2175.97   631.1 2184.87   642.9 2186.52     674 2198.88
#Mann= 5 ,-1,0
       0      .1       0     240     .06       0     300      .1       0
  433.87    .045       0  487.65      .1       0
Bank Sta=433.87,487.65
XS Rating Curve= 0 ,0
Exp/Cntr(USF)=0,0
Exp/Cntr=0.3,0.1

Type RM Length L Ch R = 1 ,21279   ,328.6,328.6,328.6
XS GIS Cut Line= 2
2199983.14396166634548.4293113942200548.46592224634219.297107778
#Sta/Elev= 30
       0 2182.58    30.3 2173.91    44.1  2171.9    67.5 2164.25   117.2 2152.64
   130.8 2150.83   190.4 2138.02     205 2136.35   218.7  2131.4   232.6 2131.68
   246.5 2130.12   257.6 2124.01   269.6 2120.63   288.2 2123.17   310.3 2123.49
   394.6 2124.23     401 2122.96  413.672118.212     427 2116.66   459.5 2116.78
     477 2118.24   491.7 2119.36   510.3 2124.15   531.2 2134.52   556.6 2152.88
   594.8 2166.43   612.2 2174.67     626 2176.76     635 2181.65   654.2 2188.27
#Mann= 5 ,-1,0
       0      .1       0   190.4     .06       0   310.3      .1       0
  413.67    .045       0     477      .1       0
#XS Ineff= 2 , 0
           389.3    2126
Permanent Ineff=
       F       F
Bank Sta=413.67,477
XS Rating Curve= 0 ,0
Exp/Cntr=0.3,0.1

Type RM Length L Ch R = 1 ,20950   ,324.2,324.2,324.2
XS GIS Cut Line= 2
2200179.29041772634858.7462528042200714.43951429634482.212379387
#Sta/Elev= 30
       0  2166.1       6 2163.48      50 2153.88    93.1 2147.17   110.9 2135.45
   118.5 2132.49   128.2 2126.63   157.6 2124.69   186.9 2118.81   214.2 2117.29
   251.5 2121.16   280.8  2121.8   304.3 2120.59   322.5 2121.88   387.5  2122.4
   402.1 2121.21   411.9 2118.96   421.7 2118.81   429.5 2116.43   436.4  2115.2
   466.8 2115.12  488.052116.445   504.2 2123.29   524.4 2144.98   534.2 2154.51
   539.1 2157.76   563.5 2169.63     588 2176.85     632  2193.1   654.3  2202.8
#Mann= 5 ,-1,0
       0      .1       0      90     .06       0     180      .1       0
   429.5    .045       0  488.05      .1       0
#XS Ineff= 2 , 0
        391.7848    2123
Permanent Ineff=
       F       F
Bank Sta=429.5,488.05
XS Rating Curve= 0 ,0
Exp/Cntr=0.3,0.1