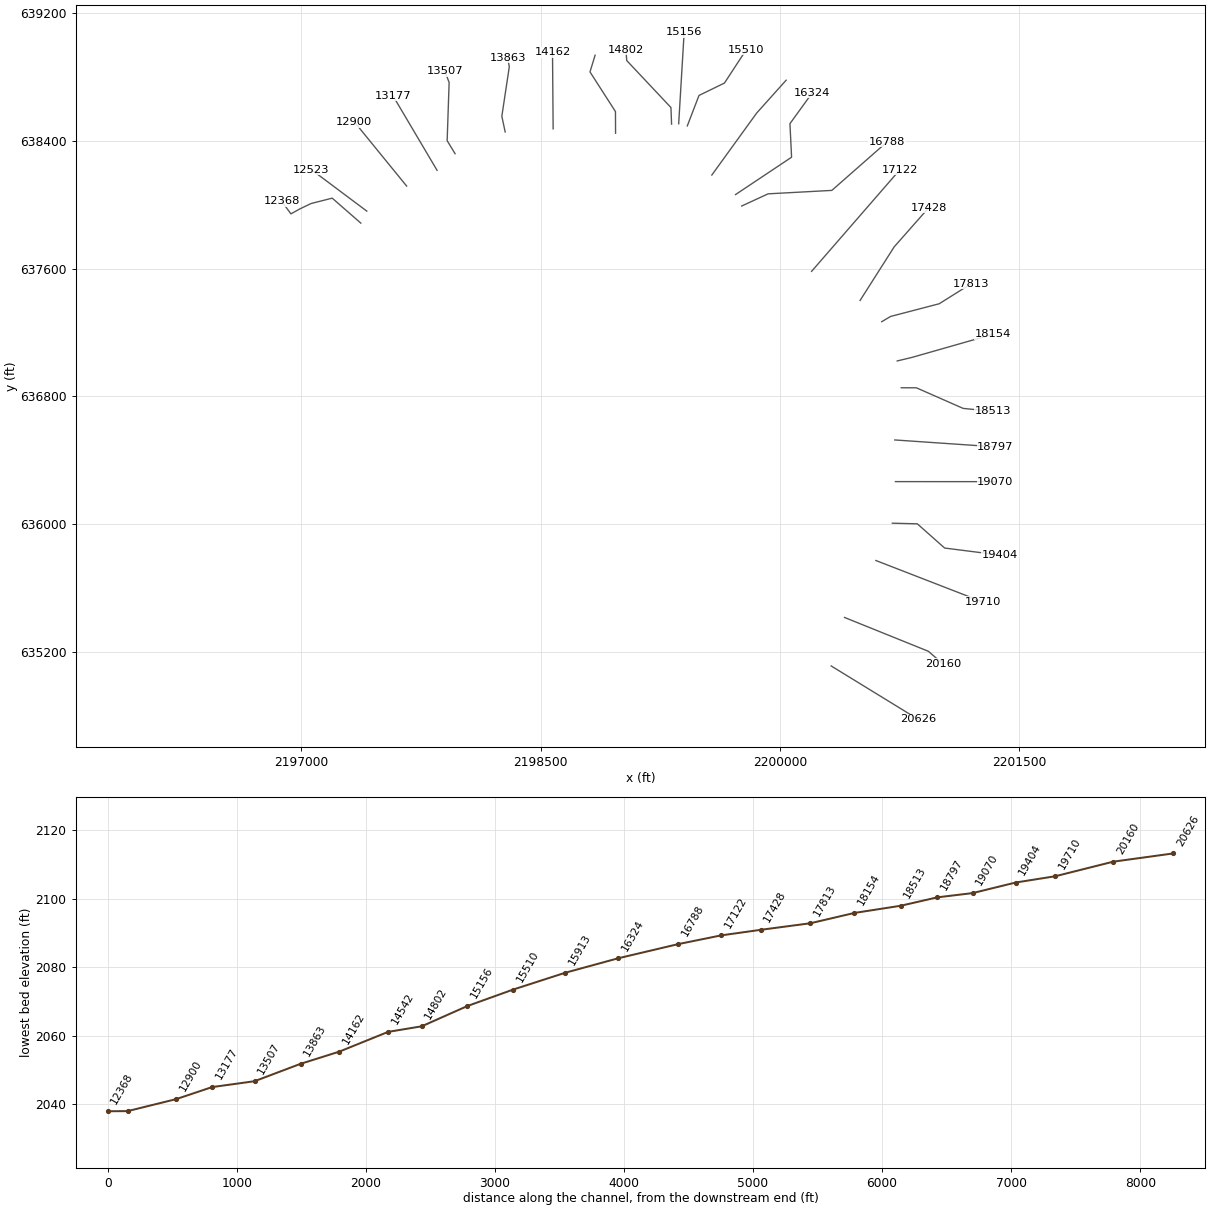
HEC-RAS study LFRFBUCRV.prj: LFRFBUCRV

--- LFRFBUCRV.g01 (geometry) --- (continued)

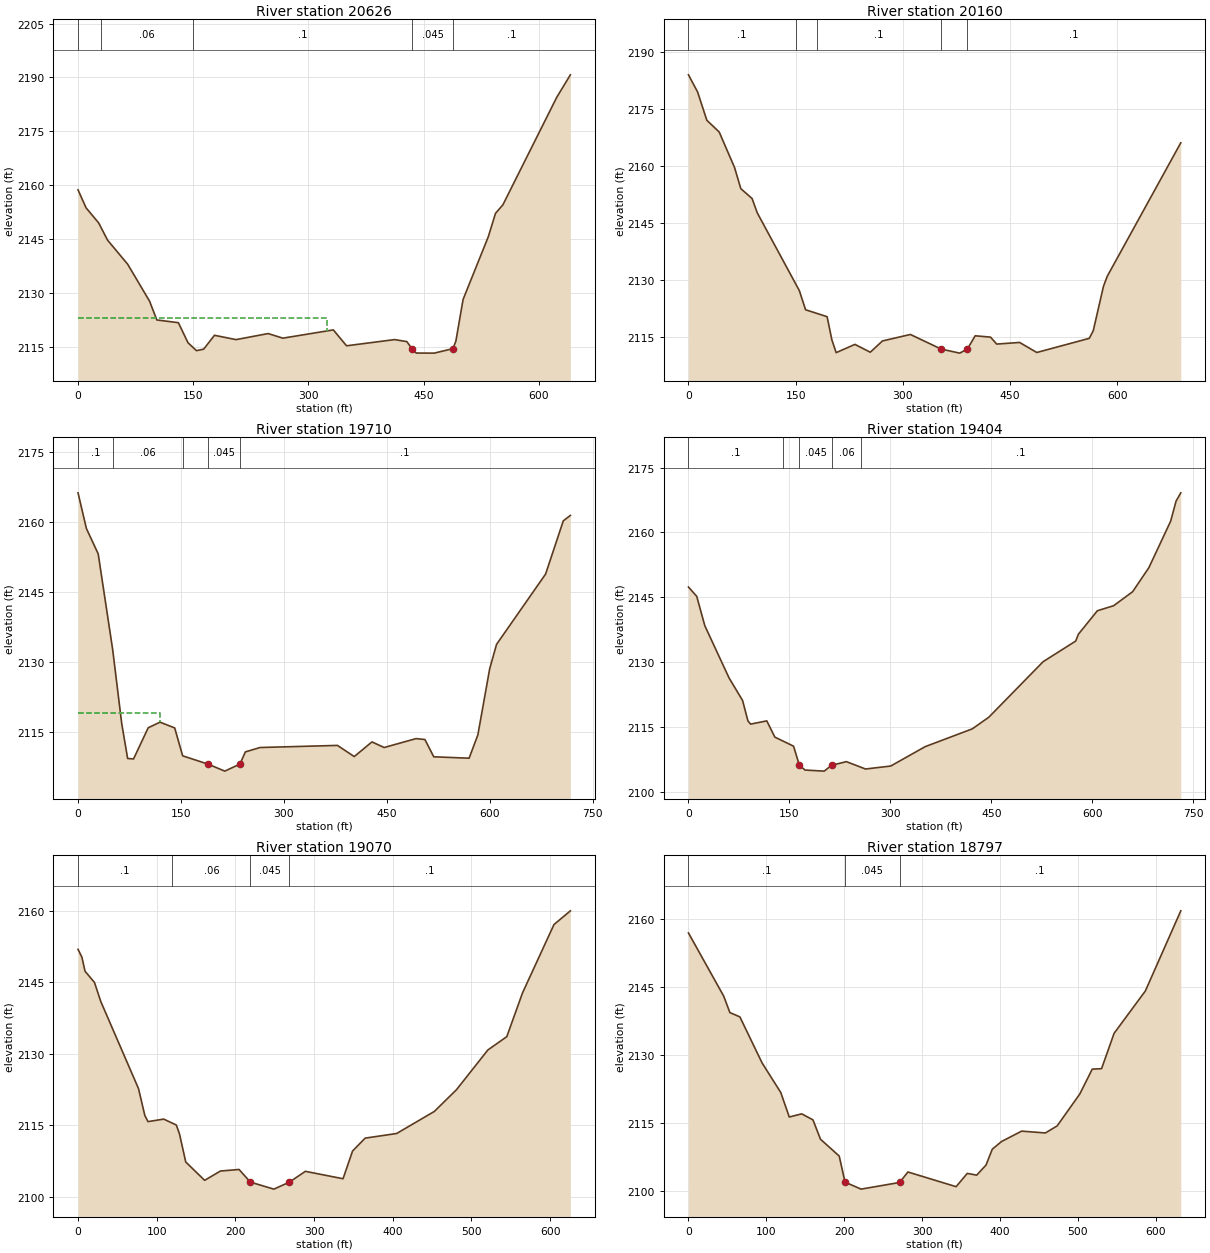
Type RM Length L Ch R = 1 ,20626   ,465.8,465.8,465.8
XS GIS Cut Line= 2
 2200320.7423595635110.6795052452200867.26781991634775.324759635
#Sta/Elev= 30
       0 2158.69    10.5 2153.68    26.9 2149.48    38.5 2144.68    64.7 2137.97
    93.2 2127.68   102.6 2122.46   130.7  2121.7   143.2 2116.12   154.2 2113.91
   163.6 2114.32   177.7 2118.19   205.8 2116.98   247.6 2118.67   266.8 2117.39
   332.5 2119.69   349.7 2115.26   412.3 2116.99   428.2 2116.43  434.872114.473
   440.5 2113.24   463.9 2113.22  488.282114.469   492.1 2116.57   501.5 2128.18
   534.3 2145.63   543.7 2152.15   553.3 2154.52   623.5 2184.48   641.2 2190.73
#Mann= 5 ,-1,0
       0      .1       0      30     .06       0     150      .1       0
  434.87    .045       0  488.28      .1       0
#XS Ineff= 2 , 0
        323.8891    2123
Permanent Ineff=
       F       F
Bank Sta=434.87,488.28
XS Rating Curve= 0 ,0
Exp/Cntr=0.3,0.1

Type RM Length L Ch R = 1 ,20160   ,449.9,449.9,449.9
XS GIS Cut Line= 3
2200404.33081591635414.4819515372200929.38320434635202.617019168
2201022.00298987635122.605892584
#Sta/Elev= 30
       0 2184.04    12.8 2179.52    25.7 2172.09      43 2168.99    64.5 2159.64
    73.2  2154.1      89 2151.49    96.2 2147.73   155.1 2127.25   163.8 2122.22
   193.9  2120.4   200.6 2114.29   206.6 2110.94   232.8 2113.11   254.3 2111.05
   271.3 2114.01   310.4 2115.72   353.5 2111.87   379.4 2110.81  390.162111.887
     401 2115.37   422.5 2115.02   431.1 2113.19   463.1 2113.62   487.2 2110.98
   560.6  2114.7   566.2 2116.73   580.4 2128.36   585.7 2131.02   688.6 2166.16
#Mann= 5 ,-1,0
       0      .1       0     150     .06       0     180      .1       0
   353.5    .045       0  390.16      .1       0
Bank Sta=353.5,390.16
XS Rating Curve= 0 ,0
Exp/Cntr=0.3,0.1

Type RM Length L Ch R = 1 ,19710   ,306,306,306
XS GIS Cut Line= 2
2200600.78082895635771.1445679592201269.80343257635511.670392551
#Sta/Elev= 30
       0 2166.19    12.2 2158.55    29.4 2153.11    50.5 2132.59    63.7 2116.73
    72.3 2109.26    80.9 2109.16   102.3 2115.84   119.5 2117.04   140.9 2115.81
   152.5 2109.83  189.922108.031   213.9 2106.55     236 2108.06   243.9 2110.67
   265.3 2111.61   378.2 2112.06   402.6 2109.67   428.4 2112.81   446.2 2111.61
   492.7 2113.52   505.6 2113.32   518.5 2109.62     570 2109.32   582.8 2114.33
     600 2128.48     610 2133.71   681.5 2148.78   707.3 2160.19   717.6 2161.35
#Mann= 5 ,-1,0
       0      .1       0    50.5     .06       0   152.5      .1       0
  189.92    .045       0     236      .1       0
#XS Ineff= 2 , 0
           119.5    2119
Permanent Ineff=
       F       F
Bank Sta=189.92,236
XS Rating Curve= 0 ,0
Exp/Cntr(USF)=0,0
Exp/Cntr=0.3,0.1

Type RM Length L Ch R = 1 ,19404   ,333.9,333.9,333.9
XS GIS Cut Line= 4
2200703.83877014636005.0496880552200860.40651194636000.990061184
2201031.50796013635849.295384466 2201375.1110791635805.621373129
#Sta/Elev= 30
       0 2147.37    12.3 2145.21    24.3 2138.41    60.4 2126.29    80.4  2121.1
    88.4 2116.35    92.4 2115.61   116.4 2116.36   128.4  2112.6   156.2  2110.5
   164.8 2106.09   173.3 2104.97   201.7 2104.72  212.872106.075   234.7 2106.92
   263.2 2105.21   300.6  2105.9   351.8 2110.39   421.8 2114.51   446.4 2117.21
   527.1 2130.07   575.5 2134.85   579.5 2136.43   607.7 2141.87   631.9 2143.04
   660.1 2146.28   684.3 2151.86   716.6 2162.61   724.7 2167.28   731.7 2169.19
#Mann= 5 ,-1,0
       0      .1       0     140     .06       0   164.8    .045       0
  212.87     .06       0  256.62      .1       0
Bank Sta=164.8,212.87
XS Rating Curve= 0 ,0
Exp/Cntr=0.3,0.1

Type RM Length L Ch R = 1 ,19070   ,273,273,273
XS GIS Cut Line= 2
2200723.27031044      636265.4412201348.92621493636265.197847761
#Sta/Elev= 30
       0  2151.9     4.9 2150.26     8.9 2147.31    20.9 2144.96    28.9 2140.97
    76.9 2122.69    84.9 2117.07    88.9 2115.78   108.9 2116.31   124.9 2115.07
   128.9 2113.23   136.9 2107.32   160.9 2103.47   180.9 2105.42   204.7 2105.75
  218.942103.105   248.9 2101.63   268.7  2103.1   288.9 2105.36   336.8 2103.81
   348.9 2109.62   364.9 2112.32   404.9 2113.29   452.8 2117.91   480.9 2122.46
   520.9 2130.81   544.9 2133.59   564.9 2142.77   604.9  2157.1   625.7 2159.97
#Mann= 4 ,-1,0
       0      .1       0     120     .06       0  218.94    .045       0
   268.7      .1       0
Bank Sta=218.94,268.7
XS Rating Curve= 0 ,0
Exp/Cntr=0.3,0.1

Type RM Length L Ch R = 1 ,18797   ,284.6,284.6,284.6
XS GIS Cut Line= 2
2200719.08702731636526.3967516022201349.60927355636483.225859067
#Sta/Elev= 30
       0 2156.89    45.2 2142.97    53.2 2139.32      66 2138.38    94.5 2128.23
   118.5  2121.7   129.4  2116.3   145.4 2116.99   159.8 2115.67   169.5 2111.39
   193.5 2107.69     201 2101.93   221.6 2100.39  271.112101.862   281.7 2104.17
   343.6 2100.93   357.9 2103.86     370 2103.47     382 2105.71     390  2109.2
     402  2110.9   427.7 2113.18   458.2 2112.78   473.3 2114.34   502.3 2121.36
   518.3 2126.85   530.3 2126.96   546.4 2134.76   586.5 2144.09     632 2161.77
#Mann= 3 ,-1,0
       0      .1       0     201    .045       0  271.11      .1       0
Bank Sta=201,271.11
XS Rating Curve= 0 ,0
Exp/Cntr(USF)=0,0
Exp/Cntr=0.3,0.1

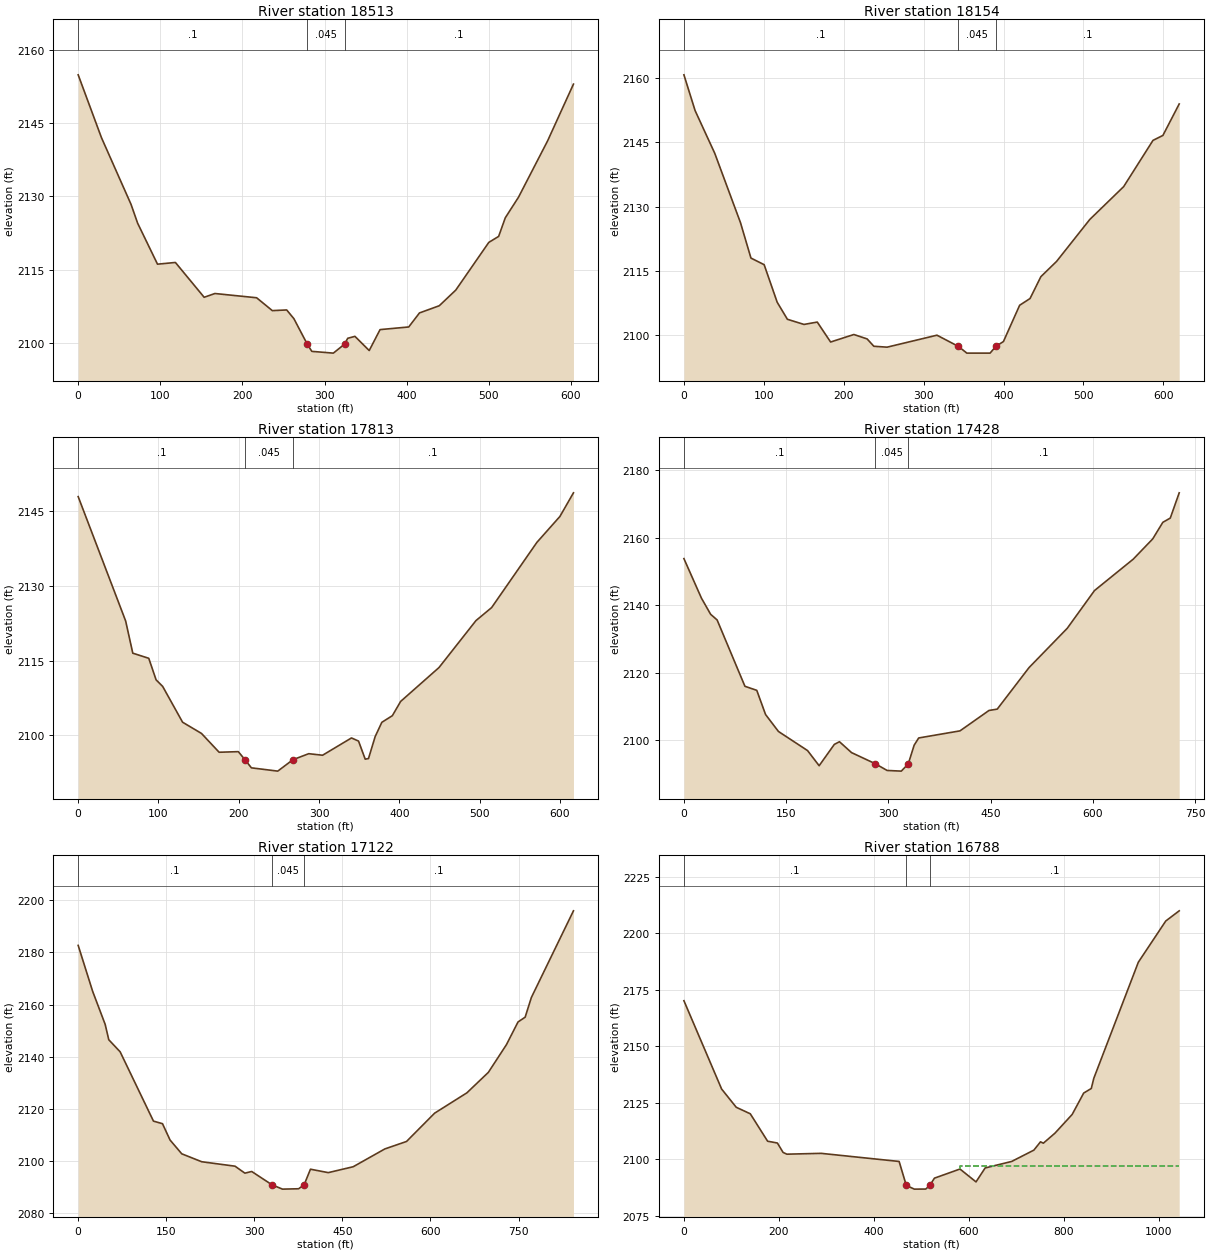
Type RM Length L Ch R = 1 ,18513   ,358.6,358.6,358.6
XS GIS Cut Line= 4
2200759.76195074 636853.414577612200854.41635374636853.087189545
2201147.38772431 636724.073996372201334.77377911636705.309417903
#Sta/Elev= 30
       0 2154.84    28.4 2141.97    64.4 2128.34    72.4  2124.5    96.6 2116.12
   118.4 2116.47   153.4 2109.35   166.5 2110.12   217.3 2109.25   236.4 2106.62
   253.9 2106.76   262.7 2104.97278.88332099.784   284.5 2098.29   310.7 2097.93
  324.382099.769   328.2 2100.96     337 2101.36   354.4 2098.46   367.6 2102.74
   402.5 2103.28   415.6 2106.15   439.7 2107.62   459.8 2110.82     500 2120.57
     512  2121.8   520.1 2125.61   536.2 2129.82   571.6 2141.33   603.1 2152.94
#Mann= 3 ,-1,0
       0      .1       0278.8833    .045       0  324.38      .1       0
Bank Sta=278.8833,324.38
XS Rating Curve= 0 ,0
Exp/Cntr=0.3,0.1

Type RM Length L Ch R = 1 ,18154   ,340.7,340.7,340.7
XS GIS Cut Line= 3
2200734.60042835637021.4065567132200827.77862389 637043.71870299
2201331.75317314637187.531752251
#Sta/Elev= 30
       0 2160.71      14 2152.37    38.6 2142.41    70.8 2126.24    83.9 2117.99
   100.4 2116.45   116.7 2107.71   129.5 2103.72   150.3 2102.52   166.9 2103.07
   183.6 2098.42   212.7 2100.17   229.3 2099.14   237.7 2097.43   254.3 2097.22
   316.7 2100.01  343.652097.388   354.1 2095.83   383.2 2095.83  390.322097.388
   399.9 2098.53   420.2 2106.99   433.2 2108.56   446.8 2113.66   466.4 2117.21
     508 2126.99   550.4 2134.65   587.1 2145.43   599.5 2146.58   619.9 2153.92
#Mann= 3 ,-1,0
       0      .1       0  343.65    .045       0  390.32      .1       0
Bank Sta=343.65,390.32
XS Rating Curve= 0 ,0
Exp/Cntr=0.3,0.1

Type RM Length L Ch R = 1 ,17813   ,385.2,385.2,385.2
XS GIS Cut Line= 4
2200637.28954671637267.1183814222200692.95727656637300.064588883
2200997.42567655637379.5899172382201198.51114968637505.694366487
#Sta/Elev= 30
       0 2147.93    59.1 2122.97      68  2116.5    87.9 2115.47      97 2111.15
   105.2 2109.83     130 2102.64   153.5 2100.39   175.5 2096.61   199.4 2096.73
  207.652095.118   215.7 2093.48   248.5 2092.82  267.452095.117   287.1 2096.32
   304.3 2096.01   340.3 2099.48   349.1 2098.85   357.4 2095.22   361.5 2095.35
   369.8 2099.76   378.1 2102.62   391.2 2103.95   401.5 2106.81   449.3 2113.62
   495.3 2123.04   514.8 2125.65   571.1 2138.73   599.8 2143.94   616.7 2148.69
#Mann= 3 ,-1,0
       0      .1       0  207.65    .045       0  267.45      .1       0
Bank Sta=207.65,267.45
XS Rating Curve= 0 ,0
Exp/Cntr(USF)=0,0
Exp/Cntr=0.3,0.1

Type RM Length L Ch R = 1 ,17428   ,305.8,305.8,305.8
XS GIS Cut Line= 3
2200501.70121044637400.131698503 2200715.2016612637735.702864171
2200932.86811195637982.363497003
#Sta/Elev= 30
       0 2153.76    25.7 2142.07    39.2 2137.29    48.7 2135.62    89.5    2116
   106.9 2114.79   119.8 2107.64   138.7 2102.63   181.4 2096.98   198.4  2092.5
   220.7 2098.81   228.2  2099.6   245.9 2096.38     281 2093.07   298.1  2091.1
   318.9  2090.9  329.132093.021   337.8 2098.57   344.5 2100.71   405.1 2102.81
   447.6 2108.84   459.7 2109.24   506.4 2121.53   562.4 2133.14   602.4 2144.31
   659.2 2153.59   687.8 2159.58   702.7  2164.5   713.6 2165.75   726.7 2173.22
#Mann= 3 ,-1,0
       0      .1       0     281    .045       0  329.13      .1       0
Bank Sta=281,329.13
XS Rating Curve= 0 ,0
Exp/Cntr=0.3,0.1

Type RM Length L Ch R = 1 ,17122   ,334.3,334.3,334.3
XS GIS Cut Line= 2
2200198.00649104637582.5230999972200751.22629403638219.323446268
#Sta/Elev= 30
       0 2182.66    24.7 2165.02      46 2152.38    52.1 2146.52    71.5 2141.87
   128.2 2115.34   143.6 2114.35   156.5 2108.08   176.4 2102.81   210.4 2099.77
   267.1 2098.07   283.9  2095.4   295.5 2096.04  329.892090.966   347.9 2089.28
   375.4 2089.42  384.872090.964   395.6 2096.91   425.9  2095.6   468.4 2097.86
   522.3 2104.68   559.2 2107.54   607.1 2118.39     662 2126.17   698.6 2134.02
   729.3  2144.6   749.1 2153.33   761.2 2155.14   771.8 2162.69   843.5  2195.9
#Mann= 3 ,-1,0
       0      .1       0  329.89    .045       0  384.87      .1       0
Bank Sta=329.89,384.87
XS Rating Curve= 0 ,0
Exp/Cntr=0.3,0.1

Type RM Length L Ch R = 1 ,16788   ,464.1,464.1,464.1
XS GIS Cut Line= 4
2199760.08988955637991.6922761132199925.56513285638068.116917919
2200324.86861389638089.6374918362200671.27337015638393.983099997
#Sta/Elev= 30
       0 2170.07    79.4 2131.01   110.2 2122.93   139.8 2120.05   176.3 2107.92
   196.9 2107.12   208.9 2102.95   216.9 2102.18     289 2102.55   453.3 2098.96
  468.432088.361   485.3 2086.72   509.4 2086.75  517.792088.357   527.8 2091.58
   581.5 2095.61   615.3 2089.92   634.5 2096.08   690.5 2098.97   737.2 2103.98
   751.1 2107.64   757.2 2107.05   781.5 2111.46   817.8 2119.75   842.1 2129.22
   858.1 2131.24   863.4 2135.75   957.2  2187.1    1015 2205.34  1043.3 2209.84
#Mann= 3 ,-1,0
       0      .1       0  468.43    .045       0  517.79      .1       0
#XS Ineff= 2 , 0
                           581.5            2097
Permanent Ineff=
       F       F
Bank Sta=468.43,517.79
XS Rating Curve= 0 ,0
Exp/Cntr=0.3,0.1

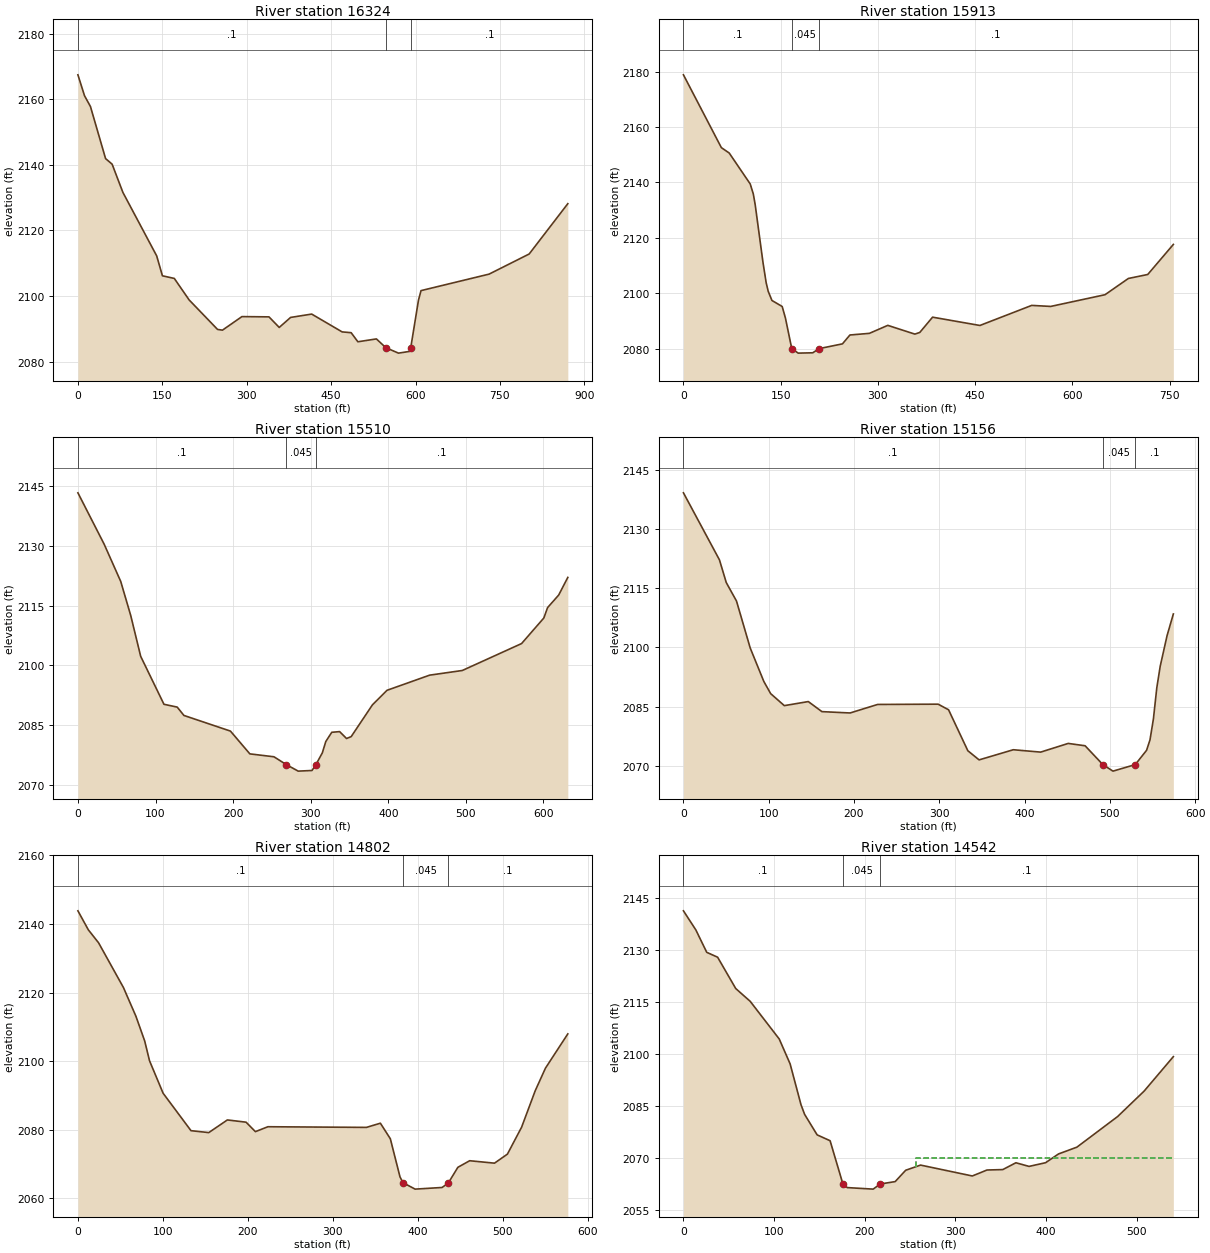
Type RM Length L Ch R = 1 ,16324   ,411.3,411.3,411.3
XS GIS Cut Line= 4
2199721.61219451 638063.507741092200072.65971539638297.539421678
2200062.43503032638507.713503759  2200202.172393638700.846444049
#Sta/Elev= 30
       0 2167.41    11.7 2161.06    22.3 2157.74    49.2 2141.87    60.8 2140.18
      80 2131.56     140 2112.23   150.2 2106.16   171.3 2105.36   197.7  2098.8
   248.2 2089.81   256.9 2089.59   291.5 2093.72   339.6 2093.64   357.8 2090.42
     378 2093.47   415.5 2094.49   469.6 2089.06   485.6 2088.82   497.6 2086.05
   530.5 2086.92   547.3 2084.25   569.7 2082.59   589.7 2083.12  591.542084.242
   605.3 2098.74   609.8 2101.64   730.8 2106.67     802  2112.8   870.7 2128.14
#Mann= 3 ,-1,0
       0      .1       0   547.3    .045       0  591.54      .1       0
Bank Sta=547.3,591.54
XS Rating Curve= 0 ,0
Exp/Cntr(USF)=0,0
Exp/Cntr=0.3,0.1

Type RM Length L Ch R = 1 ,15913   ,402.5,402.5,402.5
XS GIS Cut Line= 3
2199573.04941941638185.757714913     2199853.835638573.962843274
2200038.54746716638779.853073139
#Sta/Elev= 30
       0 2178.89    58.5 2152.58    70.6 2150.64     103 2139.47   107.8 2135.83
   110.7 2131.93   122.7 2111.12   127.6 2103.79   130.7 2100.73   136.5 2097.37
   152.3  2095.2   157.3 2091.04  167.092079.969     177 2078.35   199.5 2078.47
  209.192079.967   245.3  2081.7   256.8  2084.9   286.8 2085.49   315.2 2088.38
     357 2085.22   364.6 2085.83   384.3 2091.34   457.3 2088.34   537.2 2095.59
   566.5 2095.22   650.3 2099.45   686.3 2105.32   716.2 2106.76   755.7 2117.62
#Mann= 3 ,-1,0
       0      .1       0  167.09    .045       0  209.19      .1       0
Bank Sta=167.09,209.19
XS Rating Curve= 0 ,0
Exp/Cntr=0.3,0.1

Type RM Length L Ch R = 1 ,15510   ,353.9,353.9,353.9
XS GIS Cut Line= 4
2199419.42540477638493.6448304352199492.67005506 638684.39919391
2199652.17514221638762.106800474 2199788.8384312638971.033876715
#Sta/Elev= 30
       0 2143.31    33.8 2130.43    55.2 2121.06    68.1  2112.5    80.9 2102.27
   110.9 2090.23     128 2089.52   136.6 2087.43   196.6  2083.5   221.6 2077.78
   252.7 2077.05  268.732075.072   283.9 2073.45   301.7 2073.61   306.6 2075.04
     315 2078.03   319.5 2080.89   327.2  2083.2   337.3 2083.37   346.2 2081.64
   352.2 2082.11   379.6 2090.09   398.4 2093.74   453.3 2097.54   495.4 2098.71
   571.8 2105.47   600.5 2111.89   605.3 2114.49   619.6 2117.64   631.4 2122.08
#Mann= 3 ,-1,0
       0      .1       0  268.73    .045       0   306.6      .1       0
Bank Sta=268.73,306.6
XS Rating Curve= 0 ,0
Exp/Cntr=0.3,0.1

Type RM Length L Ch R = 1 ,15156   ,354.5,354.5,354.5
XS GIS Cut Line= 2
2199365.41486275638507.0513707022199399.76437339639080.497367772
#Sta/Elev= 30
       0 2139.19    42.2 2122.21    50.2 2116.45    62.2 2111.77    78.3 2099.86
    94.3 2091.36   102.3 2088.29   118.3 2085.25   146.4 2086.28   162.4 2083.73
   195.4 2083.39   227.7 2085.55   298.7 2085.62   310.9  2084.2   333.5 2073.82
   346.7  2071.5   386.8 2074.07   418.9 2073.47   451.2 2075.67     471 2075.08
  491.842070.304   503.7 2068.65  529.842070.305   543.1 2073.93   547.1 2076.56
   551.1 2081.85   555.1 2089.78   559.1 2095.25   567.1 2102.97   574.5 2108.49
#Mann= 3 ,-1,0
       0      .1       0  491.84    .045       0  529.84      .1       0
Bank Sta=491.84,529.84
XS Rating Curve= 0 ,0
Exp/Cntr(USF)=0,0
Exp/Cntr=0.3,0.1

Type RM Length L Ch R = 1 ,14802   ,260.3,260.3,260.3
XS GIS Cut Line= 4
2199320.91087944638504.9052582852199316.99709161638608.652086863
2199040.04866475638903.0248961332199034.69676418638971.405760623
#Sta/Elev= 30
       0 2143.86    12.3 2138.31    24.3 2134.55    53.6 2121.49    68.3 2113.11
    78.6 2105.91    84.3 2100.14   100.3 2090.67   133.1 2079.76     154  2079.2
   175.9 2082.89   197.9 2082.24   208.9 2079.48   223.6 2080.91   339.6 2080.72
     356 2081.94   367.7 2077.41   379.1 2066.28382.60492064.594   396.9 2062.72
   428.6  2063.2   435.9 2064.49   447.2 2069.08   461.1    2071   490.3 2070.29
   505.5 2072.92   522.2 2080.77   538.2 2091.38   550.3    2098   576.6 2107.98
#Mann= 3 ,-1,0
       0      .1       0382.6049    .045       0   435.9      .1       0
Bank Sta=382.6049,435.9
XS Rating Curve= 0 ,0
Exp/Cntr=0.3,0.1

Type RM Length L Ch R = 1 ,14542   ,379.8,379.8,379.8
XS GIS Cut Line= 4
2198970.07446808638447.4948906722198969.44133732638583.383616569
2198809.83967139638831.8543286122198841.89880674638936.332109328
#Sta/Elev= 30
       0 2141.31    13.7  2135.8    25.7 2129.35    37.7 2127.94    57.7 2118.91
    73.7 2115.21   105.7 2104.36   117.7 2097.19   129.7 2085.42   133.7 2082.63
   147.5 2076.73   161.8 2075.04  175.932062.573   180.8 2061.53   209.3 2061.09
   217.12062.572   233.6 2063.26   245.2 2066.53   261.6 2068.02   318.7 2064.88
   334.9  2066.6   352.3 2066.72   366.8 2068.69   381.3 2067.64   399.5  2068.7
   413.8 2071.23   434.1 2073.19     479 2082.01   508.2 2089.33   540.5 2099.28
#Mann= 3 ,-1,0
       0      .1       0  175.93    .045       0   217.1      .1       0
#XS Ineff= 1 ,-1
 256.379  540.49    2070
Permanent Ineff=
       F
Bank Sta=175.93,217.1
XS Rating Curve= 0 ,0
Exp/Cntr=0.3,0.1

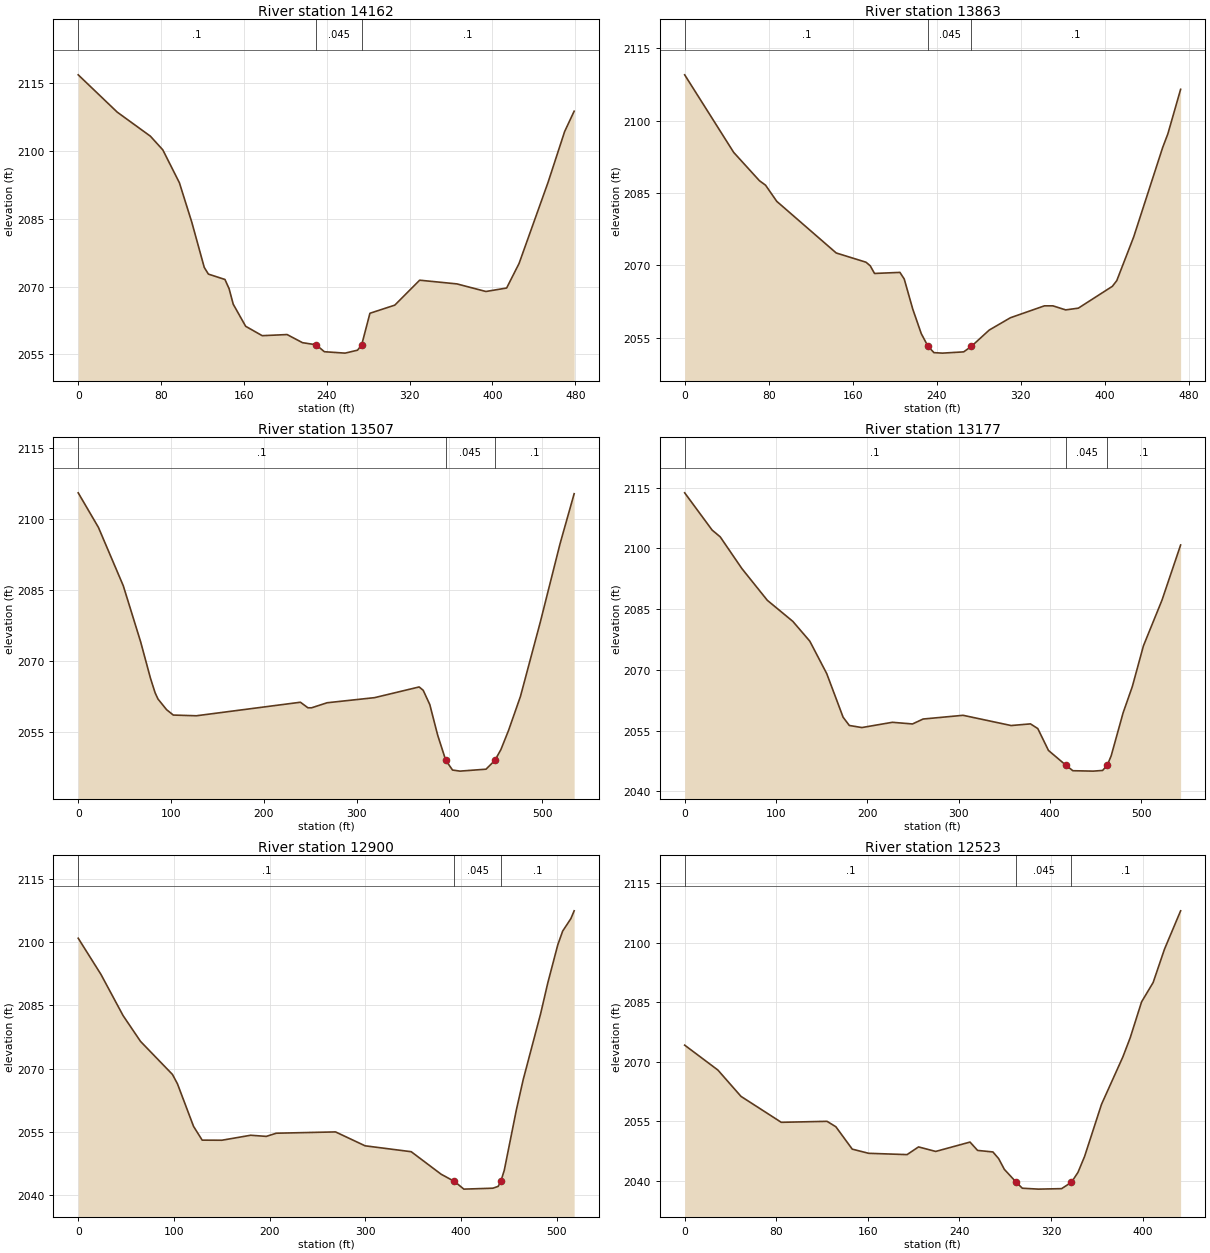
Type RM Length L Ch R = 1 ,14162   ,298.5,298.5,298.5
XS GIS Cut Line= 2
2198579.04838889638475.5012884252198575.08521573638954.423333915
#Sta/Elev= 30
       0 2116.89    37.7 2108.63    69.7 2103.31    81.7 2100.28    97.7 2093.01
   109.7 2084.26   121.7 2074.28   125.7 2072.79   141.7  2071.6   145.7 2069.56
   149.7 2066.12   161.7 2061.24   177.7 2059.16   201.7 2059.41   216.6 2057.61
   229.7 2057.15   237.7 2055.61   257.7  2055.3   269.7 2055.95   273.7  2057.1
   281.7 2064.12   305.7 2065.92   329.7 2071.44   365.7 2070.62   393.7 2068.94
   413.7 2069.71   425.7 2075.14   453.7 2093.09   469.7 2104.33   478.9 2108.84
#Mann= 3 ,-1,0
       0      .1       0   229.7    .045       0   273.7      .1       0
Bank Sta=229.7,273.7
XS Rating Curve= 0 ,0
Exp/Cntr=0.3,0.1

Type RM Length L Ch R = 1 ,13863   ,356.5,356.5,356.5
XS GIS Cut Line= 4
2198278.63451223638455.5271047432198257.64314462638553.804871295
2198304.39664521638863.9046201272198293.90096141638921.153804526
#Sta/Elev= 30
       0  2109.5    46.7  2093.4    71.2 2087.53      77 2086.61    87.7 2083.25
   144.3 2072.54   172.7 2070.62   176.7 2069.88   180.8 2068.29     205 2068.51
   209.1 2067.13   217.2  2060.9   225.3 2055.81  231.732053.172   237.4 2051.86
   245.5 2051.76   265.7 2052.02  273.092053.175     290 2056.54   310.2  2059.1
   342.6 2061.57   350.7 2061.57   362.8 2060.73   374.9 2061.09   407.3 2065.62
   411.5  2066.8   427.6 2075.86   455.2 2094.42   460.1 2097.22   472.3 2106.49
#Mann= 3 ,-1,0
       0      .1       0  231.73    .045       0  273.09      .1       0
Bank Sta=231.73,273.09
XS Rating Curve= 0 ,0
Exp/Cntr(USF)=0,0
Exp/Cntr=0.3,0.1

Type RM Length L Ch R = 1 ,13507   ,329.4,329.4,329.4
XS GIS Cut Line= 4
2197964.64275413638319.6930413732197915.10219129638401.140379563
2197927.50618125638765.6268535742197901.05500886638835.386209796
#Sta/Elev= 30
       0  2105.5    21.8 2098.19    48.6 2085.85    67.3 2074.01    77.9 2066.31
    82.9 2063.23      86 2061.92    95.3 2059.66   102.5 2058.53   127.4 2058.38
   239.5 2061.24   247.6 2060.07   251.5 2060.06   268.3 2061.13   319.5 2062.21
   367.5 2064.47   371.9 2063.76     379 2060.74   387.5 2054.27  396.222048.966
   403.5 2046.91   411.6 2046.68   439.6 2047.09   449.22048.966   455.6 2051.22
   463.8 2055.24   476.7 2062.46   498.1 2078.17   519.4 2094.74   534.6 2105.31
#Mann= 3 ,-1,0
       0      .1       0  396.22    .045       0   449.2      .1       0
Bank Sta=396.22,449.2
XS Rating Curve= 0 ,0
Exp/Cntr=0.3,0.1

Type RM Length L Ch R = 1 ,13177   ,277.7,277.7,277.7
XS GIS Cut Line= 2
2197851.96457211 638215.26834752 2197575.4800136638682.711435569
#Sta/Elev= 30
       0 2113.76    30.1 2104.54    38.9 2102.88    62.6 2095.05    90.5 2087.19
   118.4 2081.99     137  2077.1   155.6 2069.05   173.5 2058.28   180.3 2056.25
     194 2055.73   227.4 2057.03   249.5 2056.62   261.1 2057.84   304.9 2058.76
   357.5 2056.23   378.7 2056.64   386.7 2055.48   398.4 2050.07  417.252046.467
   425.1 2045.06   447.4 2044.96   457.7 2045.13  462.822046.466     467  2048.7
   480.1 2059.36   490.2 2065.86   502.4 2075.95   522.7 2087.23   543.1 2100.86
#Mann= 3 ,-1,0
       0      .1       0  417.25    .045       0  462.82      .1       0
Bank Sta=417.25,462.82
XS Rating Curve= 0 ,0
Exp/Cntr=0.3,0.1

Type RM Length L Ch R = 1 ,12900   ,376.9,376.9,376.9
XS GIS Cut Line= 2
2197661.29747379638116.8027637122197334.02296964638518.501207582
#Sta/Elev= 30
       0 2100.87    23.8 2092.29    46.9 2082.54    65.1 2076.44    98.5  2068.6
   103.7 2066.38   120.5 2056.31   129.5 2053.05   150.1 2053.03   180.2 2054.21
   196.5 2053.94   206.9 2054.69   268.8    2055   299.7 2051.71   347.9 2050.31
   379.2 2044.97  393.052043.275   402.9 2041.45   433.2 2041.67   438.7  2042.1
  441.472043.276   445.1 2045.91   457.7 2060.18   464.8 2067.32   483.1 2083.02
   490.6 2090.32     501 2099.31   506.1 2102.56   514.7 2105.52   518.1 2107.36
#Mann= 3 ,-1,0
       0      .1       0  393.05    .045       0  441.47      .1       0
Bank Sta=393.05,441.47
XS Rating Curve= 0 ,0
Exp/Cntr(USF)=0,0
Exp/Cntr=0.3,0.1

Type RM Length L Ch R = 1 ,12523   ,154.3,154.3,154.3
XS GIS Cut Line= 2
2197411.76529685637959.8296246192197064.88151279638219.435175914
#Sta/Elev= 30
       0 2074.23      29 2067.96    49.2 2061.32    84.4 2054.78   124.4 2055.03
   132.1 2053.66   146.4 2048.02   160.7 2046.97   194.3 2046.64   204.3 2048.58
   219.3 2047.44   249.3  2049.8   255.9  2047.7   269.3 2047.31   274.3 2045.64
   279.3 2042.92  289.85 2039.63     295 2038.17     309 2037.94   329.3 2038.06
   337.9 2039.66   343.6 2042.15   349.4 2046.18   364.2 2059.33   382.8 2071.24
   389.2 2076.05   399.2 2085.15   409.3 2090.02   419.2 2098.42   433.3 2108.09
#Mann= 3 ,0,0
       0      .1       0  289.85    .045       0   337.9      .1       0
Bank Sta=289.85,337.9
XS Rating Curve= 0 ,0
Exp/Cntr=0.3,0.1

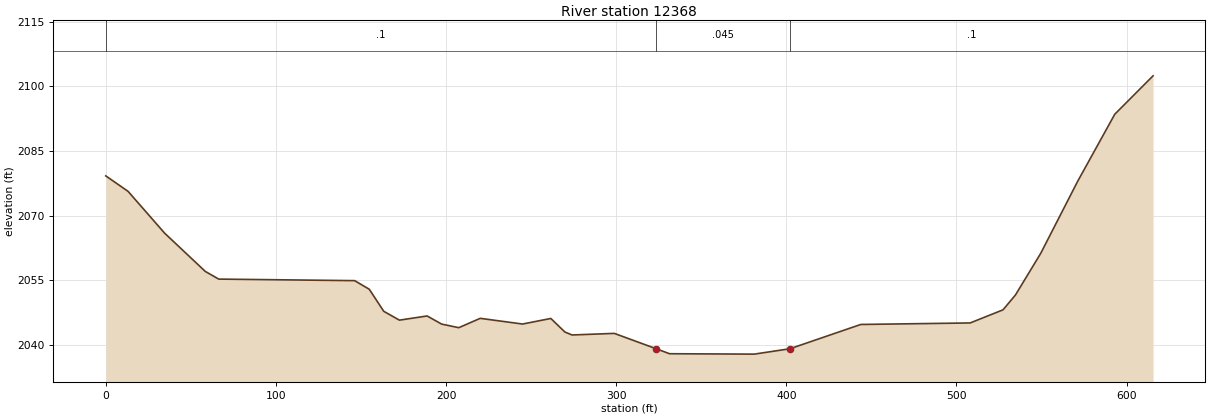
Type RM Length L Ch R = 1 ,12368   ,87,87,87
XS GIS Cut Line= 6
2197374.22615657637884.7374910432197195.02534353638041.116853292
2197062.43947922638007.3347312032196992.04464699637973.506047139
2196936.45602769637942.6011536072196877.93264248638022.349862436
#Sta/Elev= 30
       0 2079.25    13.1 2075.66    34.6 2065.96    58.5 2057.09    66.4 2055.31
   146.3 2054.95   154.9 2052.95   163.4 2047.84   172.6 2045.79   188.9 2046.76
   197.4 2044.88   207.5 2044.04   220.1 2046.21     245 2044.89   261.6 2046.18
   269.9 2043.03   274.1 2042.35   298.9 2042.72   323.4 2039.18   331.4    2038
   381.2 2037.91   402.2 2039.16   443.8 2044.79   508.1 2045.14   527.4 2048.18
   534.7 2051.61   549.6  2061.3   571.2 2077.92   593.1 2093.54   615.6 2102.45
#Mann= 3 ,0,0
       0      .1       0   323.4    .045       0   402.2      .1       0
Bank Sta=323.4,402.2
XS Rating Curve= 0 ,0
Exp/Cntr(USF)=0,0
Exp/Cntr=0.3,0.1