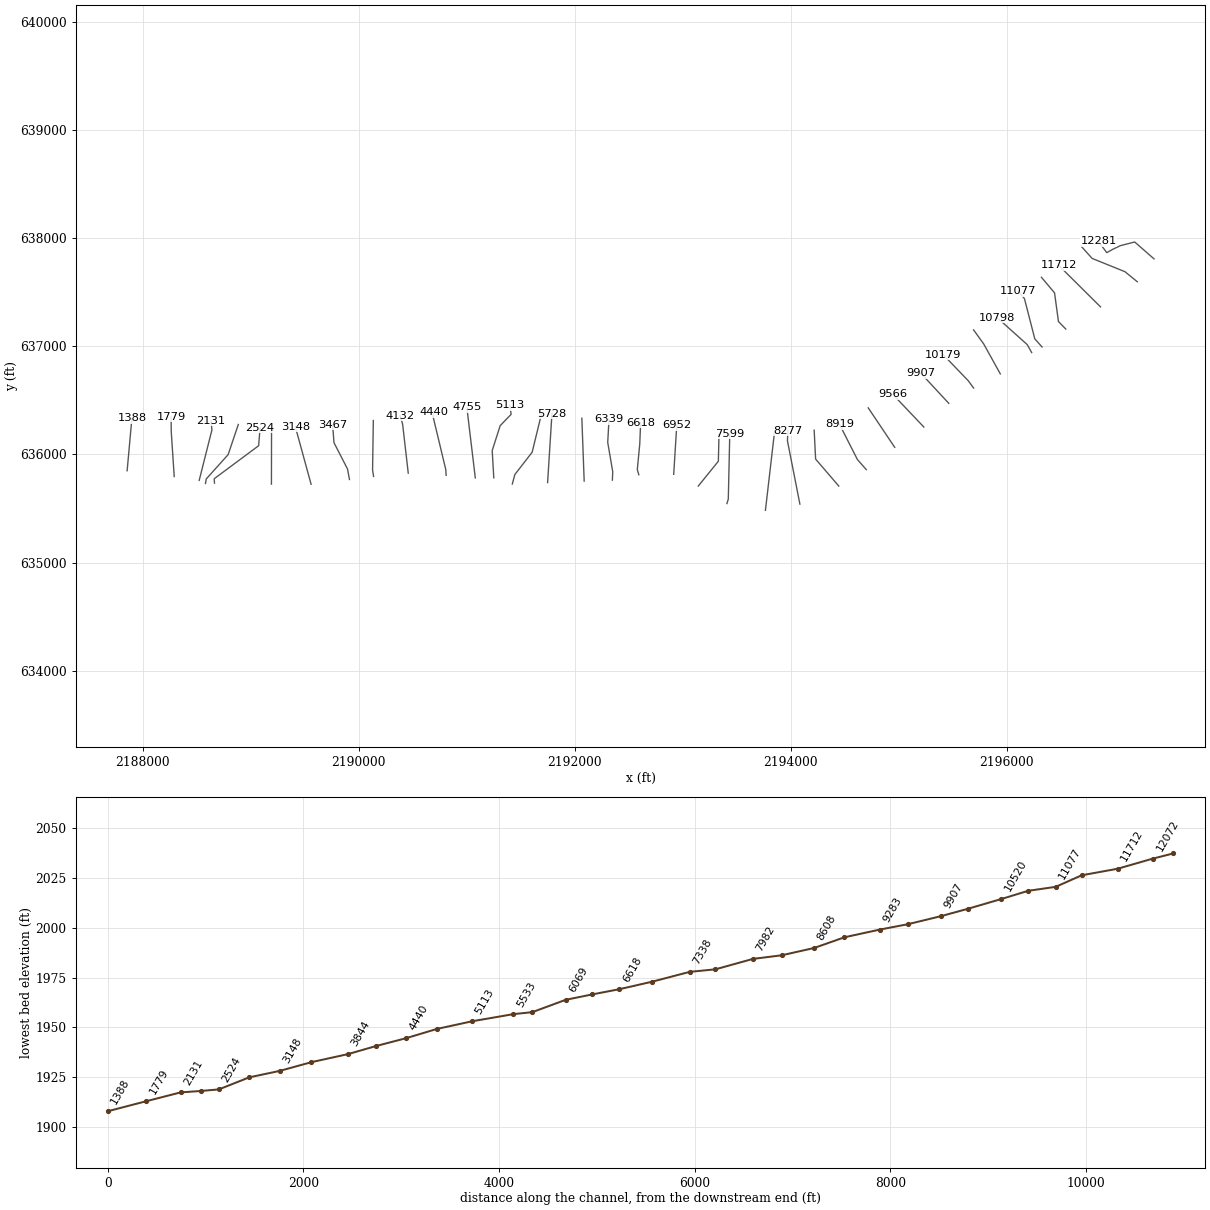
HEC-RAS study LFRFBUCRV.prj: LFRFBUCRV

--- LFRFBUCRV.g01 (geometry) --- (continued)

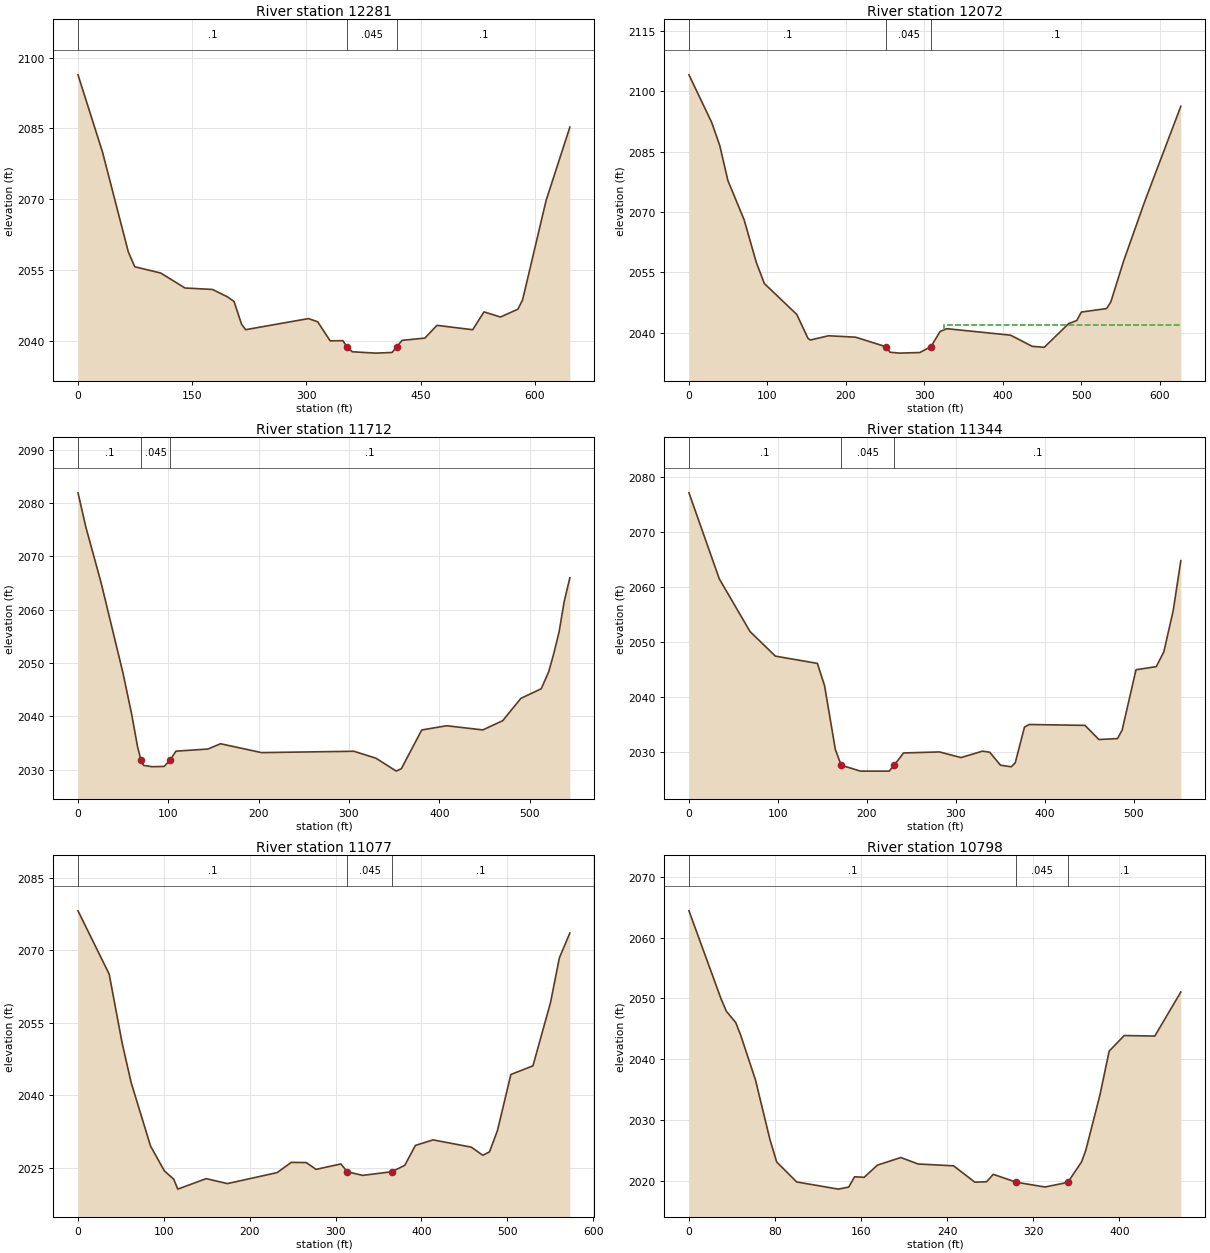
Type RM Length L Ch R = 1 ,12281   ,209,209,209
XS GIS Cut Line= 6
2197362.10433376637809.8504128732197182.90352072637966.229775122
2197050.31765641637932.4476530332196979.92282418637898.618968969
2196924.33420487637867.7140754372196847.19812919 637971.80245643
#Sta/Elev= 30
       0 2096.35    32.1 2080.06    66.1 2058.88    74.6 2055.74   108.7 2054.41
   140.6 2051.25   176.7 2050.94   196.5 2049.36     205  2048.4   214.9 2043.58
   220.2 2042.43   302.8 2044.78   314.9  2044.1   331.3 2040.07   347.9 2040.11
   353.4 2038.82   360.4 2037.76   390.9 2037.47   412.6 2037.61  418.66 2038.81
   425.8 2040.17   455.7 2040.65   471.6 2043.35   518.5 2042.42   533.4  2046.2
     555 2045.11   577.9 2046.76   584.1 2048.74     615 2069.77   646.2 2085.28
#Mann= 3 ,0,0
       0      .1       0   353.4    .045       0  418.66      .1       0
Bank Sta=353.4,418.66
XS Rating Curve= 0 ,0
Exp/Cntr(USF)=0,0
Exp/Cntr=0.3,0.1

Type RM Length L Ch R = 1 ,12072   ,360.7,360.7,360.7
XS GIS Cut Line= 4
2197206.64392129637598.5161049852197092.52336397637691.526859119
2196788.74047838637814.3599667932196687.14796622637927.540268105
#Sta/Elev= 30
       0 2104.14      29 2092.28    39.3 2086.51    49.6 2077.85    70.3 2068.07
    85.7 2057.54    96.1 2052.19   137.4 2044.52   151.8 2038.54   154.9 2038.15
   177.8  2039.2   212.3 2038.85  251.51 2036.45   256.3  2035.1   268.4 2034.88
   294.3 2035.03   308.5 2036.51   320.2 2040.29   328.8 2040.96   409.9 2039.35
   437.6 2036.57   452.9 2036.33   484.1 2042.24   494.3 2042.98   500.2  2045.1
   532.4 2045.97   537.8 2047.63   553.8 2057.64   580.8 2072.53     627 2096.31
#Mann= 3 ,0,0
       0      .1       0  251.51    .045       0   308.5      .1       0
#XS Ineff= 2 , 0
                           324.5            2042
Permanent Ineff=
       F       F
Bank Sta=251.51,308.5
XS Rating Curve= 0 ,0
Exp/Cntr=0.3,0.1

Type RM Length L Ch R = 1 ,11712   ,368,368,368
XS GIS Cut Line= 2
2196866.34271395637366.020974604 2196479.7272624 637749.63914777
#Sta/Elev= 30
       0 2081.89     8.7 2075.47    25.6 2065.03    49.9 2048.07    59.4 2040.43
      66 2034.27   69.722031.816    72.6 2030.84    81.9 2030.59    95.3 2030.64
   101.9  2031.8   108.4  2033.5   143.9  2033.9   157.8 2034.89   203.2 2033.23
   305.5 2033.48   329.9 2032.18   352.4 2029.76   358.1 2030.24   380.6 2037.47
   408.2 2038.26   448.2 2037.48   470.2  2039.2   490.3 2043.38   512.9 2045.19
   521.3 2048.43     527 2051.93   532.7 2055.86   538.3 2061.51   544.6 2065.99
#Mann= 3 ,-1,0
       0      .1       0   69.72    .045       0   101.9      .1       0
Bank Sta=69.72,101.9
XS Rating Curve= 0 ,0
Exp/Cntr=0.3,0.1

Type RM Length L Ch R = 1 ,11344   ,266.8,266.8,266.8
XS GIS Cut Line= 4
  2196544.938378637160.7413842392196477.19350979637230.394558592
2196440.93569301637495.6491129772196319.75825269637639.726227049
#Sta/Elev= 30
       0  2077.2    34.1 2061.52    68.7 2051.91    97.2 2047.43   144.4 2046.11
   152.5 2042.03   164.6 2030.43  171.112027.557   192.8 2026.47   225.1 2026.47
  230.762027.547   241.3 2029.78   281.7 2029.97   305.9 2028.94   330.1 2030.11
   338.2 2029.92   350.3 2027.55   362.4 2027.26   366.9 2027.98   377.3  2034.5
   382.6 2034.97   445.3 2034.81     461 2032.23   481.9  2032.4   487.1 2033.94
   502.7 2044.95   525.5 2045.52     534 2048.22   544.6 2055.77   553.1 2064.84
#Mann= 3 ,-1,0
       0      .1       0  171.11    .045       0  230.76      .1       0
Bank Sta=171.11,230.76
XS Rating Curve= 0 ,0
Exp/Cntr(USF)=0,0
Exp/Cntr=0.3,0.1

Type RM Length L Ch R = 1 ,11077   ,279.5,279.5,279.5
XS GIS Cut Line= 4
2196325.01624349636994.7749710462196258.25819445637070.130037815
2196162.32299559 637442.216540872196107.03916312637510.692497035
#Sta/Elev= 30
       0 2078.13    36.3 2065.06    51.3 2050.91    61.8 2042.71    84.5 2029.53
   100.7 2024.38   111.5 2022.69   116.2 2020.64   149.3 2022.81     174 2021.78
   231.9 2024.05   248.4 2026.16   265.8 2026.13   277.3 2024.72   306.2 2025.84
   313.72024.227   331.5 2023.48   365.4 2024.23   380.6 2025.55     393 2029.67
   413.6 2030.81   458.2 2029.31   471.5 2027.63   479.3 2028.33   488.6 2032.77
   504.2 2044.32   529.9 2046.11   550.4  2059.2   560.7 2068.42   572.9 2073.55
#Mann= 3 ,-1,0
       0      .1       0   313.7    .045       0   365.4      .1       0
Bank Sta=313.7,365.4
XS Rating Curve= 0 ,0
Exp/Cntr=0.3,0.1

Type RM Length L Ch R = 1 ,10798   ,277.5,277.5,277.5
XS GIS Cut Line= 3
2196229.11371073 636943.194483522196188.08512857637016.664270167
2195910.42658424637265.698222305
#Sta/Elev= 30
       0 2064.39    29.8 2049.94    34.7  2047.9    43.5 2046.02    48.1 2043.94
    61.8 2036.61    75.3 2026.78    81.5 2023.13   100.1 2019.84   138.8 2018.66
   148.5    2019   153.9 2020.69   162.8  2020.6   175.1  2022.6   196.9 2023.85
     213 2022.79   245.9 2022.49   265.7  2019.8   276.6 2019.87   282.8 2021.09
   304.3 2019.79   330.9 2019.01  352.082019.771   364.9 2023.15   368.8 2025.04
   381.9  2034.1   390.5 2041.33   404.5  2043.9   432.9 2043.81   457.1 2051.05
#Mann= 3 ,-1,0
       0      .1       0   304.3    .045       0  352.08      .1       0
Bank Sta=304.3,352.08
XS Rating Curve= 0 ,0
Exp/Cntr(USF)=0,0
Exp/Cntr=0.3,0.1

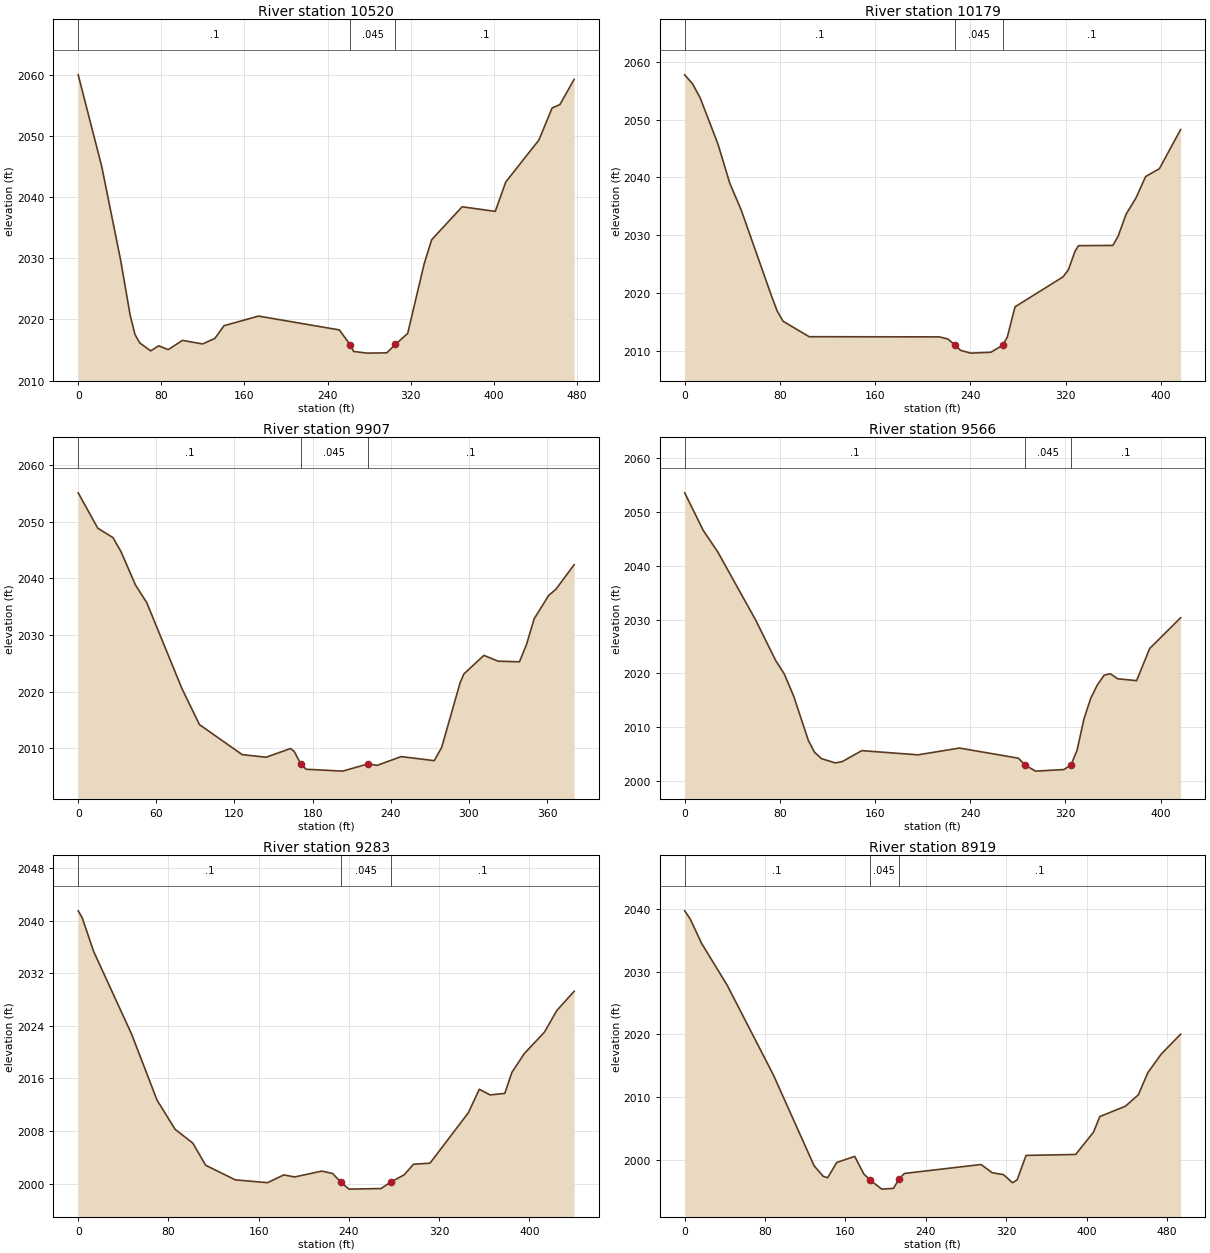
Type RM Length L Ch R = 1 ,10520   ,340.8,340.8,340.8
XS GIS Cut Line= 3
2195939.13945997636745.4358114062195785.44146268637022.663667572
2195691.81977002637152.645679089
#Sta/Elev= 30
       0 2059.95    22.6 2045.01    40.9 2029.62      50 2020.69    54.6 2017.56
    59.2 2016.17    69.7 2014.87    77.5  2015.7    86.6 2015.07   100.3 2016.58
   119.7    2016   131.5  2016.9   140.3 2018.98   173.5 2020.55   251.3 2018.29
   261.8 2015.84     265 2014.77   278.3  2014.5     297 2014.55   305.1 2015.91
     317 2017.71   332.8 2029.03   340.1 2033.02   369.4  2038.4   401.3 2037.65
   411.4 2042.45   443.3 2049.31     456 2054.53   463.5  2055.1   477.2 2059.21
#Mann= 3 ,-1,0
       0      .1       0   261.8    .045       0   305.1      .1       0
Bank Sta=261.8,305.1
XS Rating Curve= 0 ,0
Exp/Cntr=0.3,0.1

Type RM Length L Ch R = 1 ,10179   ,272.6,272.6,272.6
XS GIS Cut Line= 3
2195692.14934413 636614.764417542195641.49677357636683.086489457
2195411.79325592636922.213741167
#Sta/Elev= 30
       0 2057.74     6.7 2056.16      13 2053.76    27.9  2045.8    37.9 2038.99
    47.5 2034.35    72.7 2019.63    77.7 2016.89    82.7 2015.11   104.6 2012.44
     214 2012.41   221.1 2012.04  227.482010.942   231.7 2010.09   240.2  2009.6
   257.2 2009.75  267.052010.954     271 2012.37   277.5 2017.61   317.9  2022.8
   322.3    2024   327.9 2027.21   330.8 2028.19   359.7 2028.23   364.1 2029.82
   370.8 2033.64   378.9 2036.36   387.2 2040.14   398.8 2041.51   416.6 2048.28
#Mann= 3 ,-1,0
       0      .1       0  227.48    .045       0  267.05      .1       0
Bank Sta=227.48,267.05
XS Rating Curve= 0 ,0
Exp/Cntr(USF)=0,0
Exp/Cntr=0.3,0.1

Type RM Length L Ch R = 1 ,9907    ,341,341,341
XS GIS Cut Line= 2
2195462.36634394636472.9372076042195203.26023813636751.993210973
#Sta/Elev= 30
       0 2055.15      15  2048.9    26.7 2047.23    32.9 2044.73      44 2038.84
    52.7 2035.69    79.6 2020.55    93.1 2014.15   125.9 2008.84   144.3 2008.38
   163.1 2009.92   165.9 2009.39  170.822007.222     175 2006.25   203.1 2005.92
   222.5  2007.2   229.6 2006.94     248 2008.49   273.4 2007.77   279.1 2010.13
   293.2 2021.53   296.1  2023.1   311.5  2026.4   322.4 2025.37   338.8 2025.26
   344.2  2028.3   350.1 2032.87   361.2 2036.99   366.8 2038.09   380.8 2042.44
#Mann= 3 ,-1,0
       0      .1       0  170.82    .045       0   222.5      .1       0
Bank Sta=170.82,222.5
XS Rating Curve= 0 ,0
Exp/Cntr=0.3,0.1

Type RM Length L Ch R = 1 ,9566    ,282.8,282.8,282.8
XS GIS Cut Line= 2
2195231.30146268636253.7603127642194944.13694981636556.052479632
#Sta/Elev= 30
       0 2053.58    15.7 2046.56    27.8  2042.6    59.9 2029.84    76.4 2022.45
    83.9 2019.83    91.7 2015.74     104 2007.53   109.1 2005.37     115 2004.16
   126.5 2003.37   132.3 2003.59   148.9 2005.65   196.2 2004.87     231 2006.13
   280.6 2004.24   286.1 2002.98   294.9 2001.84   318.7 2002.13   324.7 2002.96
   329.8 2005.68   335.7 2011.58   341.3 2015.36   346.8 2017.83   352.6 2019.67
   357.8 2019.95     364 2019.01   379.9 2018.66   390.9 2024.64   416.9 2030.36
#Mann= 3 ,-1,0
       0      .1       0   286.1    .045       0   324.7      .1       0
Bank Sta=286.1,324.7
XS Rating Curve= 0 ,0
Exp/Cntr=0.3,0.1

Type RM Length L Ch R = 1 ,9283    ,364.1,364.1,364.1
XS GIS Cut Line= 2
2194961.80995467636065.8319086882194716.79286917636431.001603418
#Sta/Elev= 30
       0 2041.48     3.6  2040.4    13.7  2035.3    47.4 2022.72    69.9 2012.71
    85.9 2008.28   101.6 2006.18   113.1  2002.8   139.3 2000.59   167.9 2000.16
   182.3 2001.34   191.9 2001.03     216 2001.92   225.6 2001.56   232.7 2000.27
   240.1 1999.18   268.6 1999.27   277.5 2000.29     289 2001.34   297.3 2002.96
     312 2003.13     346  2010.8   355.7 2014.36   365.3  2013.5   378.3 2013.73
   384.6 2016.93   395.6 2019.78   413.5 2023.05   424.5 2026.35   439.8 2029.25
#Mann= 3 ,-1,0
       0      .1       0   232.7    .045       0   277.5      .1       0
Bank Sta=232.7,277.5
XS Rating Curve= 0 ,0
Exp/Cntr(USF)=0,0
Exp/Cntr=0.3,0.1

Type RM Length L Ch R = 1 ,8919    ,311.2,311.2,311.2
XS GIS Cut Line= 3
2194698.48816958635859.7789972842194616.66569481635952.747099998
2194449.11457599636282.216390766
#Sta/Elev= 30
       0 2039.68     5.5 2038.39    16.8  2034.5    42.3 2027.81    88.3 2013.49
   128.8 1999.01   137.8 1997.33   142.3  1997.1   151.3 1999.53   169.2  2000.5
   178.2 1997.71     184  1996.8   196.1 1995.28   207.8  1995.4     213 1996.84
   218.6 1997.78   294.9 1999.21     306  1997.9   317.3 1997.59   326.3  1996.3
   330.8 1996.75   339.7 2000.66   389.1 2000.81   406.8 2004.37   413.1 2006.86
   438.5  2008.5   451.4 2010.32   460.9 2013.87   474.4 2016.86   493.5    2020
#Mann= 3 ,-1,0
       0      .1       0     184    .045       0     213      .1       0
Bank Sta=184,213
XS Rating Curve= 0 ,0
Exp/Cntr=0.3,0.1

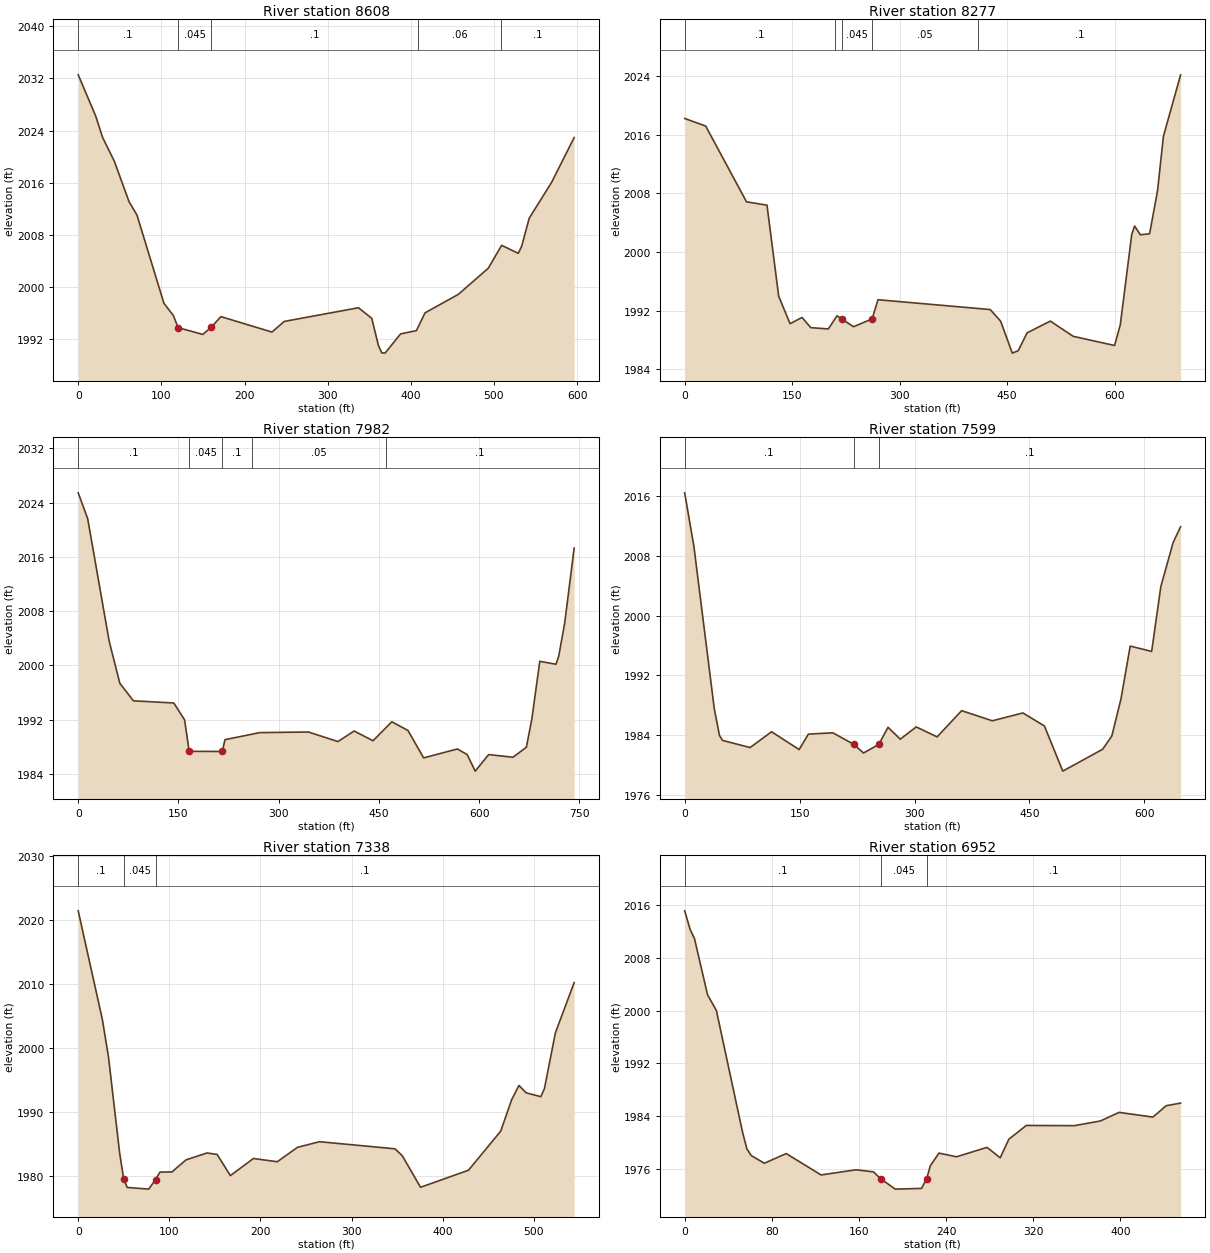
Type RM Length L Ch R = 1 ,8608    ,330.8,330.8,330.8
XS GIS Cut Line= 3
2194443.98136024 635707.572124172194229.71535293635957.042457496
2194216.29941181636224.298460942
#Sta/Elev= 30
       0 2032.56    20.9 2026.28    29.4 2022.94    43.6 2019.26    61.1 2013.12
    70.7 2011.04   103.1 1997.52   114.5 1995.64   120.1 1993.79   149.8 1992.75
   159.8 1993.83   171.6 1995.48     233 1993.11   247.8 1994.74     337 1996.84
     353 1995.22     361 1991.06     365 1989.92     369 1989.88   387.7 1992.83
   406.7 1993.33   417.1 1996.06   457.2  1998.9   493.2 2002.91   509.2 2006.41
   529.2 2005.19   533.2 2006.24   542.4 2010.58   569.3 2016.07   596.4 2022.94
#Mann= 5 ,-1,0
       0      .1       0   120.1    .045       0   159.8      .1       0
  408.85     .06       0  508.85      .1       0
Bank Sta=120.1,159.8
XS Rating Curve= 0 ,0
Exp/Cntr=0.3,0.1

Type RM Length L Ch R = 1 ,8277    ,295.1,295.1,295.1
XS GIS Cut Line= 3
2194084.22472056635540.4587349812193968.78397836636127.086180063
2193973.49584538636221.323520638
#Sta/Elev= 30
       0 2018.21    29.3 2017.18    86.3 2006.85   114.9 2006.39   131.2 1993.99
   147.1 1990.23   163.8 1991.09     176 1989.69   200.5 1989.52   212.7 1991.31
   219.1 1990.88   235.7 1989.82   261.6 1990.88   269.8  1993.5   426.5 1992.16
     441 1990.57   457.3 1986.22   465.5 1986.55   477.9 1988.98   510.3 1990.59
   542.3 1988.51     600 1987.26     608 1990.08     624 2002.41     628 2003.55
     636 2002.35   648.9 2002.49     660 2008.37   668.2 2015.78   692.2 2024.16
#Mann= 5 ,-1,0
       0      .1       0     210     .05       0   219.1    .045       0
   261.6     .05       0     410      .1       0
Bank Sta=219.1,261.6
XS Rating Curve= 0 ,0
Exp/Cntr(USF)=0,0
Exp/Cntr=0.3,0.1

Type RM Length L Ch R = 1 ,7982    ,382.3,382.3,382.3
XS GIS Cut Line= 2
 2193765.2194905635483.0434538832193850.78527137636220.148404345
#Sta/Elev= 30
       0 2025.44    14.2 2021.62    46.4 2003.52    62.3 1997.34    82.7 1994.76
   143.1 1994.44   159.2 1991.94  166.08 1987.31   215.6 1987.29   219.6 1989.03
   271.6 1990.07   344.4 1990.16   388.7 1988.75   412.9 1990.31   441.1 1988.87
   469.3 1991.67   493.4 1990.39   516.9 1986.34   567.4 1987.66     582 1986.83
   594.1 1984.39   614.2 1986.83   650.5 1986.44   670.6 1987.91   678.7 1992.02
   690.7 2000.59   714.9 2000.15     719 2001.33     728 2006.26   742.1 2017.29
#Mann= 5 ,-1,0
       0      .1       0  166.08    .045       0   215.6      .1       0
     260     .05       0     460      .1       0
Bank Sta=166.08,215.6
XS Rating Curve= 0 ,0
Exp/Cntr=0.3,0.1

Type RM Length L Ch R = 1 ,7599    ,261.7,261.7,261.7
XS GIS Cut Line= 3
2193408.93790027635545.6850522532193421.58131482635587.239265919
2193435.30486974636190.941531231
#Sta/Elev= 30
       0 2016.48      12 2009.33    38.6 1987.56    45.4 1983.95    49.4 1983.28
    85.4 1982.32   113.4 1984.44   149.4 1982.05   161.4 1984.12   193.4  1984.3
  220.731982.746   233.4 1981.59   253.4 1982.74   265.4 1985.04   281.4 1983.44
   302.2 1985.09   329.5 1983.75   361.5 1987.27   401.5 1985.91   441.5 1986.96
   469.5 1985.22   493.5 1979.16   545.5 1982.09   557.5 1983.87   569.5 1988.86
   581.5 1995.93   609.5 1995.21   621.5 2003.92   637.5  2009.8   647.3 2011.94
#Mann= 3 ,-1,0
       0      .1       0  220.73    .045       0   253.4      .1       0
Bank Sta=220.73,253.4
XS Rating Curve= 0 ,0
Exp/Cntr=0.3,0.1

Type RM Length L Ch R = 1 ,7338    ,385.2,385.2,385.2
XS GIS Cut Line= 3
2193143.49498465635707.4041040252193329.52866727635937.143020094
     2193335.612636185.724161934
#Sta/Elev= 30
       0 2021.39    26.5 2004.41    33.2 1998.59    45.6 1983.41      501979.431
    53.8 1978.15    77.4 1977.89   84.861979.382    89.8 1980.56   102.8 1980.57
   118.3 1982.46   141.3 1983.54   152.5 1983.31     167    1980   192.3 1982.68
   218.5 1982.17   240.6 1984.42   264.8  1985.3   347.7 1984.19   355.7  1983.1
   375.7 1978.18   428.3 1980.84   463.7 1986.95   475.7 1991.86   483.7 1994.09
   491.7 1992.94   507.7 1992.34   511.7 1993.61   523.7 2002.31   544.3 2010.17
#Mann= 3 ,-1,0
       0      .1       0      50    .045       0   84.86      .1       0
Bank Sta=50,84.86
XS Rating Curve= 0 ,0
Exp/Cntr=0.3,0.1

Type RM Length L Ch R = 1 ,6952    ,334.6,334.6,334.6
XS GIS Cut Line= 2
2192916.24771159 635816.184172982192944.58605786 636270.45645119
#Sta/Elev= 30
       0 2015.12       5 2012.31       9 2010.91      21 2002.39    29.1 2000.02
    53.1 1981.58    57.1 1979.05    61.1 1978.03    73.1 1976.86    93.2 1978.33
   125.2 1975.09   157.3 1975.87   173.3 1975.56  179.791974.525   193.3 1972.94
   217.4 1973.05  222.141974.512   225.4 1976.46   233.4  1978.4   249.5 1977.84
   277.5 1979.27   289.6 1977.69   297.6 1980.52   313.6 1982.59   357.7 1982.56
   381.6 1983.27   398.7 1984.57   429.8 1983.86   441.9 1985.58   455.2 1985.98
#Mann= 3 ,-1,0
       0      .1       0  179.79    .045       0  222.14      .1       0
Bank Sta=179.79,222.14
XS Rating Curve= 0 ,0
Exp/Cntr(USF)=0,0
Exp/Cntr=0.3,0.1

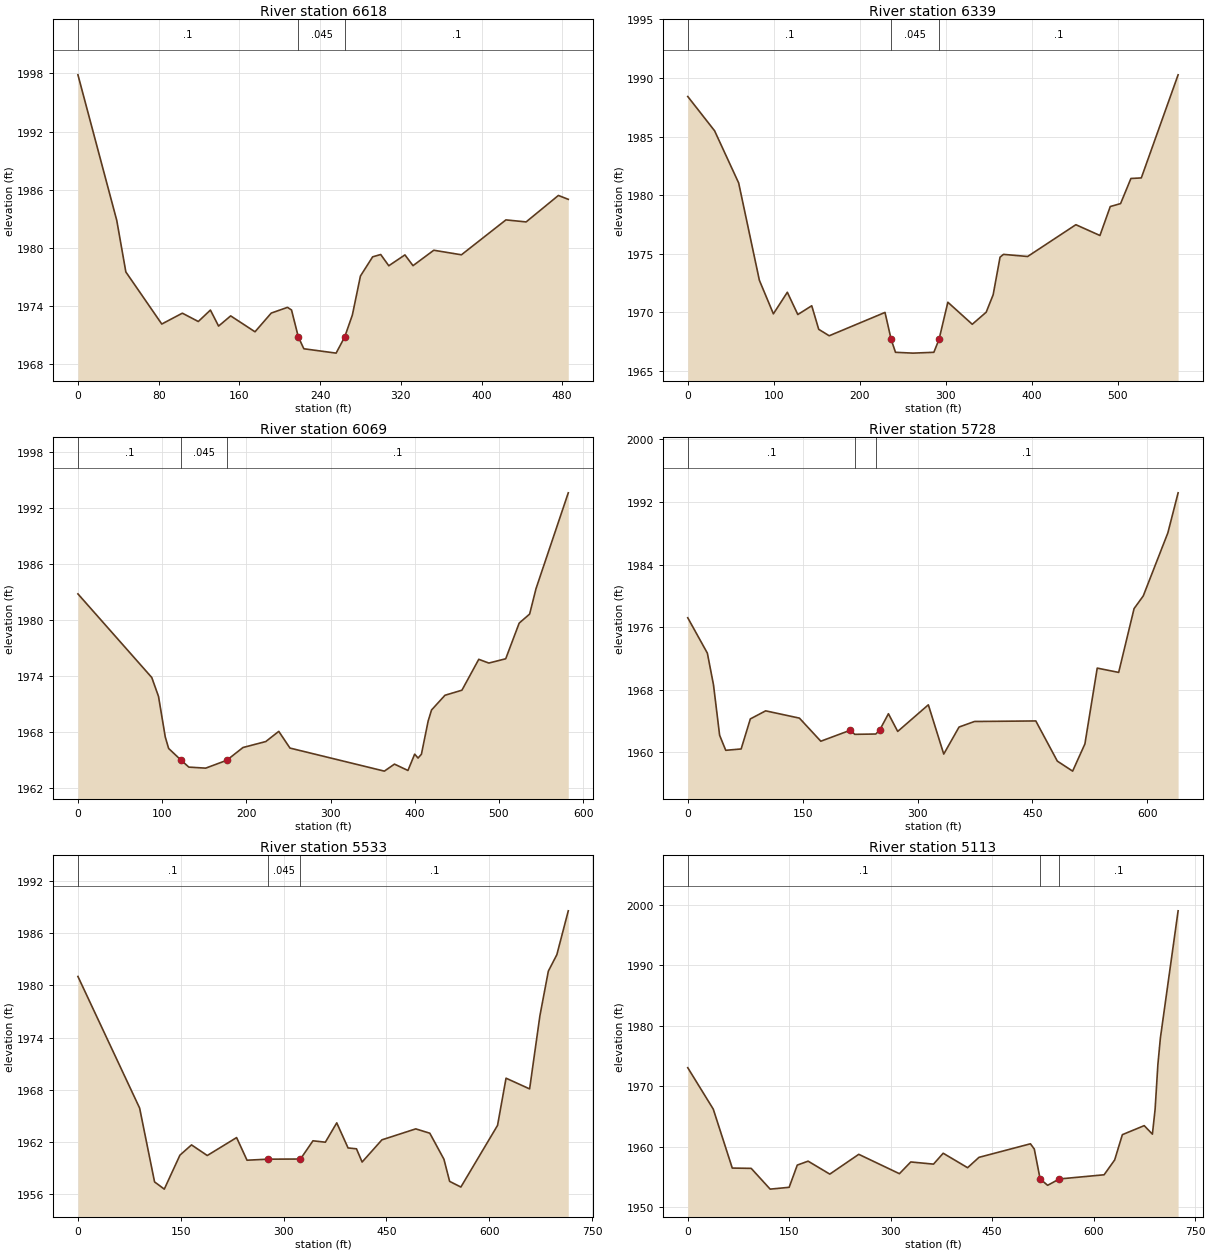
Type RM Length L Ch R = 1 ,6618    ,278.7,278.7,278.7
XS GIS Cut Line= 4
2192593.23368753635812.1676773732192579.36886572635860.710714059
2192602.14051985636096.7051765382192610.28935881636294.916007675
#Sta/Elev= 30
       0 1997.86    38.5 1982.84    47.5 1977.53    83.1 1972.16   103.5 1973.28
   119.3 1972.42   131.3  1973.6   139.4 1971.95   151.4    1973   175.5 1971.36
   191.6 1973.29   207.7 1973.88   211.7 1973.61  218.46 1970.82   223.9 1969.61
   255.9 1969.16  264.361970.819     272 1973.09     280 1977.11   292.1 1979.09
   300.1 1979.33   308.1 1978.17   324.1 1979.29   332.1 1978.18   352.7 1979.77
   380.1  1979.3   424.2  1982.9   444.2 1982.69   476.2 1985.42     486 1985.02
#Mann= 3 ,-1,0
       0      .1       0  218.46    .045       0  264.36      .1       0
Bank Sta=218.46,264.36
XS Rating Curve= 0 ,0
Exp/Cntr=0.3,0.1

Type RM Length L Ch R = 1 ,6339    ,270.3,270.3,270.3
XS GIS Cut Line= 4
2192348.62204827635761.9882784152192352.05699933 635840.13341512
2192305.68515997636111.4945491742192317.70748869636327.896466204
#Sta/Elev= 30
       0 1988.41    31.2 1985.49    59.2 1981.04    83.3 1972.74    99.6 1969.88
   115.8 1971.72     128 1969.82   144.2 1970.57   152.3 1968.56   164.5 1968.01
   229.4    1970  236.561967.701   241.6  1966.6   261.9 1966.53   286.2  1966.6
  292.221967.694   302.5 1970.87   330.9 1968.99   347.1 1970.02   355.2 1971.51
   363.2 1974.71   367.2 1974.95   395.3 1974.77   451.4 1977.48   479.4 1976.56
   491.4 1979.03   503.4 1979.28   515.4 1981.42   527.5 1981.47   570.3 1990.26
#Mann= 3 ,-1,0
       0      .1       0  236.56    .045       0  292.22      .1       0
Bank Sta=236.56,292.22
XS Rating Curve= 0 ,0
Exp/Cntr(USF)=0,0
Exp/Cntr=0.3,0.1

Type RM Length L Ch R = 1 ,6069    ,341,341,341
XS GIS Cut Line= 2
2192087.70192978635753.5354138412192066.12719574636335.407931932
#Sta/Elev= 30
       0 1982.81    87.7 1973.85    95.7 1971.82   103.7 1967.49   107.7 1966.25
  122.851964.964   131.7 1964.25   151.7 1964.14   176.7 1964.98     196 1966.35
   223.1 1966.99   238.5 1968.08   251.8 1966.29   363.9 1963.82   375.9 1964.57
   391.9 1963.89   399.9 1965.64   403.9 1965.22   407.9 1965.63   415.9 1969.19
   419.9 1970.37   435.9 1971.95     456 1972.49     476  1975.8     488  1975.4
     508 1975.86     524 1979.68   536.4 1980.65     544 1983.38   582.3 1993.64
#Mann= 3 ,-1,0
       0      .1       0  122.85    .045       0   176.7      .1       0
Bank Sta=122.85,176.7
XS Rating Curve= 0 ,0
Exp/Cntr=0.3,0.1

Type RM Length L Ch R = 1 ,5728    ,195.2,195.2,195.2
XS GIS Cut Line= 2
 2191749.2230876635739.6610964992191789.58376261636378.561994398
#Sta/Elev= 30
       0 1977.21    25.6 1972.69    33.6 1968.64    41.6  1962.2    49.6 1960.28
    69.7 1960.45    81.7 1964.29   101.7 1965.32   145.8 1964.39   173.7 1961.44
   212.4 1962.85     218 1962.32   245.5 1962.36  250.61 1962.87     262 1964.95
   274.1 1962.69   314.1 1966.09   334.2  1959.8   354.2 1963.25   374.3 1963.96
   454.4 1964.03   482.5  1958.9   502.5 1957.62   518.5 1961.09   534.6 1970.78
   562.6 1970.23   582.7 1978.38   594.7    1980   626.8 1988.05   640.2 1993.17
#Mann= 3 ,-1,0
       0      .1       0     218    .045       0   245.5      .1       0
Bank Sta=212.4,250.61
XS Rating Curve= 0 ,0
Exp/Cntr(USF)=0,0
Exp/Cntr=0.3,0.1

Type RM Length L Ch R = 1 ,5533    ,419.6,419.6,419.6
XS GIS Cut Line= 4
2191422.63915351635726.2334086592191445.86417727635813.779529089
2191606.32794766636020.8004639722191692.08183861636373.458785245
#Sta/Elev= 30
       0 1981.03      90 1965.92   111.8 1957.44     126 1956.61   148.8 1960.51
   165.7 1961.69   188.7 1960.47   231.5 1962.53   246.7 1959.93   277.2 1960.05
   324.71960.067   342.9 1962.16     361    1962   377.6 1964.22   394.1 1961.34
   406.4 1961.24   414.6 1959.72   443.5 1962.27   492.9 1963.53   513.4 1963.03
     534 1960.04   542.3  1957.5   558.7 1956.85   612.2 1963.93   624.6 1969.35
     659 1968.12     674 1976.52   686.3 1981.64   698.7 1983.53   715.4 1988.57
#Mann= 3 ,-1,0
       0      .1       0   277.2    .045       0   324.7      .1       0
Bank Sta=277.2,324.7
XS Rating Curve= 0 ,0
Exp/Cntr=0.3,0.1

Type RM Length L Ch R = 1 ,5113    ,358.1,358.1,358.1
XS GIS Cut Line= 5
2191251.15978405635783.5372585092191236.55664131636035.925625767
2191310.24475726636266.3989022692191411.49858085636371.176986172
2191400.50413616 636454.84699316
#Sta/Elev= 30
       0 1973.09    37.7 1966.25    65.8 1956.51    93.8 1956.46   121.8 1953.03
   149.9 1953.33   161.9    1957   177.9 1957.65     210 1955.51   252.8 1958.78
   312.9 1955.58   329.7 1957.52   363.3 1957.16   377.6 1958.96   413.7 1956.57
   430.5 1958.28   506.6 1960.52   512.3 1959.65   520.9 1954.72     532 1953.66
   549.4 1954.71   615.5  1955.4   631.1 1957.85   642.5 1962.03   674.8 1963.52
   686.9 1962.11   690.9 1966.23     695 1973.62   698.7    1978   724.9 1999.01
#Mann= 3 ,-1,0
       0      .1       0   520.9    .045       0   549.4      .1       0
Bank Sta=520.9,549.4
XS Rating Curve= 0 ,0
Exp/Cntr=0.3,0.1

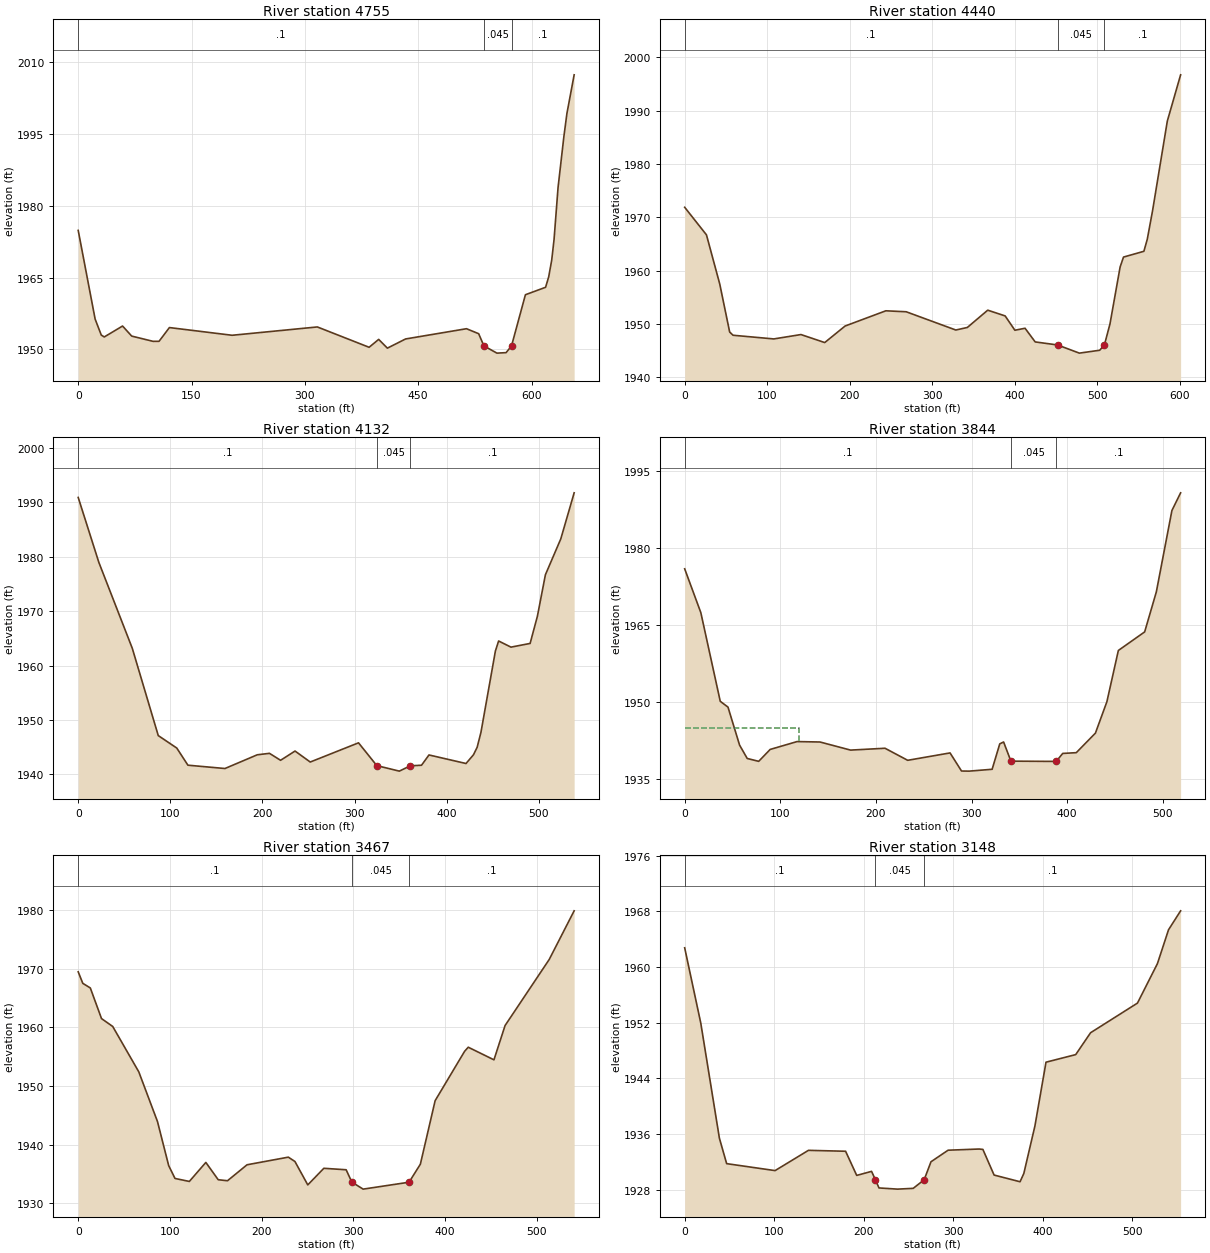
Type RM Length L Ch R = 1 ,4755    ,314.7,314.7,314.7
XS GIS Cut Line= 2
2191080.10303597635782.9295400162191001.95789927636434.711504404
#Sta/Elev= 30
       0 1974.84    22.4 1956.31    30.5 1952.98    34.5 1952.58    58.7 1954.86
    70.8 1952.76    99.1 1951.66     107 1951.67   120.7 1954.54   203.7 1952.93
   316.5 1954.67     385 1950.42   397.7 1952.07   409.2 1950.24   433.3 1952.16
   513.9  1954.3     530 1953.26     537 1950.71   554.2  1949.2   566.3  1949.3
  573.491950.697   591.9  1961.4   618.6 1962.96   622.7 1965.13   626.7 1968.63
   629.8 1972.93   635.1 1983.81   642.8 1994.43   646.8 1999.25   656.4 2007.35
#Mann= 3 ,-1,0
       0      .1       0     537    .045       0  573.49      .1       0
Bank Sta=537,573.49
XS Rating Curve= 0 ,0
Exp/Cntr(USF)=0,0
Exp/Cntr=0.3,0.1

Type RM Length L Ch R = 1 ,4440    ,308,308,308
XS GIS Cut Line= 4
2190810.02487712635806.788702658 2190806.8957016635860.030099515
2190688.74300638636352.0429058532190695.03840679636393.174006084
#Sta/Elev= 30
       0 1971.89    26.4 1966.72    42.5 1957.51    54.5 1948.52    58.6 1947.91
     108 1947.22   140.9 1948.04   169.7 1946.54   194.4 1949.64   243.7 1952.49
   268.4 1952.31   328.5 1948.89   342.5 1949.37   367.2 1952.61   388.3 1951.53
   400.1 1948.85   412.4 1949.22   424.7 1946.66   451.8 1946.09   478.2 1944.56
   502.9  1945.1   508.61946.123   515.3 1950.02   527.6  1960.7   531.7 1962.56
   556.4 1963.64   560.5 1965.89   566.9 1971.24   584.8 1988.05   600.9 1996.71
#Mann= 3 ,-1,0
       0      .1       0   451.8    .045       0   508.6      .1       0
Bank Sta=451.8,508.6
XS Rating Curve= 0 ,0
Exp/Cntr=0.3,0.1

Type RM Length L Ch R = 1 ,4132    ,287.9,287.9,287.9
XS GIS Cut Line= 3
2190459.49413298635826.8888117072190407.47769256636279.401238303
2190384.87095852636359.172998926
#Sta/Elev= 30
       0 1990.88    22.4 1978.95    58.7 1963.17    86.9 1947.13     107 1944.84
   119.1 1941.69   159.3 1941.08   194.4  1943.6   207.6 1943.87   219.7 1942.59
   235.4 1944.29   251.9 1942.27   304.3  1945.8  324.171941.612   348.6  1940.6
   360.6 1941.58   372.7 1941.68   380.8 1943.57     421    1942   429.1  1943.6
   433.1 1944.98   437.2 1947.71   452.9 1962.66   456.4 1964.51   469.8 1963.38
   490.6 1964.06   498.5 1969.06   507.2 1976.68   523.9 1983.27   538.4 1991.73
#Mann= 3 ,-1,0
       0      .1       0  324.17    .045       0   360.6      .1       0
Bank Sta=324.17,360.6
XS Rating Curve= 0 ,0
Exp/Cntr=0.3,0.1

Type RM Length L Ch R = 1 ,3844    ,377.4,377.4,377.4
XS GIS Cut Line= 3
2190138.79771966635796.4835048322190129.35160423635855.736410685
2190136.22150636636314.302377725
#Sta/Elev= 30
       0 1975.97    16.9 1967.42    37.2 1950.14    45.3    1949    57.4  1941.6
    65.4 1938.99    77.4 1938.43    89.4 1940.75   117.5 1942.28   141.5  1942.2
   173.5 1940.62   209.5 1940.98   233.2 1938.63   277.5 1940.07   289.5 1936.54
   297.5 1936.52   321.5 1936.88   329.5 1941.84   333.5  1942.2  341.161938.466
  388.491938.412   395.3 1939.97   409.5 1940.12   429.5 1943.93   441.5 1950.05
   453.5 1960.05     481 1963.67   493.2 1971.46   509.5 1987.34   518.6 1990.79
#Mann= 3 ,-1,0
       0      .1       0  341.16    .045       0  388.49      .1       0
#XS Ineff= 2 , 0
        119.8122    1945
Permanent Ineff=
       F       F
Bank Sta=341.16,388.49
XS Rating Curve= 0 ,0
Exp/Cntr(USF)=0,0
Exp/Cntr=0.3,0.1

Type RM Length L Ch R = 1 ,3467    ,319.3,319.3,319.3
XS GIS Cut Line= 4
2189915.42590851635768.2415143652189897.49240741635865.182526111
2189772.11669358636109.0640516532189759.53230372636276.324077666
#Sta/Elev= 30
       0 1969.47       5 1967.51    13.2 1966.72    25.4  1961.5    37.6 1960.16
      66 1952.43    86.4 1943.95    98.6 1936.44   105.5 1934.25   121.1 1933.74
   139.1 1936.98   152.6 1934.03   162.7 1933.86     184 1936.58     229 1937.88
   236.2 1937.14   250.2 1933.15   267.7 1935.98     292 1935.73   298.2 1933.63
   310.5 1932.43  360.591933.608   372.9 1936.68     389 1947.51   421.1 1955.92
   425.1 1956.62   453.1 1954.47   465.2 1960.31   513.3 1971.57   540.5 1979.87
#Mann= 3 ,-1,0
       0      .1       0   298.2    .045       0  360.59      .1       0
Bank Sta=298.2,360.59
XS Rating Curve= 0 ,0
Exp/Cntr=0.3,0.1

Type RM Length L Ch R = 1 ,3148    ,314.4,314.4,314.4
XS GIS Cut Line= 2
2189560.45863395635723.7957592482189413.98374939636258.217155205
#Sta/Elev= 30
       0 1962.75      18 1951.93    38.8  1935.4    46.9 1931.75     101 1930.75
   138.3 1933.66   179.8 1933.53   192.2 1930.06   208.8 1930.64     213 1929.47
     213 1929.46   217.1 1928.26   237.8 1928.09   255.3  1928.2  267.561929.432
   275.2 1932.02   294.3 1933.68   329.1 1933.85   333.2 1933.79   345.7 1930.11
   374.7 1929.15   378.9 1930.33   391.3 1937.15   403.7 1946.32   436.9 1947.41
   453.5 1950.55   505.9 1954.81   528.2 1960.48   540.6 1965.34   554.1 1968.06
#Mann= 3 ,-1,0
       0      .1       0     213    .045       0  267.56      .1       0
Bank Sta=213,267.56
XS Rating Curve= 0 ,0
Exp/Cntr=0.3,0.1

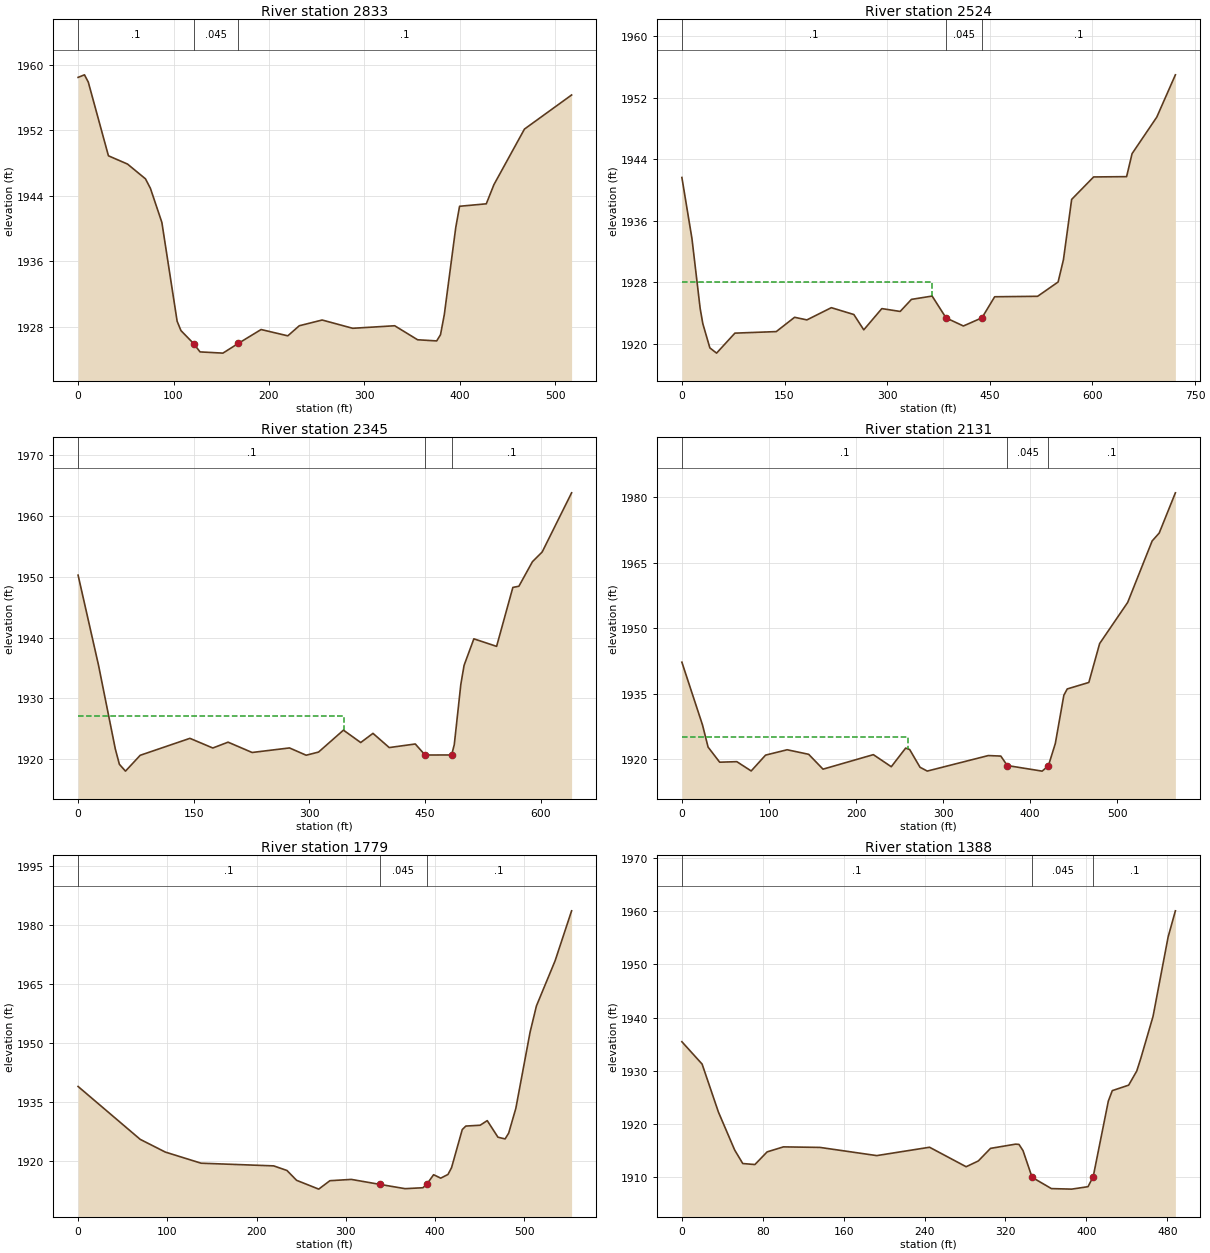
Type RM Length L Ch R = 1 ,2833    ,309.8,309.8,309.8
XS GIS Cut Line= 2
2189193.29950827635725.3723628562189194.25366134636242.523328598
#Sta/Elev= 30
       0 1958.46     6.7 1958.77    10.7 1957.88    31.8 1948.89    51.8 1947.88
    70.6 1946.08    75.8 1944.92    87.8 1940.76   103.8  1928.7   107.8 1927.56
   121.2 1925.96   127.8 1924.96   151.8 1924.81   167.8 1925.99   191.8 1927.69
   219.8 1926.92   231.8 1928.15   255.8 1928.85   287.8 1927.84   331.8 1928.15
   355.8 1926.44   375.8  1926.3   379.8 1927.05   383.8 1929.51   395.8 1940.14
   399.8 1942.73   427.8 1943.03   435.8 1945.37   467.8 1952.15   517.2 1956.31
#Mann= 3 ,-1,0
       0      .1       0   121.2    .045       0   167.8      .1       0
Bank Sta=121.2,167.8
XS Rating Curve= 0 ,0
Exp/Cntr(USF)=0,0
Exp/Cntr=0.3,0.1

Type RM Length L Ch R = 1 ,2524    ,178.5,178.5,178.5
XS GIS Cut Line= 4
2188666.17151165635734.5543665472188663.62173196635775.337778556
2189074.88218077636080.7499398742189088.34743872636248.290268611
#Sta/Elev= 30
       0  1941.6    14.7 1933.67    26.7 1924.58    30.6 1922.59    40.9 1919.44
    50.7 1918.76    77.5 1921.36   137.9 1921.56   164.7 1923.42   182.7 1923.08
   218.4 1924.67   251.3 1923.78   265.8 1921.79   292.2 1924.55     319 1924.18
   335.5 1925.75   365.7 1926.18   386.1 1923.34   411.4 1922.29   438.5 1923.35
   457.1 1926.09   519.9 1926.15   549.8 1928.01   557.6 1930.91   569.6 1938.75
   601.7 1941.67   649.9 1941.71   657.9  1944.7     694 1949.45   721.2 1954.95
#Mann= 3 ,0,0
       0      .1       0   386.1    .045       0   438.5      .1       0
#XS Ineff= 2 , 0
           365.4    1928
Permanent Ineff=
       F       F
Bank Sta=386.1,438.5
XS Rating Curve= 0 ,0
Exp/Cntr=0.3,0.1

Type RM Length L Ch R = 1 ,2345    ,213.5,213.5,213.5
XS GIS Cut Line= 4
 2188582.9665279635730.9727495912188589.38186501635772.672440768
2188792.53420664635998.278462268 2188886.6258175636277.345626302
#Sta/Elev= 30
       0 1950.27    26.5 1935.44    48.3 1921.64    53.6 1919.11    61.5 1917.99
    80.6  1920.6   145.1 1923.39   174.8  1921.8   194.6 1922.76   225.8 1921.06
   274.3 1921.81   295.9 1920.61     312 1921.13   344.3 1924.74   366.7  1922.7
   382.6 1924.21   403.7 1921.87   437.5 1922.46   450.2 1920.64  484.661920.656
   488.1 1922.36   496.6 1932.29   500.8 1935.41   513.5 1939.78     543 1938.54
   564.1 1948.25   571.9 1948.44   589.5 1952.49   602.1 1954.08   640.3 1963.83
#Mann= 3 ,-1,0
       0      .1       0   450.2    .045       0  484.66      .1       0
#XS Ineff= 2 , 0
        344.7624    1927
Permanent Ineff=
       F       F
Bank Sta=450.2,484.66
XS Rating Curve= 0 ,0
Exp/Cntr(USF)=0,0
Exp/Cntr=0.3,0.1

Type RM Length L Ch R = 1 ,2131    ,352.8,352.8,352.8
XS GIS Cut Line= 3
2188524.62959355635759.9782964992188642.48199691 636227.11939571
2188633.83025921636311.741358947
#Sta/Elev= 30
       0 1942.23    23.7 1927.82    30.1 1922.75    43.4 1919.29    63.1 1919.41
    79.6 1917.28    96.1 1920.91   120.9 1922.14   145.6  1921.1   162.1 1917.69
   219.9 1921.02   240.5 1918.25     257 1922.52   261.6  1922.2   273.5 1918.13
   281.8 1917.25   351.9 1920.81   366.3 1920.69  373.731918.522   413.8 1917.24
  420.961918.478   428.9 1923.58   438.7 1934.65   442.6 1936.09   467.4 1937.58
   479.8  1946.5     512 1955.93   540.1 1970.03   548.2 1971.84   566.8 1981.07
#Mann= 3 ,-1,0
       0      .1       0  373.73    .045       0  420.96      .1       0
#XS Ineff= 2 , 0
        260.1701    1925
Permanent Ineff=
       F       F
Bank Sta=373.73,420.96
XS Rating Curve= 0 ,0
Exp/Cntr(USF)=0,0
Exp/Cntr=0.3,0.1

Type RM Length L Ch R = 1 ,1779    ,391.2,391.2,391.2
XS GIS Cut Line= 3
2188293.48985427 635795.726936882188265.92543216636212.373778897
2188264.66526523636347.705648563
#Sta/Elev= 30
       0 1938.87    69.6 1925.43    97.7  1922.2   137.8 1919.37   219.1 1918.69
     234 1917.52   244.8 1915.02   269.6 1912.78   282.1 1914.92   306.1 1915.25
   338.2 1913.98   366.3  1912.9   386.3 1913.13  390.581913.998   398.3 1916.44
   406.3 1915.57   414.4 1916.51   418.4 1918.23   430.4 1927.92   434.4 1928.81
   450.4 1929.02   458.4 1930.19   470.4 1925.98   478.4 1925.54   482.4 1927.01
   490.4 1933.29   506.4 1952.69   513.5 1959.35   534.4 1970.81   552.9 1983.52
#Mann= 3 ,-1,0
       0      .1       0   338.2    .045       0  390.58      .1       0
Bank Sta=338.2,390.58
XS Rating Curve= 0 ,0
Exp/Cntr(USF)=0,0
Exp/Cntr=0.3,0.1

Type RM Length L Ch R = 1 ,1388    ,342.4,342.4,342.4
XS GIS Cut Line= 2
2187857.79545161635849.2329165072187901.89493472 636335.28591522
#Sta/Elev= 30
       0 1935.47      20 1931.27    36.1 1922.27    52.2 1915.12    60.2 1912.58
    72.2 1912.39    84.3 1914.77   100.4 1915.71   136.5 1915.61   192.7 1914.07
   244.9 1915.64   281.1 1911.98   293.1 1913.06   305.2 1915.43   329.9 1916.22
   333.3 1916.18   337.3 1915.02   346.3 1909.99   365.4 1907.87   385.5 1907.77
   401.6 1908.23  406.751910.124   421.7 1924.32   425.6 1926.28   441.8 1927.31
   449.8 1929.97   453.8 1932.35   465.9 1940.23   480.8 1955.15     488 1960.07
#Mann= 3 ,-1,0
       0      .1       0   346.3    .045       0  406.75      .1       0
Bank Sta=346.3,406.75
XS Rating Curve= 0 ,0
Exp/Cntr(USF)=0,0
Exp/Cntr=0.3,0.1