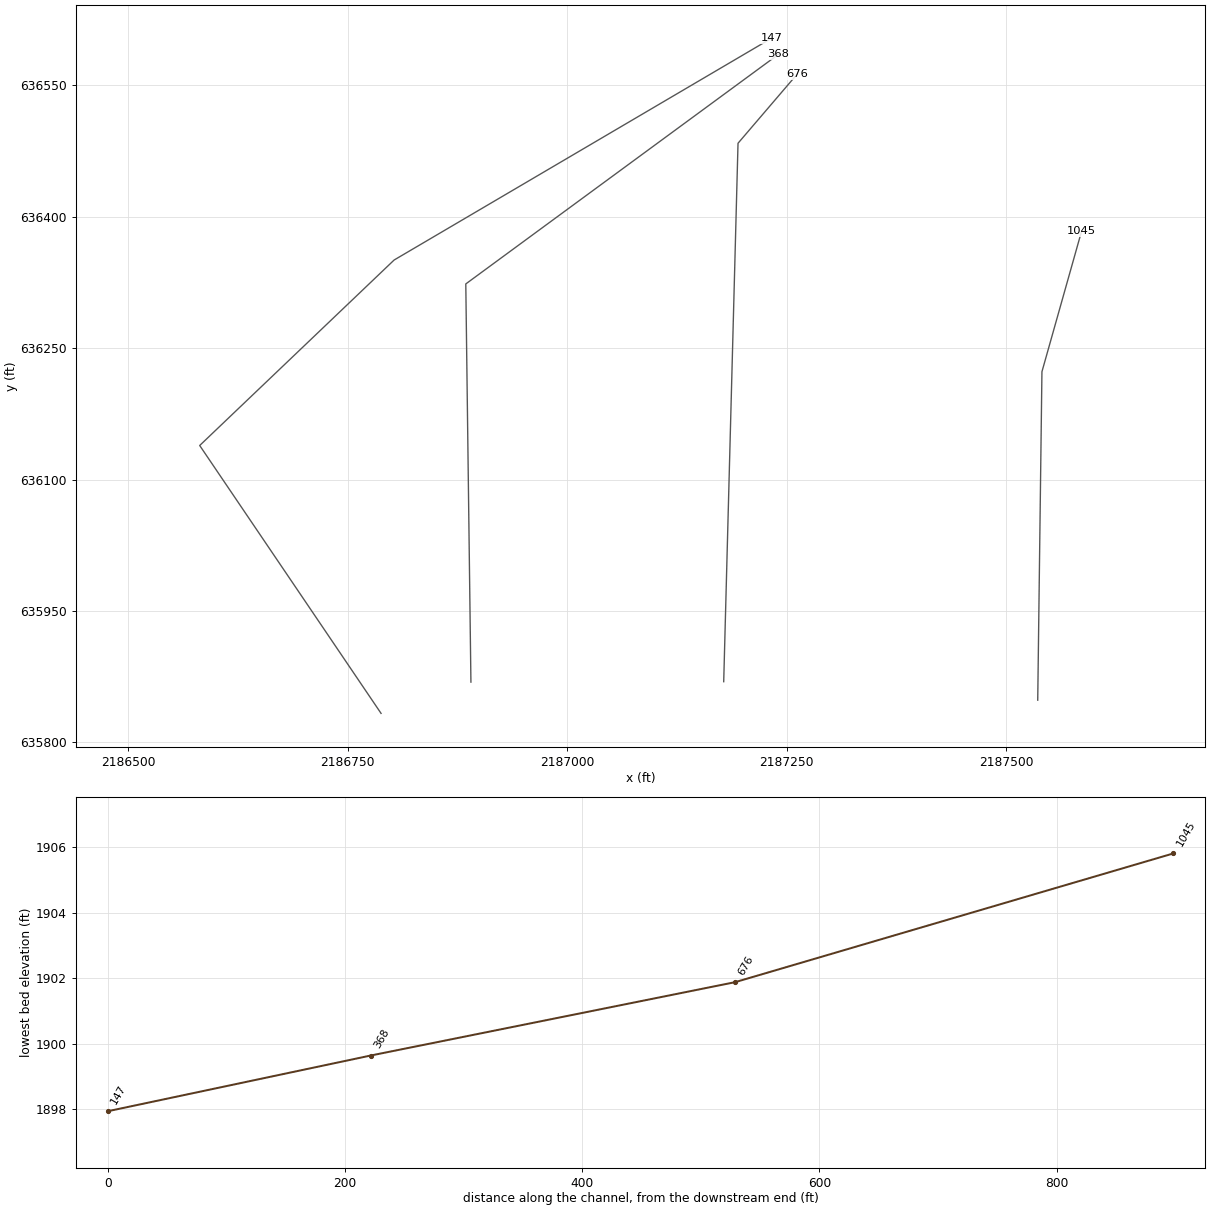
HEC-RAS study LFRFBUCRV.prj: LFRFBUCRV

--- LFRFBUCRV.g01 (geometry) --- (continued)

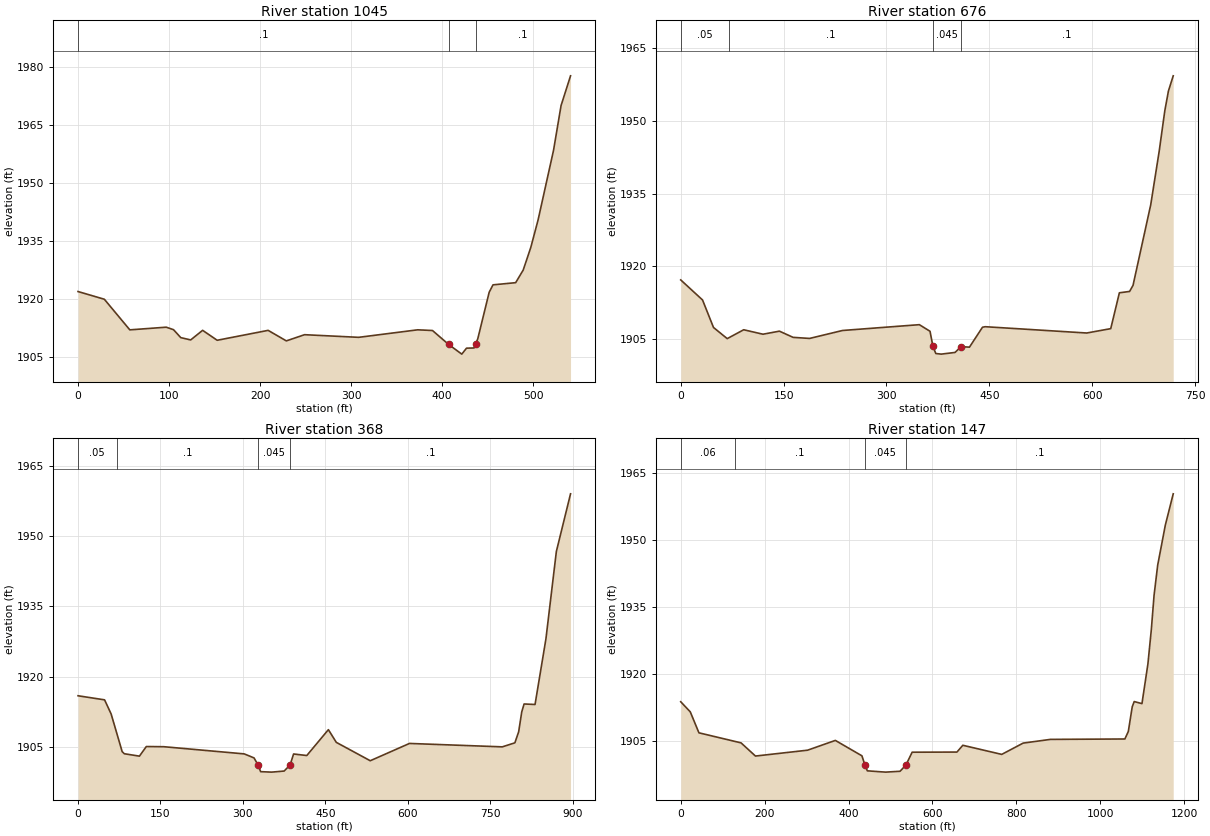
Type RM Length L Ch R = 1 ,1045    ,369.5,369.5,369.5
XS GIS Cut Line= 3
2187535.67748796635848.2742320912187540.47091004636223.119838594
2187585.52907757636383.220136001
#Sta/Elev= 30
       0 1921.98    28.9 1919.99    56.9 1912.08    96.9 1912.77   104.9 1912.13
   112.9 1910.07   123.8 1909.48   136.9 1911.96   152.9 1909.39   208.9 1911.95
   228.9 1909.23   248.9 1910.83   308.4 1910.15   373.2 1912.09   389.5 1911.91
   407.2 1908.32   421.7 1905.81   426.9 1907.35   435.2  1907.4  436.931908.379
   439.3 1909.81   451.8  1921.8     456 1923.71   480.9 1924.27   489.2 1927.54
   497.5 1933.36   505.5 1940.44   522.5 1958.45   530.8 1970.04   541.2 1977.71
#Mann= 3 ,-1,0
       0      .1       0   407.2    .045       0  436.93      .1       0
Bank Sta=407.2,436.93
XS Rating Curve= 0 ,0
Exp/Cntr(USF)=0,0
Exp/Cntr=0.3,0.1

Type RM Length L Ch R = 1 ,676     ,307.3,307.3,307.3
XS GIS Cut Line= 3
2187178.08820094635869.3652892352187194.38583601636483.881999639
 2187261.4937451636562.494121719
#Sta/Elev= 30
       0  1917.2    31.8 1913.06    47.8 1907.38    67.8 1905.08    91.8 1906.91
   119.9 1905.99   143.9 1906.62   163.9 1905.34   187.9 1905.12   235.9 1906.76
   347.9 1907.96   363.5  1906.6  367.711903.511   371.9 1902.01   379.9 1901.88
     400 1902.23   408.7 1903.43     421 1903.32     440 1907.43     444 1907.54
     592 1906.24     627 1907.14   639.6 1914.54   654.5 1914.82   659.5 1916.08
   685.3 1932.71   697.6 1943.72   705.8 1952.09   711.1 1956.19   718.1 1959.33
#Mann= 4 ,-1,0
       0     .05       0      70      .1       0  367.71    .045       0
   408.7      .1       0
Bank Sta=367.71,408.7
XS Rating Curve= 0 ,0
Exp/Cntr(USF)=0,0
Exp/Cntr=0.3,0.1

Type RM Length L Ch R = 1 ,368     ,221.6,221.6,221.6
XS GIS Cut Line= 3
2186890.23032011635868.8914156532186884.38557439636323.320394854
2187240.20624136636585.189989093
#Sta/Elev= 30
       0 1915.93    48.3 1915.06    60.3 1912.03    80.3 1904.01    84.3 1903.56
   111.7 1903.05   124.3  1905.1   156.3 1905.06   302.5 1903.53   320.3 1902.67
  328.041901.081   332.3 1899.74   352.3 1899.64   375.1 1899.87  385.861901.159
   392.3 1903.51   416.3 1903.18   455.6  1908.7     470 1905.99   531.8 1902.07
   603.2 1905.76   772.1 1905.03     795 1905.89   801.9 1908.25   807.5 1912.49
   811.8 1914.18   831.7 1914.07   851.5 1928.06   870.5 1946.72   896.3 1959.01
#Mann= 4 ,-1,0
       0     .05       0      70      .1       0  328.04    .045       0
  385.86      .1       0
Bank Sta=328.04,385.86
XS Rating Curve= 0 ,0
Exp/Cntr(USF)=0,0
Exp/Cntr=0.3,0.1

Type RM Length L Ch R = 1 ,147     ,,,
XS GIS Cut Line= 4
 2186787.8954835635833.2075636292186581.37359606636138.923037322
2186802.78095498636350.6182415182187232.32833772636603.615638346
#Sta/Elev= 30
       0  1913.7    22.8 1911.43    43.4 1906.74   143.8 1904.49   178.1 1901.54
   302.3 1902.85   368.5 1905.04   431.9 1901.59  439.17 1899.51   444.8 1898.23
     488 1897.94   522.7 1898.13   536.6 1899.51   551.6  1902.4   658.3 1902.43
   672.4 1903.95   765.1 1901.91   816.1 1904.44   881.1 1905.27  1058.6 1905.36
  1066.8 1907.05  1076.1 1912.56  1080.8 1913.74  1099.3 1913.28  1113.5 1922.18
  1121.7 1929.94  1128.1 1937.49  1136.8 1944.29    1155 1953.25  1173.8 1960.25
#Mann= 4 ,-1,0
       0     .06       0     130      .1       0  439.17    .045       0
   536.6      .1       0
Bank Sta=439.17,536.6
XS Rating Curve= 0 ,0
Exp/Cntr(USF)=0,0
Exp/Cntr=0.3,0.1
LCMann Table=0

Chan Stop Cuts=-1
Use User Specified Reach Order=0
Composite Channel Slope=5