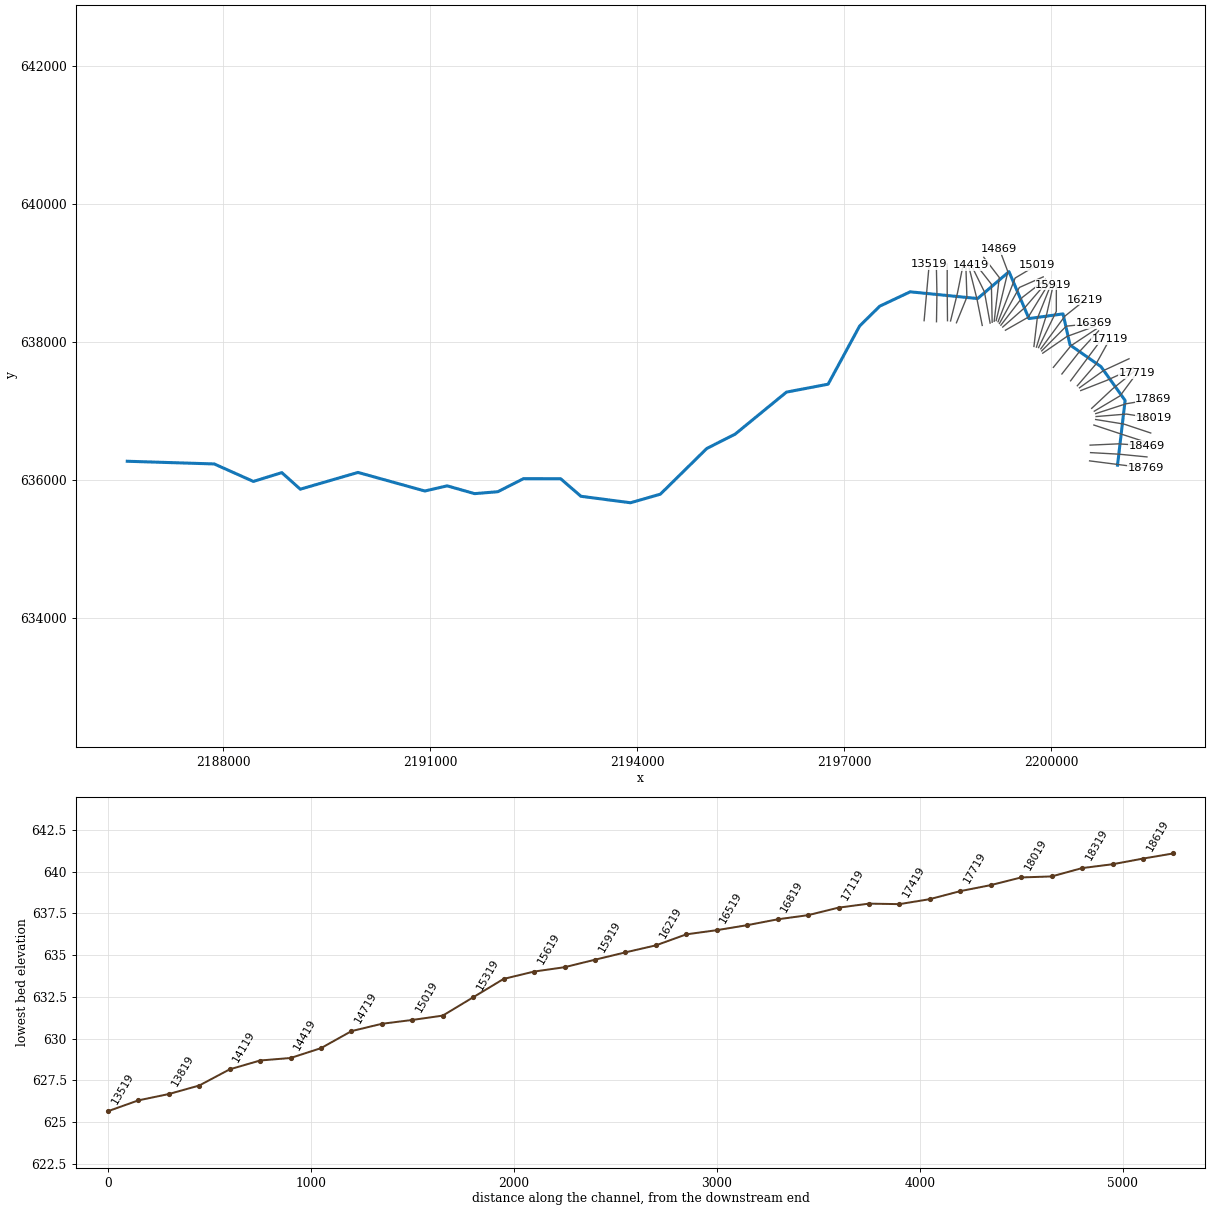
--- LFRFBUCKRV.prj (project) ---

Proj Title=LFRFBUCKRV
Current Plan=p01
Geom File=g01
Flow File=f01
Plan File=p01
DSS Export Rating Curves=0
DSS Export Rating Curve Sorted=0
DSS Export Volume Flow Curves=0
DXF OffsetX=0
DXF OffsetY=0
DXF ScaleX=0
DXF ScaleY=0

--- LFRFBUCKRV.p01 (plan) ---

Plan Title=Floodplain
Program Version=4.00
Geom File=g01
Flow File=f01
K Sum by GR=0
Std Step Tol=0.01
Critical Tol=0.01
Num of Std Step Trials=20
Max Error Tol=0.3
Flow Tol Ratio=0.001
Split Flow NTrial=30
Split Flow Tol=0.02
Split Flow Ratio=0.02
Log Output Level=0
Friction Slope Method=1
Unsteady Friction Slope Method=2
Unsteady Bridges Friction Slope Method=1
Global Log Level=0
CheckData=False
Run HTab=0
Run UNet=0
Run PostProcess=0
UNET Theta=0
UNET Theta Warmup=0
UNET ZTol=0
UNET ZSATol=0
UNET MxIter=0
UNET MaxInSteps=0
UNET DtIC=0
UNET DtMin=0
UNET MaxCRTS=0
UNET WFStab=0
UNET SFStab=0
UNET WFX=0
UNET SFX=0
UNET DSS MLevel=0
UNET DZMax Abort=0
UNET Convert EG Bridges=0
UNET Use Existing IB Tables=0
UNET Froude Limit=0
UNET Froude Power=0
Write IC File=0
Echo Input=False
Echo Output=False
Write Detailed=0

--- LFRFBUCKRV.f01 (steady flow) ---

Flow Title=Flows
Program Version=4.00
Number of Profiles= 1
Profile Names=01pct
River Rch & RM=LFRFBUCKRV,Main      ,18769
2752.851
River Rch & RM=LFRFBUCKRV,Main      ,18469
2755.462
River Rch & RM=LFRFBUCKRV,Main      ,18169
2758.916
River Rch & RM=LFRFBUCKRV,Main      ,17869
2762.136
River Rch & RM=LFRFBUCKRV,Main      ,17569
2766.985
River Rch & RM=LFRFBUCKRV,Main      ,17269
2769.952
River Rch & RM=LFRFBUCKRV,Main      ,16969
2772.818
River Rch & RM=LFRFBUCKRV,Main      ,16669
2774.402
River Rch & RM=LFRFBUCKRV,Main      ,16369
2788.928
River Rch & RM=LFRFBUCKRV,Main      ,16069
2789.989
River Rch & RM=LFRFBUCKRV,Main      ,15769
2809.836
River Rch & RM=LFRFBUCKRV,Main      ,15469
2812.552
River Rch & RM=LFRFBUCKRV,Main      ,15169
2813.326
River Rch & RM=LFRFBUCKRV,Main      ,14869
2816.298
River Rch & RM=LFRFBUCKRV,Main      ,13969
2827.112
River Rch & RM=LFRFBUCKRV,Main      ,13669
2829.483
River Rch & RM=LFRFBUCKRV,Main      ,13369
2833.817
River Rch & RM=LFRFBUCKRV,Main      ,13069
2836.126
River Rch & RM=LFRFBUCKRV,Main      ,12769
2837.356
River Rch & RM=LFRFBUCKRV,Main      ,12469
2838.486
River Rch & RM=LFRFBUCKRV,Main      ,12169
2843.772
River Rch & RM=LFRFBUCKRV,Main      ,11869
2846.000
River Rch & RM=LFRFBUCKRV,Main      ,11569
2849.335
River Rch & RM=LFRFBUCKRV,Main      ,11269
2851.157
River Rch & RM=LFRFBUCKRV,Main      ,10969
2853.130
River Rch & RM=LFRFBUCKRV,Main      ,10669
2860.287
River Rch & RM=LFRFBUCKRV,Main      ,10369
2864.109
River Rch & RM=LFRFBUCKRV,Main      ,10069
2865.994
River Rch & RM=LFRFBUCKRV,Main      ,9769
2871.193
River Rch & RM=LFRFBUCKRV,Main      ,9469
2874.225
River Rch & RM=LFRFBUCKRV,Main      ,9169
2876.669
River Rch & RM=LFRFBUCKRV,Main      ,8869
2879.938
River Rch & RM=LFRFBUCKRV,Main      ,8569
2882.446
River Rch & RM=LFRFBUCKRV,Main      ,7969
2945.475
River Rch & RM=LFRFBUCKRV,Main      ,7669
2947.835
River Rch & RM=LFRFBUCKRV,Main      ,7369
2948.574
River Rch & RM=LFRFBUCKRV,Main      ,7069
2949.741
River Rch & RM=LFRFBUCKRV,Main      ,6769
2960.028
River Rch & RM=LFRFBUCKRV,Main      ,6469
2964.867
River Rch & RM=LFRFBUCKRV,Main      ,6169
2966.670
River Rch & RM=LFRFBUCKRV,Main      ,5869
2967.589
River Rch & RM=LFRFBUCKRV,Main      ,5569
2988.706
River Rch & RM=LFRFBUCKRV,Main      ,5269
2990.661
River Rch & RM=LFRFBUCKRV,Main      ,4969
2992.427
River Rch & RM=LFRFBUCKRV,Main      ,4669
2994.067
River Rch & RM=LFRFBUCKRV,Main      ,4369
2996.129
River Rch & RM=LFRFBUCKRV,Main      ,4069
2997.588
River Rch & RM=LFRFBUCKRV,Main      ,3769
3011.295
River Rch & RM=LFRFBUCKRV,Main      ,3469
3012.842
River Rch & RM=LFRFBUCKRV,Main      ,3169
3014.325
River Rch & RM=LFRFBUCKRV,Main      ,2869
3024.128
River Rch & RM=LFRFBUCKRV,Main      ,2569
3024.471
River Rch & RM=LFRFBUCKRV,Main      ,2269
3030.537
River Rch & RM=LFRFBUCKRV,Main      ,1969
3033.069
River Rch & RM=LFRFBUCKRV,Main      ,1669
3036.737
River Rch & RM=LFRFBUCKRV,Main      ,1369
3039.340
River Rch & RM=LFRFBUCKRV,Main      ,1069
3041.056
Boundary for River Rch & Prof#=LFRFBUCKRV,Main      ,1
Up Type=0
Dn Type=3
Dn Slope=0.002556

--- LFRFBUCKRV.g01 (geometry) ---

Geom Title=Geometry
Program Version=4.00

River Reach=LFRFBUCKRV     ,Main
Reach XY= 30
     2200959.272      636219.074     2201068.816      637156.289
     2200718.522      637647.060     2200270.733      637960.267
     2200169.631      638410.603     2199675.484      638342.581
     2199386.601      639022.221     2198932.287      638632.694
     2197955.181      638730.162     2197514.345      638522.292
     2197222.744      638235.127     2196765.912      637391.945
     2196162.679      637277.107     2195419.483      636668.494
     2195008.265      636460.539     2194335.551      635798.384
     2193903.100      635674.017     2193184.342      635767.908
     2192890.681      636022.250     2192353.437      636023.395
     2191980.108      635833.897     2191643.235      635806.225
     2191246.784      635919.002     2190923.133      635844.314
     2189954.926      636113.422     2189118.526      635870.440
     2188851.507      636110.360     2188438.572      635982.903
     2187872.368      636236.272     2186611.788      636275.276

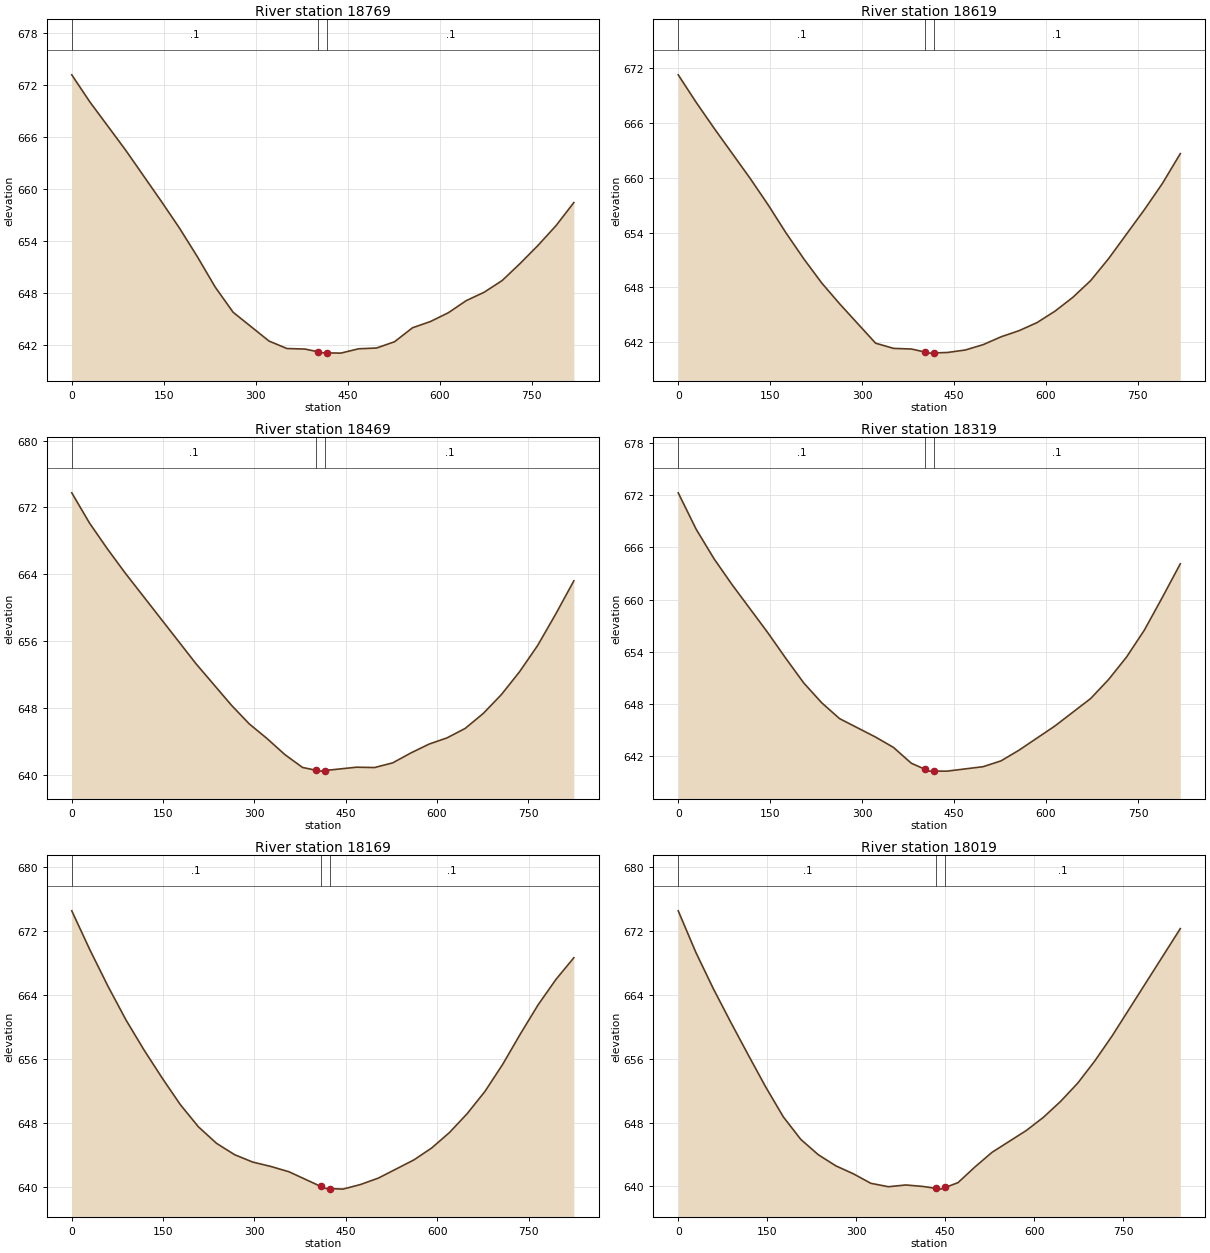
Type RM Length L Ch R = 1 ,18769,148.3,150,150.7
XS GIS Cut Line= 3
     2200554.346      636280.921     2200960.540      636228.993
     2201366.734      636177.065
#Sta/Elev= 28
       0  673.17    29.2  670.08    87.8  664.50   146.2  658.58   175.5  655.53
   204.8  652.22   234.0  648.71   263.2  645.81   321.8  642.49   351.0  641.63
   380.2  641.57     402  641.25   409.5  641.14     417  641.13   438.8  641.10
   468.0  641.60   497.2  641.69   526.5  642.41   555.8  644.02   585.0  644.74
   614.2  645.75   643.5  647.15   672.8  648.12   702.0  649.46   731.2  651.42
   760.5  653.51   789.8  655.78   819.0  658.45
#Mann= 3 , 0 , 0
       0     0.1       0     402   0.045       0     417     0.1       0
Bank Sta=402,417
Exp/Cntr=0.3,0.1

Type RM Length L Ch R = 1 ,18619,147.7,150,150.5
XS GIS Cut Line= 3
     2200568.721      636400.373     2200978.061      636377.951
     2201385.540      636338.130
#Sta/Elev= 28
       0  671.30    29.3  668.28    58.6  665.44   117.1  659.97   146.4  657.08
   175.7  653.99   205.0  651.12   234.3  648.47   263.5  646.19   322.1  641.88
   351.4  641.31   380.7  641.24   402.5  640.91   410.0  640.79   417.5  640.81
   439.2  640.86   468.4  641.13   497.7  641.72   526.9  642.58   556.2  643.25
   585.4  644.13   614.7  645.38   643.9  646.90   673.2  648.75   702.4  651.15
   760.9  656.53   790.1  659.38   819.4  662.66
#Mann= 3 , 0 , 0
       0     0.1       0   402.5   0.045       0   417.5     0.1       0
Bank Sta=402.5,417.5
Exp/Cntr=0.3,0.1

Type RM Length L Ch R = 1 ,18469,158.3,150,144.3
XS GIS Cut Line= 3
     2200561.753      636508.888     2200969.591      636527.400
     2201385.310      636501.261
#Sta/Elev= 26
       0  673.75    29.2  670.13    58.3  667.07    87.5  664.18   204.1  653.30
   262.4  648.33   291.6  646.10   320.8  644.35   349.9  642.44   379.1  640.89
   400.8  640.56   408.3  640.45   415.8  640.52   467.8  640.92   497.5  640.88
   527.3  641.44   557.0  642.62   586.8  643.68   616.5  644.43   646.3  645.56
   676.0  647.35   705.8  649.61   735.5  652.33   765.3  655.48   795.0  659.24
   824.8  663.22
#Mann= 3 , 0 , 0
       0     0.1       0   400.8   0.045       0   415.8     0.1       0
Bank Sta=400.8,415.8
Exp/Cntr=0.3,0.1

Type RM Length L Ch R = 1 ,18319,146.1,150,149.9
XS GIS Cut Line= 3
     2200616.731      636800.109     2201005.503      636671.478
     2201394.845      636544.563
#Sta/Elev= 26
       0  672.30    29.2  668.11    58.5  664.69    87.8  661.72   146.2  656.17
   175.5  653.22   204.8  650.38   234.0  648.10   263.2  646.27   321.8  644.15
   351.0  642.96   380.2  641.13     402  640.45   409.5  640.22     417  640.22
   438.8  640.22   497.2  640.73   526.5  641.40   555.8  642.63   614.2  645.41
   672.8  648.59   702.0  650.78   731.2  653.36   760.5  656.49   789.8  660.26
   819.0  664.12
#Mann= 3 , 0 , 0
       0     0.1       0     402   0.045       0     417     0.1       0
Bank Sta=402,417
Exp/Cntr=0.3,0.1

Type RM Length L Ch R = 1 ,18169,144.7,150,153.7
XS GIS Cut Line= 3
     2200642.086      636880.211     2201052.757      636813.840
     2201440.181      636684.787
#Sta/Elev= 29
       0  674.48    29.7  669.62    59.4  665.07    89.1  660.84   118.9  657.07
   148.6  653.58   178.3  650.27   208.0  647.50   237.7  645.44   267.4  644.02
   297.1  643.10   326.9  642.55   356.6  641.89   408.5  640.07   416.0  639.82
   423.5  639.79   445.2  639.72   474.3  640.30   503.5  641.10   561.8  643.37
   591.0  644.86   620.2  646.79   649.3  649.15   678.5  651.93   707.7  655.32
   736.8  659.13   766.0  662.77   795.2  665.93   824.4  668.62
#Mann= 3 , 0 , 0
       0     0.1       0   408.5   0.045       0   423.5     0.1       0
Bank Sta=408.5,423.5
Exp/Cntr=0.3,0.1

Type RM Length L Ch R = 1 ,18019,144.8,150,157.1
XS GIS Cut Line= 3
     2200648.472      636923.066     2201089.752      636958.879
     2201488.630      636897.086
#Sta/Elev= 28
       0  674.52    29.5  669.35    59.0  664.79    88.6  660.56   118.1  656.46
   147.6  652.44   177.1  648.72   206.6  645.89   236.1  643.97   265.6  642.58
   295.2  641.58   324.7  640.39   354.2  639.96   383.7  640.18   413.2  639.99
   435.2  639.74   442.7  639.66   450.2  639.87   471.6  640.47   500.4  642.45
   529.2  644.28   586.9  647.01   615.7  648.66   644.6  650.65   673.4  652.93
   702.2  655.71   731.0  658.80   846.4  672.29
#Mann= 3 , 0 , 0
       0     0.1       0   435.2   0.045       0   450.2     0.1       0
Bank Sta=435.2,450.2
Exp/Cntr=0.3,0.1

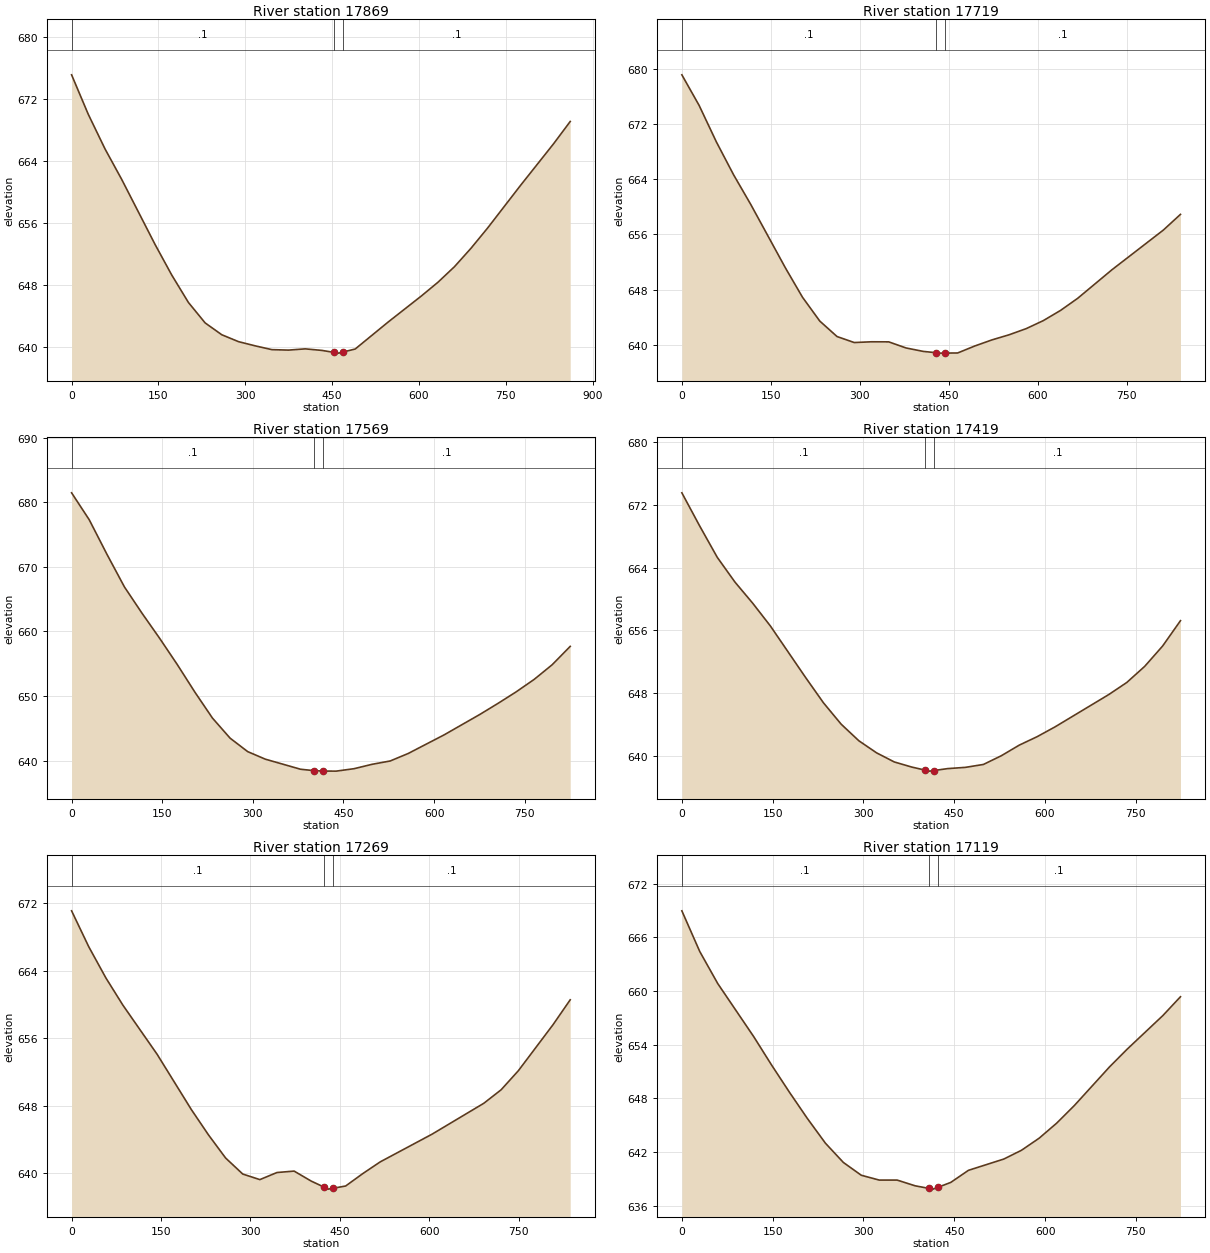
Type RM Length L Ch R = 1 ,17869,145.4,150,167.5
XS GIS Cut Line= 3
     2200643.275      636965.421     2201082.085      637107.948
     2201476.840      637173.122
#Sta/Elev= 28
       0  675.10    28.8  670.01    57.7  665.55    86.5  661.62   144.2  653.22
   173.0  649.28   201.8  645.74   230.7  643.10   259.5  641.57   288.4  640.68
   317.2  640.14   346.0  639.65   374.9  639.59   403.7  639.75   432.5  639.55
   453.9  639.29   461.4  639.20   468.9  639.34   490.0  639.73   547.1  643.22
   604.3  646.57   632.8  648.33   661.4  650.34   690.0  652.72   718.6  655.32
   775.7  660.84   832.9  666.22   861.5  669.08
#Mann= 3 , 0 , 0
       0     0.1       0   453.9   0.045       0   468.9     0.1       0
Bank Sta=453.9,468.9
Exp/Cntr=0.3,0.1

Type RM Length L Ch R = 1 ,17719,144.7,150,144.3
XS GIS Cut Line= 3
     2200622.504      637000.652     2200997.176      637223.944
     2201237.477      637549.709
#Sta/Elev= 28
       0  679.09    29.1  674.67    58.2  669.39    87.2  664.64   116.3  660.33
   174.5  651.19   203.5  646.92   232.6  643.48   261.7  641.24   290.8  640.37
   319.8  640.48   348.9  640.47   378.0  639.59   407.1  639.09   428.7  638.90
   436.2  638.84   443.7  638.85   465.1  638.86   494.0  639.87   522.9  640.75
   551.8  641.49   580.7  642.38   609.6  643.54   638.6  645.01   667.5  646.76
   725.3  650.89   812.0  656.63   841.0  658.91
#Mann= 3 , 0 , 0
       0     0.1       0   428.7   0.045       0   443.7     0.1       0
Bank Sta=428.7,443.7
Exp/Cntr=0.3,0.1

Type RM Length L Ch R = 1 ,17569,158.6,150,144.4
XS GIS Cut Line= 3
     2200584.829      637042.061     2200883.017      637320.767
     2201207.064      637583.386
#Sta/Elev= 27
       0  681.46    29.2  677.29    58.3  671.98    87.5  666.88   116.6  662.81
   145.8  658.92   174.9  654.87   204.1  650.59   233.2  646.57   262.4  643.46
   291.5  641.38   320.7  640.21   379.0  638.65   400.7  638.44   415.7  638.37
   438.0  638.36   467.7  638.74   497.5  639.42   527.3  639.93   557.1  641.09
   616.7  643.98   676.3  647.17   706.1  648.87   735.9  650.64   765.7  652.57
   795.5  654.84   825.3  657.68
#Mann= 3 , 0 , 0
       0     0.1       0   400.7   0.045       0   415.7     0.1       0
Bank Sta=400.7,415.7
Exp/Cntr=0.3,0.1

Type RM Length L Ch R = 1 ,17419,144.3,150,150
XS GIS Cut Line= 3
     2200425.929      637299.373     2200807.121      637448.680
     2201183.943      637621.231
#Sta/Elev= 28
       0  673.52    29.2  669.33    58.5  665.30    87.7  662.15   117.0  659.46
   146.2  656.56   204.7  649.96   233.9  646.77   263.2  644.04   292.4  641.93
   321.7  640.39   350.9  639.23   380.2  638.57   401.9  638.19   409.4  638.06
   416.9  638.14   439.0  638.38   468.6  638.54   498.2  638.91   527.8  640.02
   557.4  641.37   587.0  642.45   616.6  643.70   705.4  647.82   735.0  649.35
   764.6  651.40   794.2  653.99   823.8  657.23
#Mann= 3 , 0 , 0
       0     0.1       0   401.9   0.045       0   416.9     0.1       0
Bank Sta=401.9,416.9
Exp/Cntr=0.3,0.1

Type RM Length L Ch R = 1 ,17269,144.5,150,164.4
XS GIS Cut Line= 3
     2200407.322      637339.281     2200757.586      637589.880
     2201125.826      637760.299
#Sta/Elev= 25
       0  671.12    28.7  666.87    57.4  663.17    86.1  659.92   143.6  654.08
   201.0  647.52   229.7  644.52   258.4  641.78   287.1  639.88   315.8  639.22
   344.5  640.06   373.3  640.23   402.0  639.04   423.2  638.34   430.7  638.09
   438.2  638.19   459.7  638.46   488.6  639.94   517.6  641.32   604.6  644.61
   691.5  648.28   720.5  649.88   749.5  652.15   807.5  657.60   836.4  660.56
#Mann= 3 , 0 , 0
       0     0.1       0   423.2   0.045       0   438.2     0.1       0
Bank Sta=423.2,438.2
Exp/Cntr=0.3,0.1

Type RM Length L Ch R = 1 ,17119,148.4,150,147
XS GIS Cut Line= 3
     2200376.561      637368.873     2200646.990      637683.680
     2200845.241      638041.026
#Sta/Elev= 27
       0  668.95    29.6  664.40    59.3  660.82   118.6  654.90   148.2  651.72
   177.9  648.66   207.5  645.73   237.2  642.98   266.8  640.83   296.4  639.40
   326.1  638.86   355.7  638.86   385.4  638.22   407.5  637.94   415.0  637.85
   422.5  638.04   444.2  638.60   473.4  639.95   531.8  641.21   561.0  642.19
   590.2  643.54   619.3  645.23   648.5  647.20   706.9  651.54   736.1  653.52
   794.5  657.24   823.7  659.35
#Mann= 3 , 0 , 0
       0     0.1       0   407.5   0.045       0   422.5     0.1       0
Bank Sta=407.5,422.5
Exp/Cntr=0.3,0.1

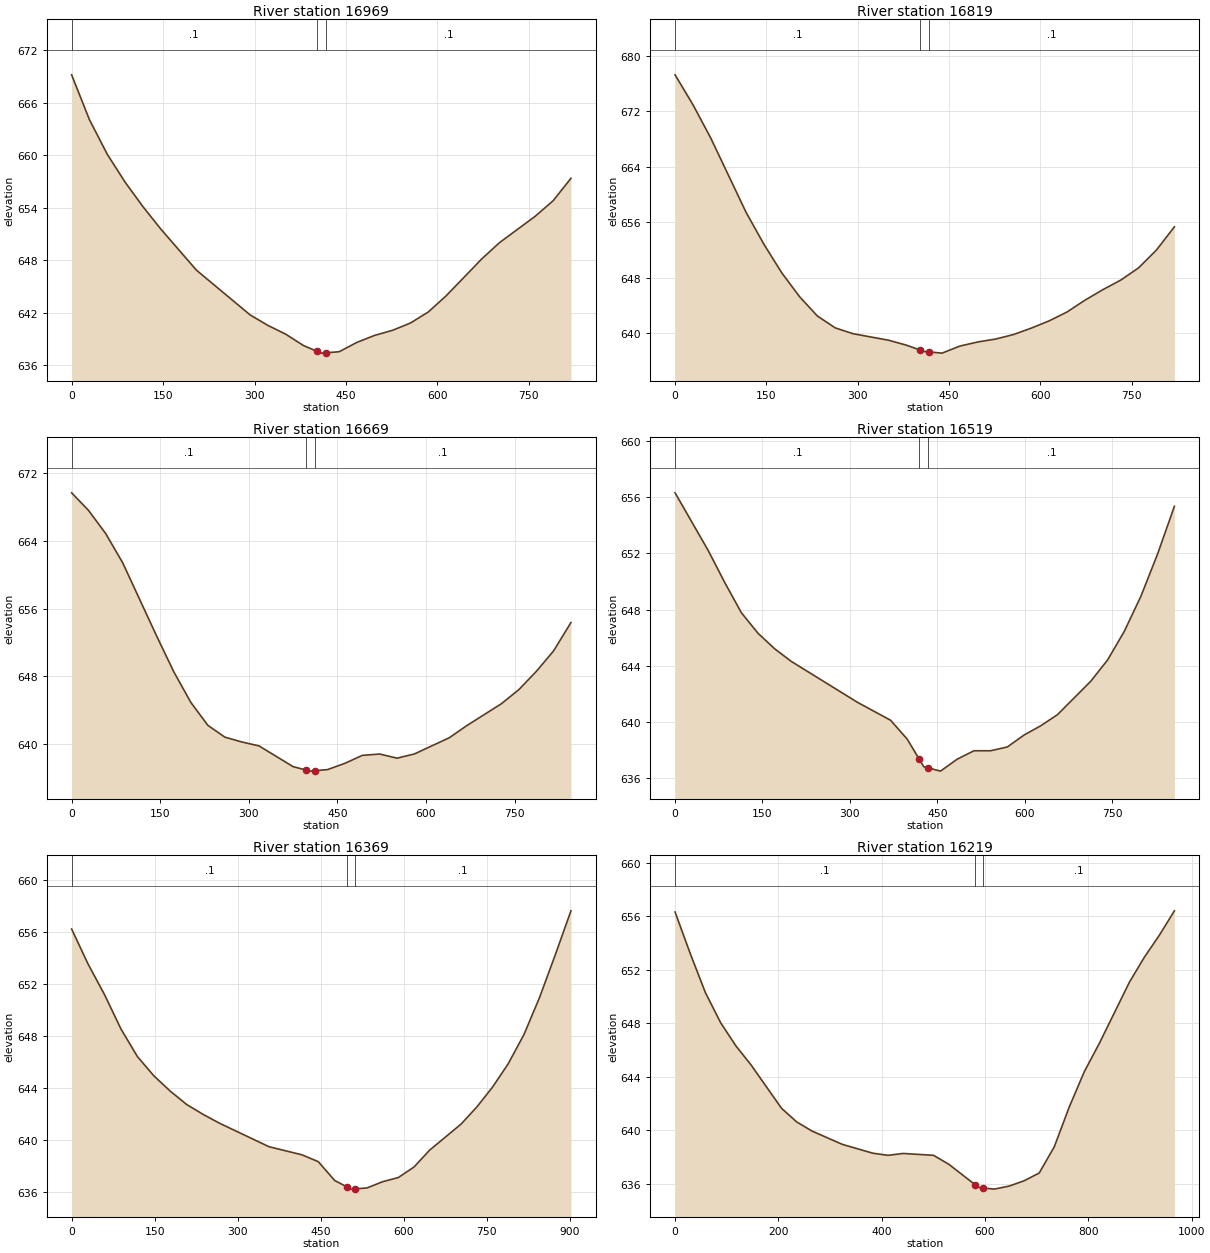
Type RM Length L Ch R = 1 ,16969,150.5,150,147.6
XS GIS Cut Line= 3
     2200279.227      637440.726     2200524.010      637769.012
     2200768.792      638097.298
#Sta/Elev= 26
       0  669.19    29.2  664.07    58.5  660.11    87.8  656.92   117.0  654.13
   146.2  651.58   204.8  646.87   292.5  641.78   321.8  640.57   351.0  639.57
   380.2  638.27     402  637.62   409.5  637.40     417  637.44   438.8  637.56
   468.0  638.63   497.2  639.43   526.5  640.01   555.8  640.84   585.0  642.10
   614.2  643.94   672.8  648.17   702.0  650.03   760.5  653.04   789.8  654.81
   819.0  657.37
#Mann= 3 , 0 , 0
       0     0.1       0     402   0.045       0     417     0.1       0
Bank Sta=402,417
Exp/Cntr=0.3,0.1

Type RM Length L Ch R = 1 ,16819,150.4,150,144.4
XS GIS Cut Line= 3
     2200153.003      637539.842     2200405.948      637861.535
     2200684.637      638163.677
#Sta/Elev= 29
       0  677.27    29.2  672.99    58.5  668.18   116.9  657.40   146.2  652.81
   175.4  648.71   204.6  645.28   233.8  642.50   263.1  640.79   292.3  639.95
   350.8  639.01   380.0  638.30   401.7  637.62   409.2  637.39   416.7  637.33
   438.6  637.15   468.0  638.17   497.3  638.76   526.7  639.18   556.0  639.83
   585.4  640.76   614.8  641.81   644.1  643.09   673.5  644.79   702.8  646.30
   732.2  647.68   761.6  649.45   790.9  652.02   820.3  655.36
#Mann= 3 , 0 , 0
       0     0.1       0   401.7   0.045       0   416.7     0.1       0
Bank Sta=401.7,416.7
Exp/Cntr=0.3,0.1

Type RM Length L Ch R = 1 ,16669,156.4,150,144.8
XS GIS Cut Line= 3
     2200029.664      637635.807     2200284.457      637949.106
     2200652.736      638192.880
#Sta/Elev= 28
       0  669.67    28.8  667.58    57.7  664.86    86.5  661.40   144.2  652.72
   173.1  648.52   201.9  644.91   230.8  642.20   259.6  640.81   288.4  640.24
   317.3  639.78   375.0  637.33   396.3  636.94   403.8  636.80   411.3  636.85
   433.3  636.98   462.7  637.72   492.2  638.66   521.6  638.82   551.0  638.33
   580.5  638.83   639.4  640.74   668.8  642.16   727.7  644.76   757.2  646.42
   786.6  648.56   816.0  650.99   845.5  654.35
#Mann= 3 , 0 , 0
       0     0.1       0   396.3   0.045       0   411.3     0.1       0
Bank Sta=396.3,411.3
Exp/Cntr=0.3,0.1

Type RM Length L Ch R = 1 ,16519,140.4,150,144.4
XS GIS Cut Line= 3
     2199875.585      637841.366     2200226.896      638083.669
     2200631.202      638230.286
#Sta/Elev= 27
       0  656.32    56.9  652.21    85.4  649.92   113.8  647.78   142.3  646.32
   170.7  645.22   199.2  644.32   313.0  641.40   369.9  640.12   398.3  638.78
   419.3  637.33   426.8  636.81   434.3  636.73   455.4  636.50   484.1  637.35
   512.8  637.95   541.4  637.95   570.1  638.22   598.8  639.07   627.5  639.73
   656.1  640.52   713.5  642.91   742.2  644.42   770.8  646.45   799.5  648.97
   828.2  651.99   856.8  655.36
#Mann= 3 , 0 , 0
       0     0.1       0   419.3   0.045       0   434.3     0.1       0
Bank Sta=419.3,434.3
Exp/Cntr=0.3,0.1

Type RM Length L Ch R = 1 ,16369,151.9,150,162.9
XS GIS Cut Line= 3
     2199860.673      637874.243     2200216.632      638232.527
     2200611.532      638273.117
#Sta/Elev= 30
       0  656.24    29.7  653.55    59.4  651.20    89.1  648.56   118.8  646.44
   148.5  644.96   178.2  643.78   208.0  642.75   237.7  641.99   267.4  641.31
   356.5  639.51   415.9  638.89   445.6  638.36   475.3  636.91   497.5  636.42
   505.0  636.25   512.5  636.27   533.4  636.34   561.8  636.82   590.1  637.14
   618.5  637.95   646.8  639.25   703.5  641.25   731.9  642.56   760.2  644.08
   788.6  645.88   817.0  648.12   845.3  650.98   873.7  654.26   902.0  657.64
#Mann= 3 , 0 , 0
       0     0.1       0   497.5   0.045       0   512.5     0.1       0
Bank Sta=497.5,512.5
Exp/Cntr=0.3,0.1

Type RM Length L Ch R = 1 ,16219,146.7,150,170.3
XS GIS Cut Line= 3
     2199847.311      637903.875     2200196.559      638377.856
     2200491.589      638613.950
#Sta/Elev= 30
       0  656.33    29.4  653.22    58.9  650.28    88.3  648.04   117.8  646.31
   147.2  644.88   206.1  641.64   235.5  640.62   264.9  639.94   323.8  638.94
   382.7  638.28   412.1  638.12   441.6  638.26   500.4  638.12   529.9  637.45
   581.3  635.91   588.8  635.71   596.3  635.68   617.8  635.59   646.9  635.82
   676.0  636.22   705.0  636.80   734.1  638.76   763.2  641.75   792.2  644.38
   821.3  646.50   879.4  651.07   908.5  652.95   937.6  654.60   966.6  656.42
#Mann= 3 , 0 , 0
       0     0.1       0   581.3   0.045       0   596.3     0.1       0
Bank Sta=581.3,596.3
Exp/Cntr=0.3,0.1

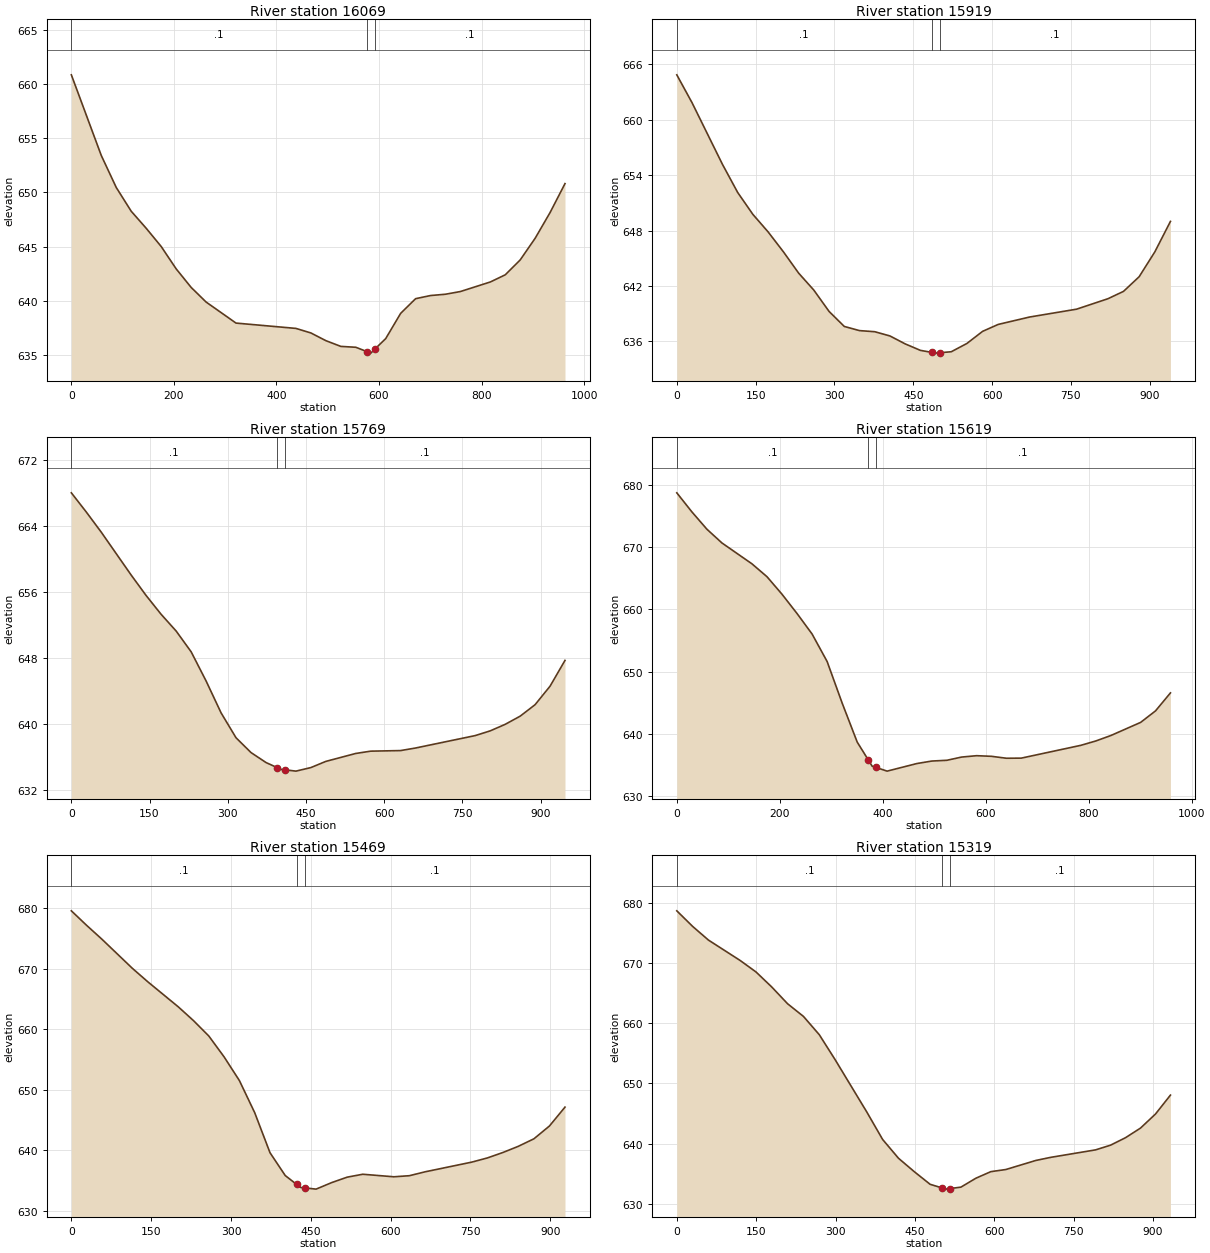
Type RM Length L Ch R = 1 ,16069,148.5,150,143.4
XS GIS Cut Line= 3
     2199815.191      637922.362     2200072.076      638446.716
     2200072.931      638825.441
#Sta/Elev= 30
       0  660.83    58.4  653.39    87.6  650.44   116.8  648.25   146.0  646.68
   175.2  645.00   204.4  642.94   233.6  641.23   262.8  639.88   321.1  637.94
   437.9  637.45   467.1  637.03   496.3  636.32   525.5  635.79   554.7  635.71
   576.4  635.31   583.9  635.17   591.4  635.52   613.0  636.51   642.2  638.84
   671.3  640.19   700.4  640.48   729.6  640.60   758.7  640.85   817.0  641.73
   846.1  642.39   875.2  643.76   904.4  645.76   933.5  648.13   962.6  650.80
#Mann= 3 , 0 , 0
       0     0.1       0   576.4   0.045       0   591.4     0.1       0
Bank Sta=576.4,591.4
Exp/Cntr=0.3,0.1

Type RM Length L Ch R = 1 ,15919,142.9,150,145.7
XS GIS Cut Line= 3
     2199784.451      637929.255     2199931.277      638399.344
     2200029.260      638835.327
#Sta/Elev= 30
       0  664.88    29.0  661.86    86.9  655.18   115.9  652.13   144.8  649.76
   173.8  647.86   202.8  645.71   231.8  643.40   260.7  641.56   289.7  639.25
   318.7  637.62   347.6  637.17   376.6  637.05   405.6  636.59   434.6  635.73
   463.5  635.03     485  634.81   492.5  634.73     500  634.77   522.3  634.88
   552.1  635.78   581.9  637.09   611.6  637.84   671.2  638.64   760.6  639.49
   820.2  640.62   850.0  641.42   879.8  643.01   909.6  645.70   939.3  649.00
#Mann= 3 , 0 , 0
       0     0.1       0     485   0.045       0     500     0.1       0
Bank Sta=485,500
Exp/Cntr=0.3,0.1

Type RM Length L Ch R = 1 ,15769,171.4,150,149.9
XS GIS Cut Line= 3
     2199748.078      637938.617     2199794.927      638337.966
     2199997.823      638843.440
#Sta/Elev= 30
       0  668.01    28.7  665.68    57.4  663.24   114.9  658.03   143.6  655.55
   172.3  653.28   201.0  651.26   229.8  648.74   258.5  645.20   287.2  641.34
   315.9  638.32   344.6  636.53   373.4  635.32   394.6  634.71   402.1  634.49
   409.6  634.44   430.8  634.28   459.4  634.71   488.1  635.46   545.4  636.42
   574.1  636.70   631.4  636.77   660.1  637.08   774.8  638.59   803.4  639.16
   832.1  639.95   860.8  640.94   889.4  642.33   918.1  644.57   946.8  647.70
#Mann= 3 , 0 , 0
       0     0.1       0   394.6   0.045       0   409.6     0.1       0
Bank Sta=394.6,409.6
Exp/Cntr=0.3,0.1

Type RM Length L Ch R = 1 ,15619,145.3,150,147
XS GIS Cut Line= 3
     2199334.817      638173.761     2199664.372      638362.032
     2199966.304      638856.377
#Sta/Elev= 30
       0  678.74    29.2  675.69    58.4  672.90    87.6  670.69   146.0  667.33
   175.2  665.26   204.4  662.44   233.6  659.34   262.8  656.05   292.0  651.63
   321.2  644.95   350.4  638.69     372  635.81   379.5  634.81     387  634.61
   408.5  634.02   466.4  635.24   495.4  635.64   524.4  635.76   553.3  636.28
   582.3  636.50   611.2  636.40   640.2  636.09   669.2  636.11   785.0  638.17
   814.0  638.87   843.0  639.74   900.9  641.85   929.8  643.70   958.8  646.59
#Mann= 3 , 0 , 0
       0     0.1       0     372   0.045       0     387     0.1       0
Bank Sta=372,387
Exp/Cntr=0.3,0.1

Type RM Length L Ch R = 1 ,15469,142.6,150,142.9
XS GIS Cut Line= 3
     2199296.072      638219.950     2199619.167      638504.756
     2199943.613      638881.153
#Sta/Elev= 30
       0  679.60    28.7  677.20    57.4  674.91   114.8  670.08   143.6  667.87
   201.0  663.72   229.7  661.43   258.4  658.89   287.1  655.44   315.8  651.53
   344.6  646.21   373.3  639.60   402.0  635.82   423.2  634.37   430.7  633.86
   438.2  633.79   459.9  633.58   489.2  634.66   518.4  635.56   547.6  636.04
   606.1  635.62   635.3  635.80   664.6  636.44   752.2  638.04   781.5  638.73
   810.7  639.63   839.9  640.66   869.2  641.90   898.4  644.02   927.6  647.14
#Mann= 3 , 0 , 0
       0     0.1       0   423.2   0.045       0   438.2     0.1       0
Bank Sta=423.2,438.2
Exp/Cntr=0.3,0.1

Type RM Length L Ch R = 1 ,15319,144.3,150,144.6
XS GIS Cut Line= 3
     2199269.104      638246.777     2199579.929      638649.526
     2199915.335      638909.298
#Sta/Elev= 30
       0  678.63    29.9  676.05    59.8  673.78   119.7  670.40   149.6  668.50
   179.6  665.99   209.5  663.21   239.4  661.12   269.3  658.09   299.3  653.94
   359.1  645.27   389.0  640.72   419.0  637.60   448.9  635.37   478.8  633.28
   501.2  632.68   508.7  632.48   516.2  632.57   537.0  632.81   565.3  634.29
   593.6  635.38   621.9  635.73   678.4  637.23   706.7  637.75   791.6  638.99
   819.8  639.77   848.1  641.01   876.4  642.60   904.7  644.93   933.0  648.07
#Mann= 3 , 0 , 0
       0     0.1       0   501.2   0.045       0   516.2     0.1       0
Bank Sta=501.2,516.2
Exp/Cntr=0.3,0.1

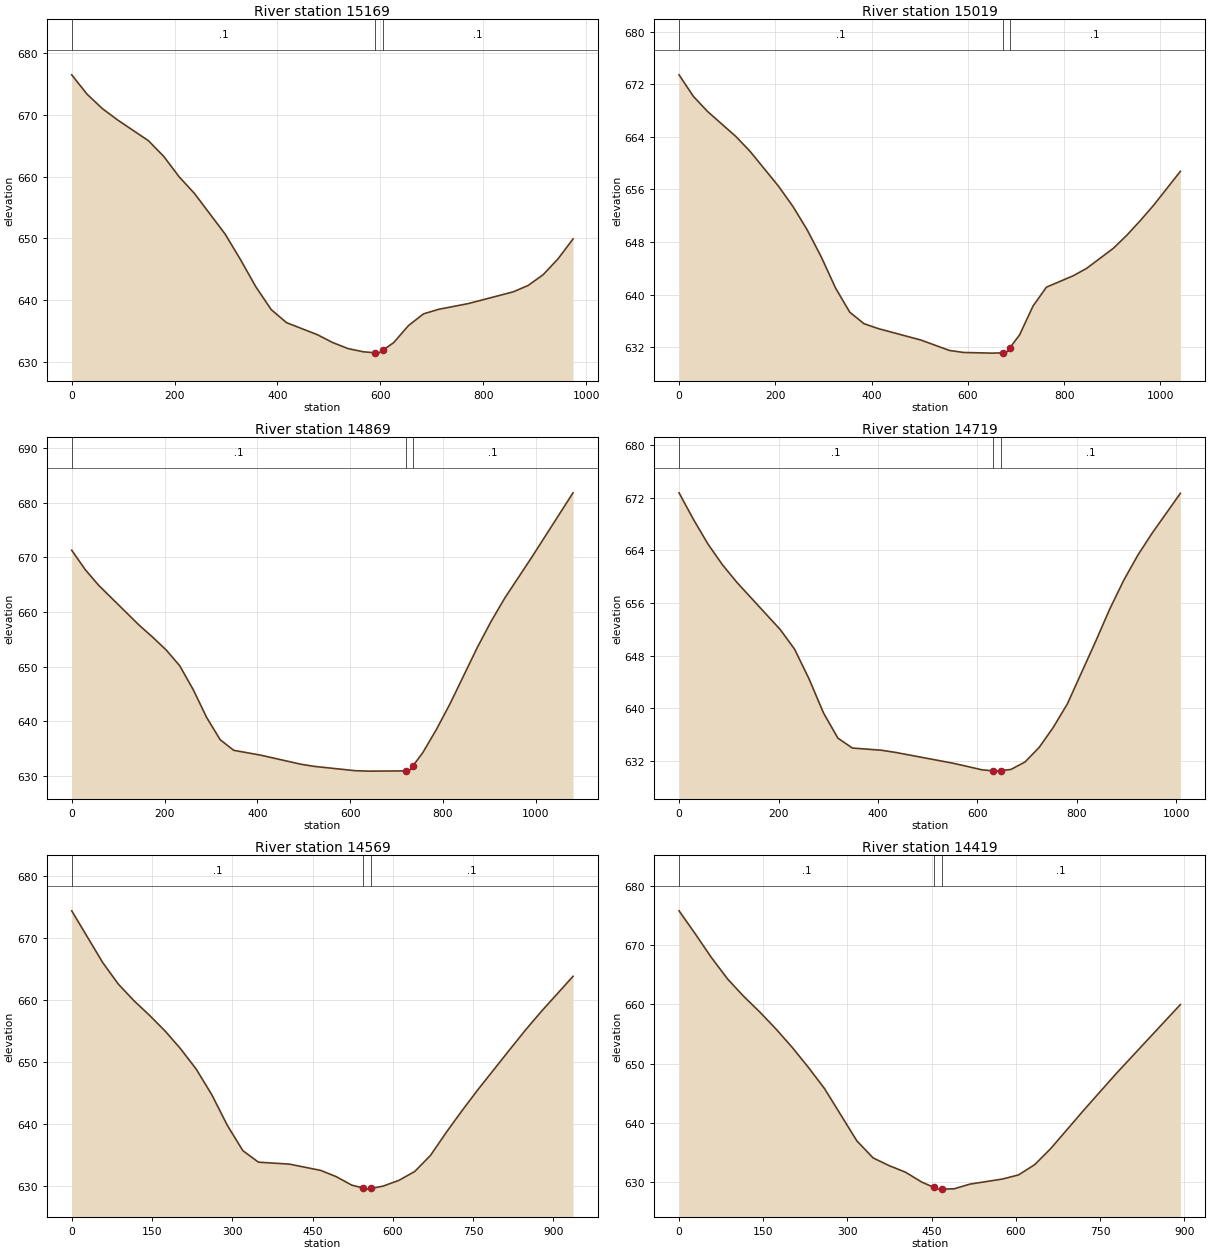
Type RM Length L Ch R = 1 ,15169,149.6,150,152.8
XS GIS Cut Line= 3
     2199248.138      638271.224     2199537.237      638793.299
     2199882.552      638946.852
#Sta/Elev= 30
       0  676.53    29.8  673.39    59.7  671.04    89.5  669.19   149.2  665.84
   179.0  663.29   208.9  659.98   238.7  657.28   298.4  650.68   328.2  646.54
   358.1  642.13   387.9  638.44   417.7  636.32   477.4  634.38   507.3  633.10
   537.1  632.12   566.9  631.60   589.3  631.44   596.8  631.38   604.3  631.82
   625.8  633.07   654.9  635.86   684.0  637.75   713.1  638.48   771.2  639.42
   858.4  641.32   887.5  642.36   916.6  644.10   945.6  646.68   974.7  649.90
#Mann= 3 , 0 , 0
       0     0.1       0   589.3   0.045       0   604.3     0.1       0
Bank Sta=589.3,604.3
Exp/Cntr=0.3,0.1

Type RM Length L Ch R = 1 ,15019,152.1,150,181.8
XS GIS Cut Line= 3
     2199228.135      638296.425     2199475.384      638929.696
     2199786.146      639114.961
#Sta/Elev= 30
       0  673.42    29.6  670.16    59.1  667.86   118.2  664.04   147.8  661.77
   206.9  656.47   236.5  653.43   266.0  649.89   295.6  645.73   325.1  641.03
   354.7  637.34   384.2  635.60   413.8  634.85   502.5  633.11   561.6  631.53
   591.2  631.22   650.3  631.12   672.3  631.16   679.8  631.18   687.3  631.91
   707.7  633.91   735.5  638.28   763.3  641.14   819.0  642.88   846.8  644.00
   902.5  647.06   930.3  649.03   958.1  651.24   986.0  653.59  1041.6  658.75
#Mann= 3 , 0 , 0
       0     0.1       0   672.3   0.045       0   687.3     0.1       0
Bank Sta=672.3,687.3
Exp/Cntr=0.3,0.1

Type RM Length L Ch R = 1 ,14869,148.8,150,156.6
XS GIS Cut Line= 3
     2199200.978      638313.612     2199370.640      639020.594
     2199246.202      639351.218
#Sta/Elev= 27
       0  671.28    29.1  667.74    58.2  664.86   145.4  657.57   174.5  655.38
   203.6  653.04   232.7  650.16   261.7  645.81   290.8  640.70   319.9  636.64
   349.0  634.70   407.2  633.81   494.4  632.14   523.5  631.75   610.7  630.97
   639.8  630.89   719.6  630.93   727.1  630.92   734.6  631.77   756.5  634.26
   785.9  638.51   815.4  643.23   874.2  653.53   903.7  658.26   933.1  662.52
   992.0  670.08  1080.3  681.78
#Mann= 3 , 0 , 0
       0     0.1       0   719.6   0.045       0   734.6     0.1       0
Bank Sta=719.6,734.6
Exp/Cntr=0.3,0.1

Type RM Length L Ch R = 1 ,14719,147.3,150,150.2
XS GIS Cut Line= 3
     2199172.008      638303.020     2199246.107      638937.549
     2199021.361      639230.245
#Sta/Elev= 29
       0  672.75    29.0  668.70    58.1  664.97    87.1  661.83   116.2  659.15
   203.3  651.98   232.3  648.98   261.3  644.48   290.4  639.30   319.4  635.46
   348.5  633.96   406.5  633.63   435.6  633.29   551.7  631.64   609.8  630.64
   631.3  630.50   638.8  630.45   646.3  630.52   667.2  630.70   695.6  631.84
   724.0  634.05   752.4  637.10   780.8  640.68   837.6  650.17   865.9  655.08
   894.3  659.49   922.7  663.31   951.1  666.61  1007.9  672.67
#Mann= 3 , 0 , 0
       0     0.1       0   631.3   0.045       0   646.3     0.1       0
Bank Sta=631.3,646.3
Exp/Cntr=0.3,0.1

Type RM Length L Ch R = 1 ,14569,144.6,150,145.1
XS GIS Cut Line= 3
     2199142.794      638289.144     2199131.338      638841.221
     2198894.163      639143.626
#Sta/Elev= 30
       0  674.43    58.1  666.04    87.2  662.57   116.2  659.90   145.3  657.54
   174.4  655.00   203.4  652.12   232.5  648.84   261.6  644.71   290.6  639.76
   319.7  635.65   348.8  633.79   406.9  633.47   465.0  632.46   494.1  631.45
   523.1  630.08   544.7  629.60   552.2  629.43   559.7  629.55   581.8  629.92
   611.3  630.85   640.9  632.29   670.4  634.90   700.0  638.64   729.6  642.17
   759.1  645.54   818.3  651.99   847.8  655.17   877.4  658.17   936.5  663.84
#Mann= 3 , 0 , 0
       0     0.1       0   544.7   0.045       0   559.7     0.1       0
Bank Sta=544.7,559.7
Exp/Cntr=0.3,0.1

Type RM Length L Ch R = 1 ,14419,146.7,150,145.3
XS GIS Cut Line= 3
     2199112.793      638276.780     2199030.506      638730.253
     2198840.053      639118.098
#Sta/Elev= 27
       0  675.75    28.8  671.88    57.6  667.88    86.4  664.27   115.2  661.33
   144.0  658.68   172.8  655.82   201.6  652.73   230.4  649.36   259.2  645.78
   316.8  636.97   345.7  634.10   374.5  632.79   403.3  631.70   432.1  630.04
   453.4  629.15   460.9  628.84   468.4  628.85   489.7  628.89   518.5  629.69
   576.1  630.54   604.9  631.24   633.7  632.98   662.5  635.72   720.1  642.06
   777.7  648.21   893.0  659.95
#Mann= 3 , 0 , 0
       0     0.1       0   453.4   0.045       0   468.4     0.1       0
Bank Sta=453.4,468.4
Exp/Cntr=0.3,0.1

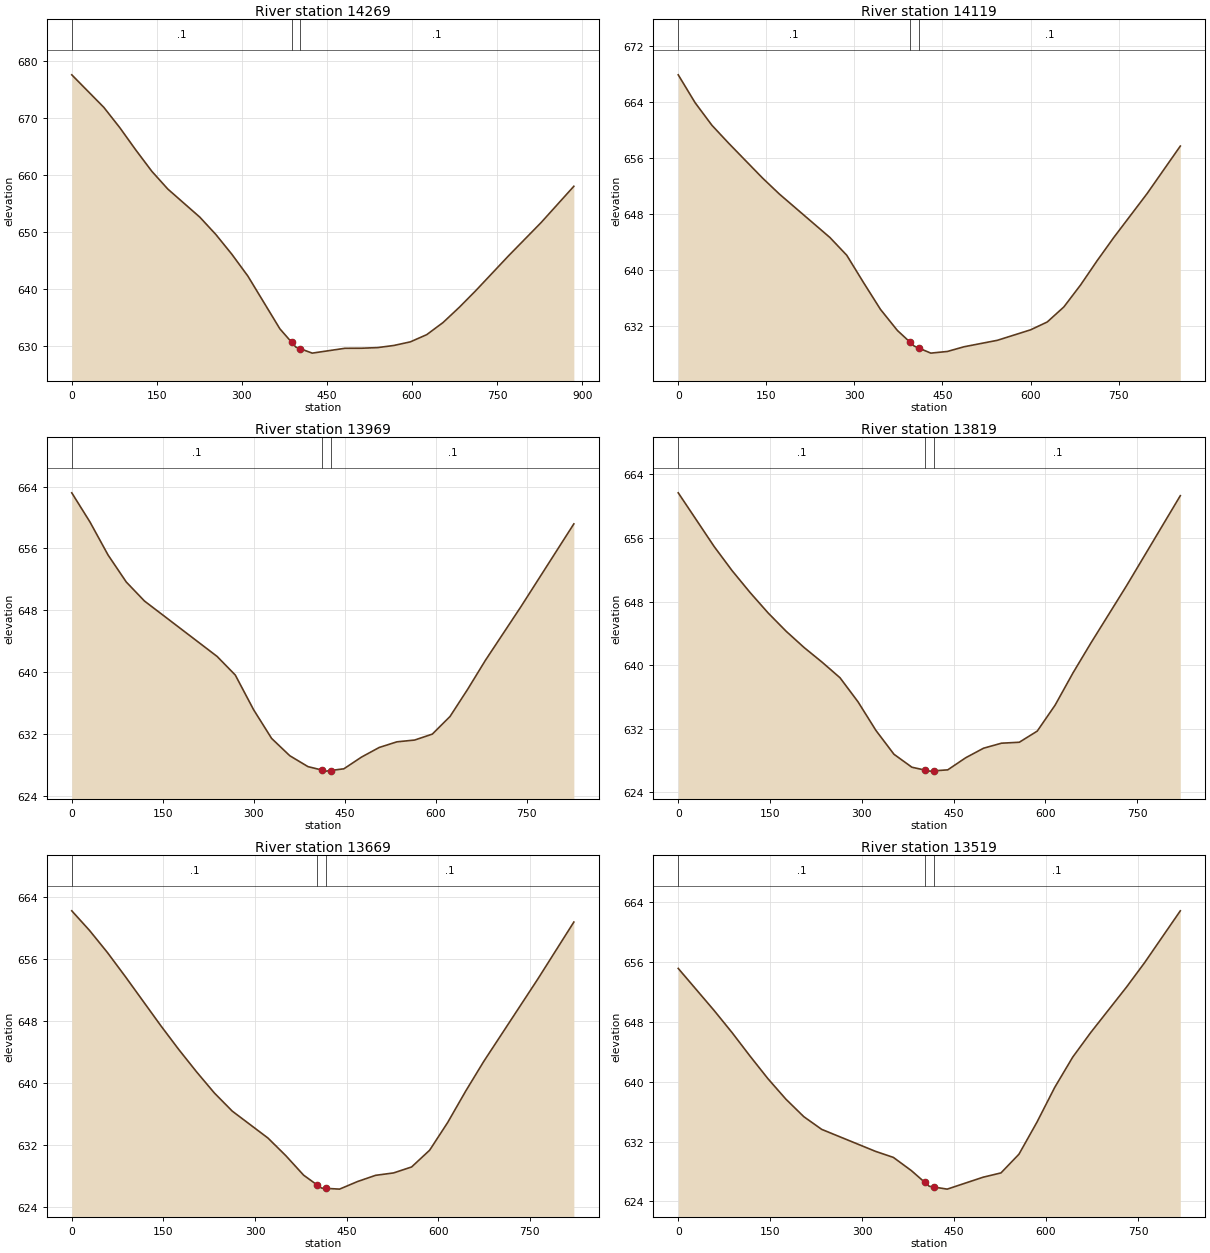
Type RM Length L Ch R = 1 ,14269,163.3,150,145.7
XS GIS Cut Line= 3
     2198999.127      638242.957     2198921.456      638630.524
     2198801.966      639105.854
#Sta/Elev= 27
       0  677.58    56.5  671.87    84.7  668.30   112.9  664.38   141.2  660.63
   169.4  657.51   225.9  652.57   254.1  649.53   282.3  646.06   310.6  642.22
   367.0  632.96   387.8  630.59   395.3  629.74   402.8  629.47   424.1  628.69
   481.8  629.54   510.6  629.55   539.4  629.66   568.3  630.04   597.1  630.67
   625.9  631.93   654.8  634.07   683.6  636.76   712.4  639.66   770.1  645.77
   827.7  651.63   885.4  658.00
#Mann= 3 , 0 , 0
       0     0.1       0   387.8   0.045       0   402.8     0.1       0
Bank Sta=387.8,402.8
Exp/Cntr=0.3,0.1

Type RM Length L Ch R = 1 ,14119,146.7,150,144.2
XS GIS Cut Line= 3
     2198625.272      638281.644     2198776.827      638653.744
     2198761.790      639106.738
#Sta/Elev= 26
       0  667.92    28.7  663.94    57.4  660.71    86.1  658.13   143.5  653.18
   172.2  650.89   258.3  644.68   287.0  642.14   315.7  638.22   344.4  634.41
   373.1  631.41   394.3  629.76   401.8  629.17   409.3  628.90   430.1  628.16
   458.4  628.40   486.8  629.07   543.4  629.99   600.1  631.49   628.4  632.61
   656.7  634.76   685.1  637.89   713.4  641.37   741.7  644.68   798.4  650.95
   855.0  657.74
#Mann= 3 , 0 , 0
       0     0.1       0   394.3   0.045       0   409.3     0.1       0
Bank Sta=394.3,409.3
Exp/Cntr=0.3,0.1

Type RM Length L Ch R = 1 ,13969,144.2,150,154.4
XS GIS Cut Line= 3
     2198540.101      638308.083     2198640.769      638715.353
     2198720.903      639115.878
#Sta/Elev= 25
       0  663.20    30.0  659.43    59.9  655.15    89.9  651.66   119.9  649.20
   239.7  642.03   269.7  639.62   299.7  635.16   329.6  631.42   359.6  629.18
   389.6  627.77     412  627.34   419.5  627.19     427  627.27   448.7  627.49
   477.9  629.01   507.0  630.25   536.2  630.98   565.4  631.21   594.6  631.98
   623.8  634.26   652.9  637.78   682.1  641.52   740.5  648.44   828.0  659.18
#Mann= 3 , 0 , 0
       0     0.1       0     412   0.045       0     427     0.1       0
Bank Sta=412,427
Exp/Cntr=0.3,0.1

Type RM Length L Ch R = 1 ,13819,150.6,150,150.5
XS GIS Cut Line= 3
     2198495.684      638311.630     2198491.376      638722.807
     2198491.376      639132.007
#Sta/Elev= 27
       0  661.66    58.7  654.91    88.1  651.87   117.5  649.12   146.9  646.56
   176.2  644.27   205.6  642.22   235.0  640.38   264.3  638.42   293.7  635.40
   323.1  631.79   352.5  628.80   381.8  627.17   403.7  626.80   411.2  626.68
   418.7  626.72   440.4  626.84   469.7  628.36   498.9  629.56   528.1  630.19
   557.3  630.31   586.6  631.71   615.8  634.97   645.0  639.02   674.3  642.78
   732.7  650.00   820.4  661.30
#Mann= 3 , 0 , 0
       0     0.1       0   403.7   0.045       0   418.7     0.1       0
Bank Sta=403.7,418.7
Exp/Cntr=0.3,0.1

Type RM Length L Ch R = 1 ,13669,151.6,150,147.4
XS GIS Cut Line= 3
     2198336.322      638296.669     2198342.792      638705.473
     2198334.020      639118.533
#Sta/Elev= 26
       0  662.20    29.2  659.66    58.4  656.82    87.6  653.73   146.0  647.36
   175.2  644.31   204.4  641.42   233.6  638.69   262.8  636.36   321.2  632.89
   350.4  630.62   379.6  628.10   401.4  626.86   408.9  626.44   416.4  626.40
   438.4  626.30   467.9  627.28   497.4  628.08   526.9  628.39   556.4  629.16
   585.9  631.32   615.4  634.89   644.9  638.94   674.4  642.76   763.0  653.40
   822.0  660.75
#Mann= 3 , 0 , 0
       0     0.1       0   401.4   0.045       0   416.4     0.1       0
Bank Sta=401.4,416.4
Exp/Cntr=0.3,0.1

Type RM Length L Ch R = 1 ,13519,148,150,150.3
XS GIS Cut Line= 3
     2198156.838      638311.884     2198193.632      638719.728
     2198230.427      639127.572
#Sta/Elev= 25
       0  655.16    58.5  649.54    87.8  646.58   117.0  643.45   146.2  640.43
   175.5  637.69   204.8  635.34   234.0  633.64   321.8  630.70   351.0  629.89
   380.2  628.13     402  626.57   409.5  626.03     417  625.93   438.8  625.65
   497.2  627.24   526.5  627.82   555.8  630.32   585.0  634.58   614.2  639.26
   643.5  643.30   672.8  646.58   731.2  652.66   760.5  655.90   819.0  662.86
#Mann= 3 , 0 , 0
       0     0.1       0     402   0.045       0     417     0.1       0
Bank Sta=402,417
Exp/Cntr=0.3,0.1