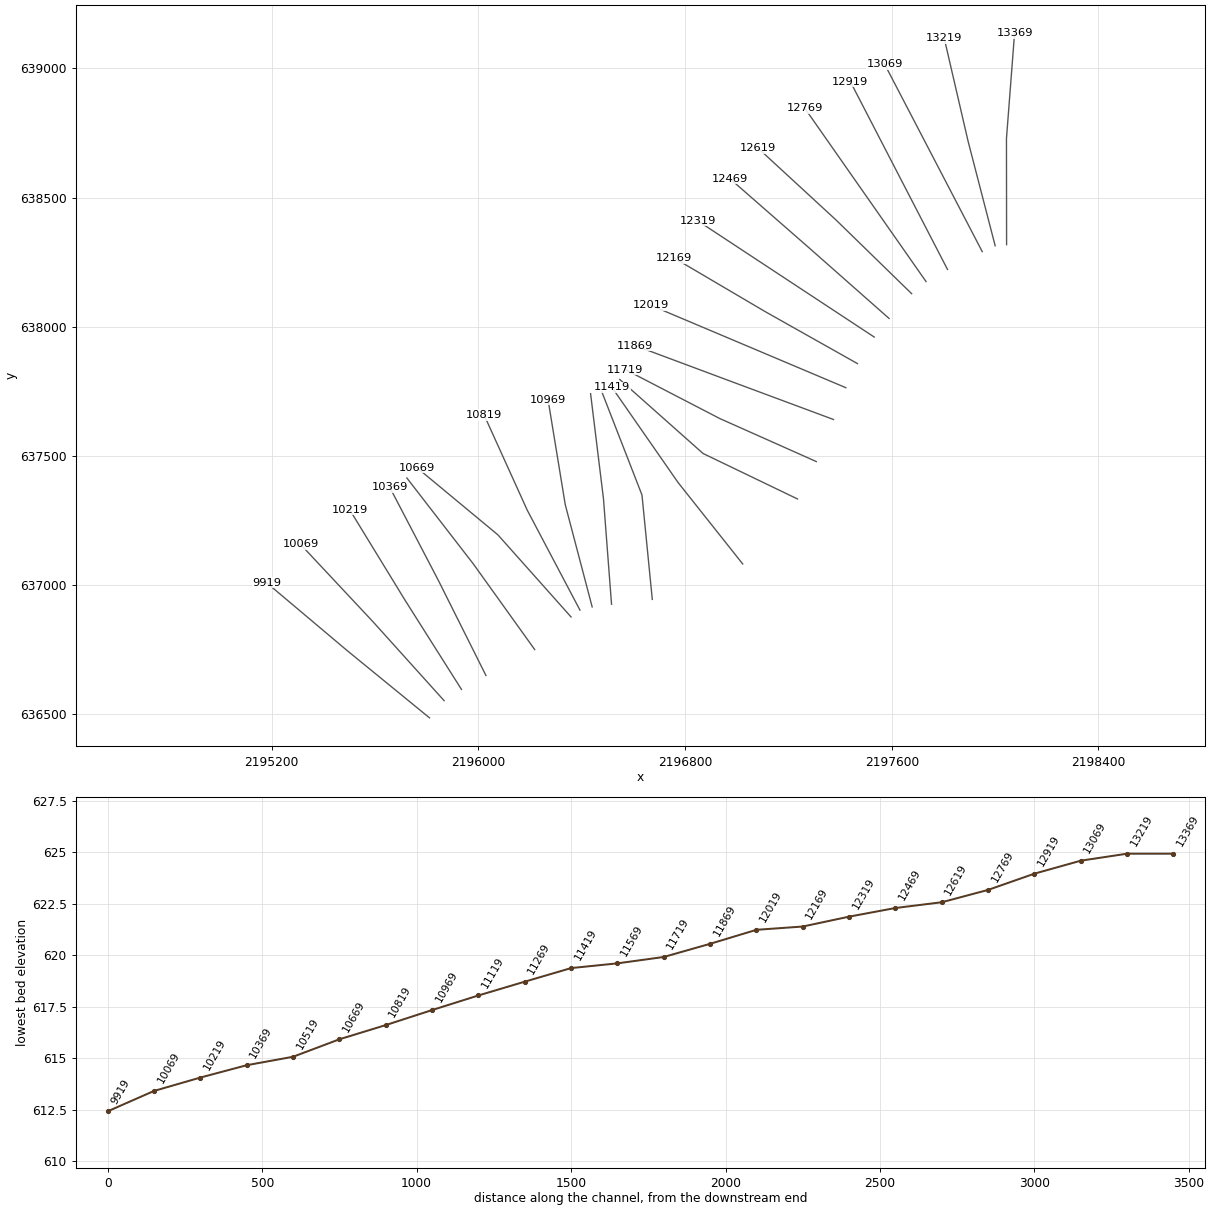
HEC-RAS study LFRFBUCKRV.prj: LFRFBUCKRV

--- LFRFBUCKRV.g01 (geometry) --- (continued)

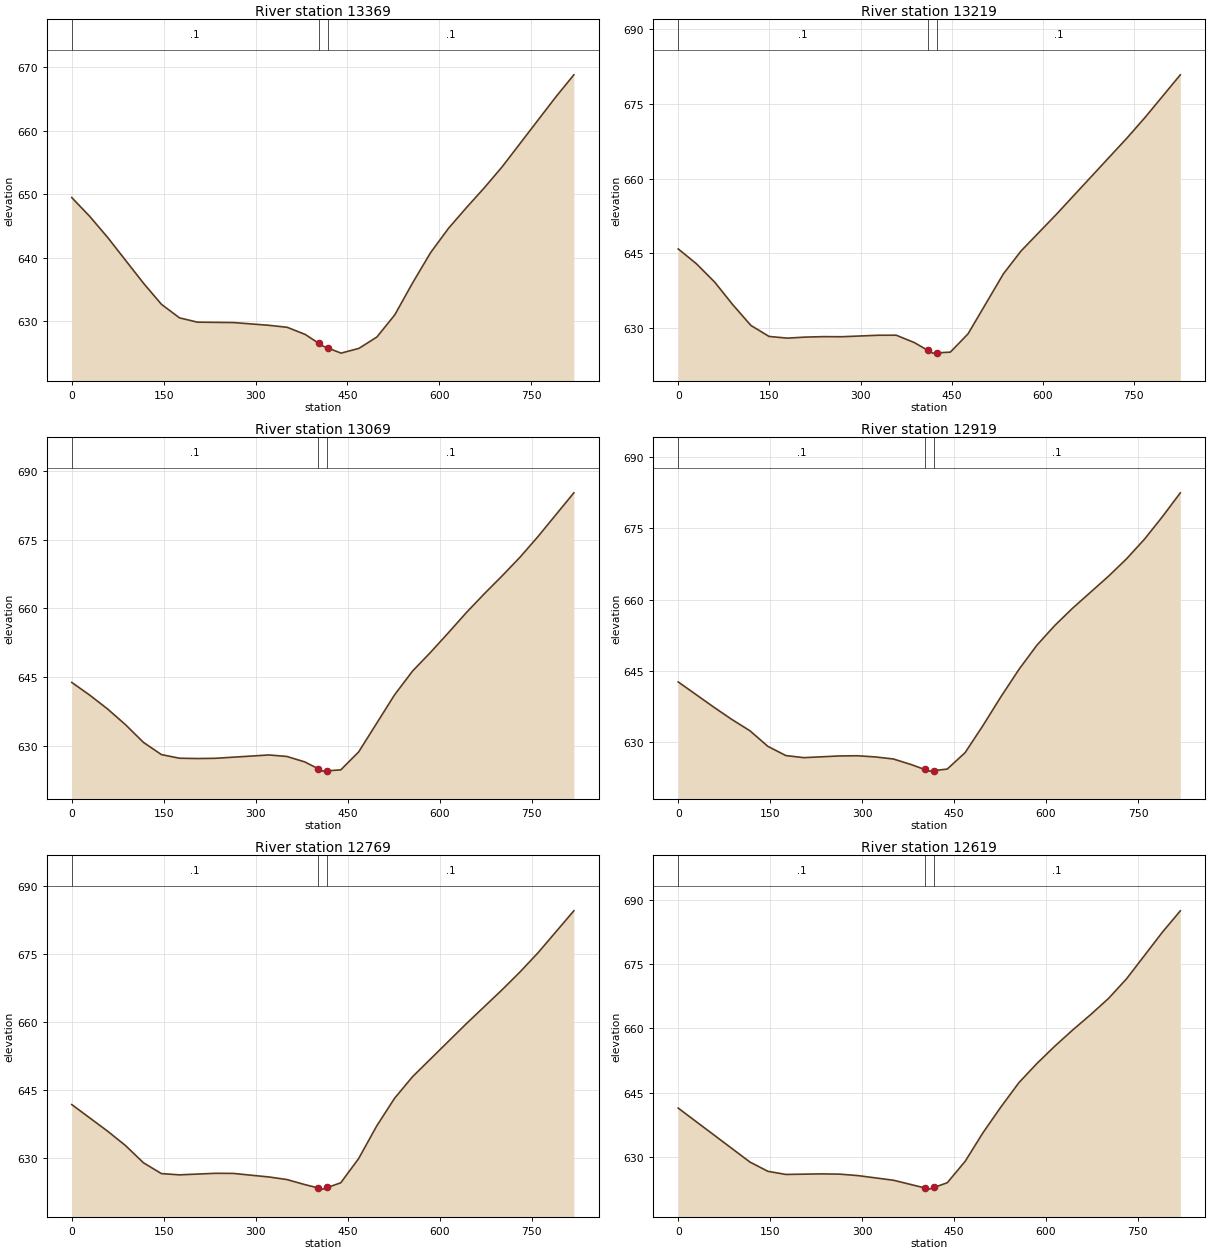
Type RM Length L Ch R = 1 ,13369,144.1,150,156.7
XS GIS Cut Line= 3
     2198044.396      638317.865     2198043.900      638728.299
     2198075.295      639136.428
#Sta/Elev= 26
       0  649.46    29.3  646.50    58.6  643.18   117.3  635.94   146.6  632.62
   175.9  630.50   205.2  629.82   263.8  629.76   322.5  629.32   351.8  629.01
   381.1  627.89   402.9  626.51   410.4  626.04   417.9  625.76   439.7  624.94
   468.9  625.69   498.2  627.48   527.4  630.97   556.6  636.02   585.9  640.78
   615.1  644.61   644.3  647.86   673.6  651.00   702.8  654.32   790.5  665.34
   819.8  668.81
#Mann= 3 , 0 , 0
       0     0.1       0   402.9   0.045       0   417.9     0.1       0
Bank Sta=402.9,417.9
Exp/Cntr=0.3,0.1

Type RM Length L Ch R = 1 ,13219,144.9,150,155.7
XS GIS Cut Line= 3
     2198000.202      638313.610     2197895.213      638718.867
     2197803.202      639116.028
#Sta/Elev= 24
       0  645.86    29.9  642.89    59.8  639.23    89.7  634.67   119.6  630.50
   149.5  628.29   179.4  627.95   209.3  628.16   239.2  628.25   269.1  628.23
   328.9  628.53   358.8  628.54   388.7  627.05   411.1  625.47   418.6  624.94
   426.1  624.99   447.8  625.14   476.9  628.80   535.1  640.85   564.2  645.45
   622.5  652.83   739.0  668.19   768.1  672.24   826.3  680.82
#Mann= 3 , 0 , 0
       0     0.1       0   411.1   0.045       0   426.1     0.1       0
Bank Sta=411.1,426.1
Exp/Cntr=0.3,0.1

Type RM Length L Ch R = 1 ,13069,150.1,150,149.9
XS GIS Cut Line= 3
     2197950.155      638290.885     2197761.032      638654.097
     2197571.908      639017.308
#Sta/Elev= 27
       0  643.91    29.2  641.15    58.5  638.12    87.8  634.69   117.0  630.85
   146.2  628.20   175.5  627.41   204.8  627.34   234.0  627.39   321.8  628.12
   351.0  627.79   380.2  626.60     402  625.11   409.5  624.60     417  624.67
   438.8  624.87   468.0  628.78   526.5  641.19   555.8  646.36   585.0  650.42
   614.2  654.69   643.5  659.08   672.8  663.18   702.0  667.09   731.2  671.16
   760.5  675.65   819.0  685.17
#Mann= 3 , 0 , 0
       0     0.1       0     402   0.045       0     417     0.1       0
Bank Sta=402,417
Exp/Cntr=0.3,0.1

Type RM Length L Ch R = 1 ,12919,147,150,153
XS GIS Cut Line= 3
     2197815.665      638222.022     2197627.515      638585.739
     2197439.364      638949.455
#Sta/Elev= 28
       0  642.71    58.5  637.37    87.8  634.80   117.0  632.45   146.2  629.18
   175.5  627.24   204.8  626.80   263.2  627.16   292.5  627.20   321.8  626.95
   351.0  626.52   380.2  625.34     402  624.32   409.5  623.97     417  624.08
   438.8  624.40   468.0  627.86   497.2  633.57   526.5  639.62   555.8  645.35
   585.0  650.42   614.2  654.57   643.5  658.23   702.0  664.94   731.2  668.57
   760.5  672.70   789.8  677.43   819.0  682.45
#Mann= 3 , 0 , 0
       0     0.1       0     402   0.045       0     417     0.1       0
Bank Sta=402,417
Exp/Cntr=0.3,0.1

Type RM Length L Ch R = 1 ,12769,145.8,150,154.9
XS GIS Cut Line= 3
     2197732.521      638175.165     2197497.801      638510.720
     2197263.081      638846.274
#Sta/Elev= 24
       0  641.84    58.5  635.97    87.8  632.78   117.0  628.99   146.2  626.61
   175.5  626.33   234.0  626.67   263.2  626.65   321.8  625.86   351.0  625.29
   380.2  624.18     402  623.44   409.5  623.18     417  623.54   438.8  624.58
   468.0  629.93   497.2  637.07   526.5  643.22   555.8  647.98   643.5  659.67
   702.0  667.18   731.2  671.11   760.5  675.33   819.0  684.60
#Mann= 3 , 0 , 0
       0     0.1       0     402   0.045       0     417     0.1       0
Bank Sta=402,417
Exp/Cntr=0.3,0.1

Type RM Length L Ch R = 1 ,12619,148.9,150,150.6
XS GIS Cut Line= 3
     2197676.818      638128.167     2197383.434      638414.135
     2197082.274      638691.560
#Sta/Elev= 24
       0  641.45   117.1  628.88   146.3  626.73   175.6  626.00   234.1  626.13
   263.4  626.07   292.6  625.74   351.2  624.65   402.2  622.86   409.7  622.58
   417.2  622.96   439.0  624.07   468.2  629.07   497.4  635.75   526.7  641.76
   555.9  647.39   585.2  651.84   614.4  655.88   643.7  659.66   672.9  663.23
   702.2  667.02   731.4  671.56   789.9  682.42   819.2  687.41
#Mann= 3 , 0 , 0
       0     0.1       0   402.2   0.045       0   417.2     0.1       0
Bank Sta=402.2,417.2
Exp/Cntr=0.3,0.1

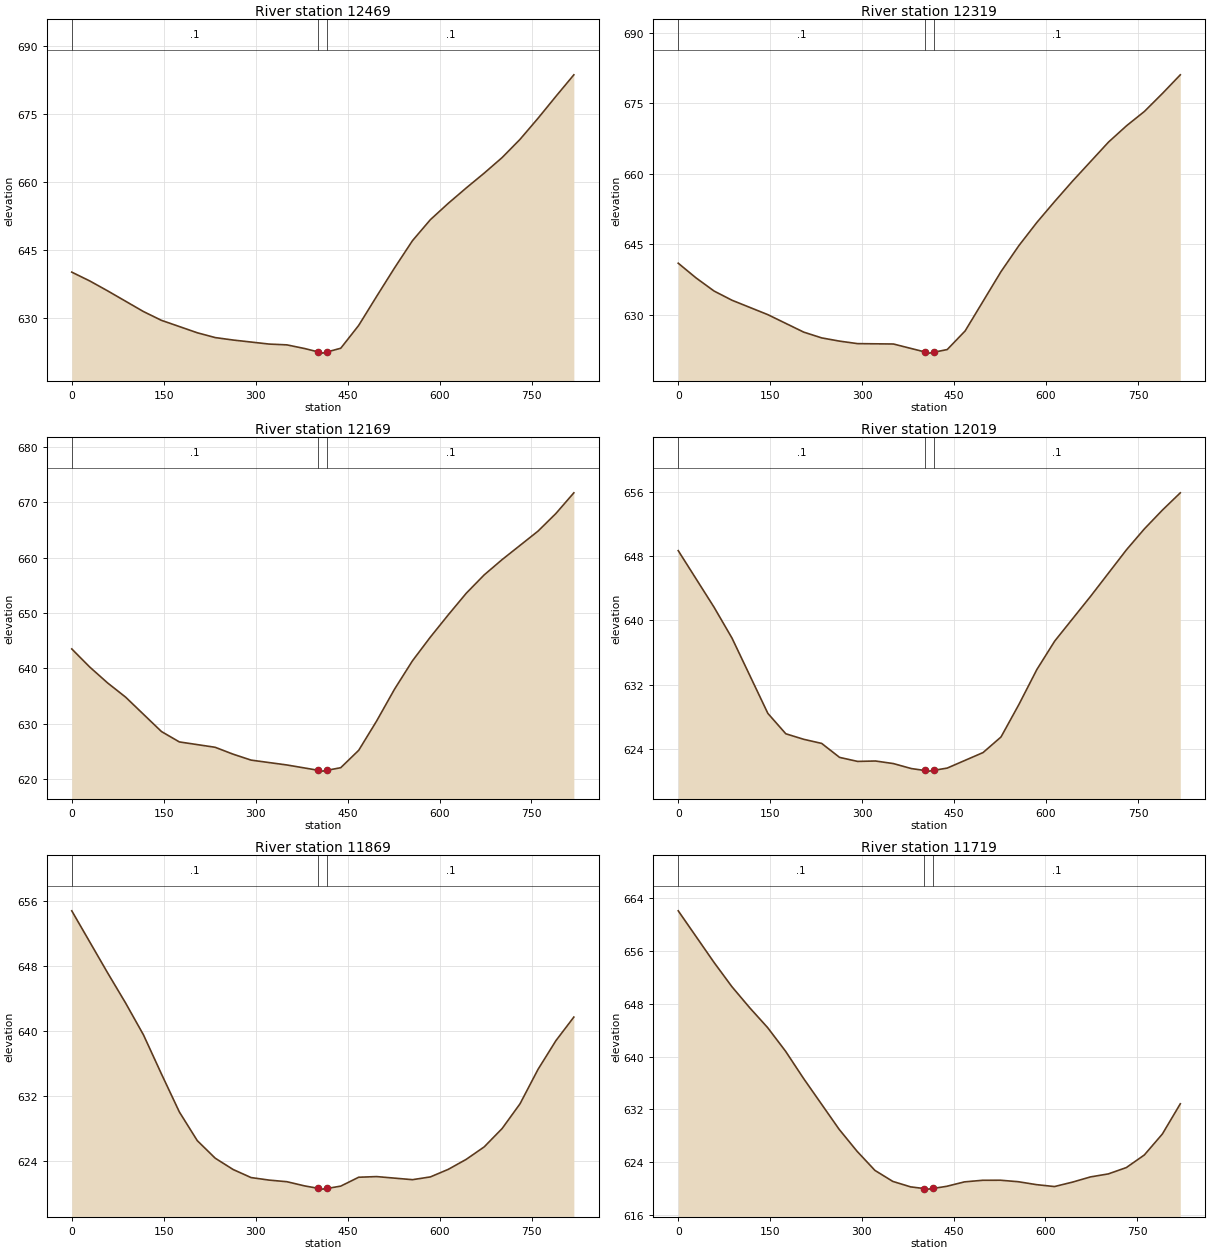
Type RM Length L Ch R = 1 ,12469,146.8,150,153.1
XS GIS Cut Line= 3
     2197589.386      638032.351     2197282.347      638303.316
     2196974.027      638572.812
#Sta/Elev= 28
       0  640.17    29.2  638.24    58.5  636.04   117.0  631.47   146.2  629.54
   204.8  626.79   234.0  625.73   263.2  625.19   321.8  624.30   351.0  624.12
   380.3  623.30     402  622.56   409.5  622.30     417  622.58   438.8  623.38
   468.0  628.41   497.3  634.82   526.5  641.10   555.8  647.12   585.0  651.75
   614.3  655.37   643.5  658.75   672.8  662.02   702.0  665.45   731.2  669.47
   760.5  674.11   789.8  678.97   819.0  683.71
#Mann= 3 , 0 , 0
       0     0.1       0     402   0.045       0     417     0.1       0
Bank Sta=402,417
Exp/Cntr=0.3,0.1

Type RM Length L Ch R = 1 ,12319,148.4,150,151.1
XS GIS Cut Line= 3
     2197532.028      637960.233     2197190.051      638185.493
     2196848.074      638410.753
#Sta/Elev= 25
       0  641.00    29.2  637.86    58.5  635.08    87.8  633.12   146.2  630.06
   204.8  626.34   234.0  625.12   263.2  624.43   292.5  623.90   351.0  623.82
     402  622.14   409.5  621.88     417  622.07   438.8  622.64   468.0  626.60
   526.5  639.21   555.8  644.76   585.0  649.67   614.2  654.15   643.5  658.50
   702.0  666.77   731.2  670.22   760.5  673.28   789.8  677.09   819.0  681.06
#Mann= 3 , 0 , 0
       0     0.1       0     402   0.045       0     417     0.1       0
Bank Sta=402,417
Exp/Cntr=0.3,0.1

Type RM Length L Ch R = 1 ,12169,147.5,150,153
XS GIS Cut Line= 3
     2197467.191      637857.443     2197110.334      638058.484
     2196757.465      638266.234
#Sta/Elev= 26
       0  643.49    29.3  640.22    58.5  637.34    87.8  634.78   146.3  628.56
   175.5  626.68   234.0  625.71   263.3  624.46   292.6  623.39   351.1  622.51
   402.1  621.55   409.6  621.40   417.1  621.56   438.8  622.02   468.1  625.16
   497.3  630.45   526.6  636.22   555.8  641.34   585.1  645.64   614.3  649.66
   643.6  653.56   672.8  656.87   702.1  659.64   760.6  664.78   789.8  667.97
   819.1  671.71
#Mann= 3 , 0 , 0
       0     0.1       0   402.1   0.045       0   417.1     0.1       0
Bank Sta=402.1,417.1
Exp/Cntr=0.3,0.1

Type RM Length L Ch R = 1 ,12019,149,150,151
XS GIS Cut Line= 3
     2197422.292      637764.137     2197045.077      637923.507
     2196667.861      638082.877
#Sta/Elev= 26
       0  648.69    58.5  641.64    87.8  637.79   146.2  628.43   175.5  625.89
   204.8  625.20   234.0  624.69   263.2  622.95   292.5  622.45   321.8  622.50
   351.0  622.18   380.2  621.56     402  621.32   409.5  621.24     417  621.34
   438.8  621.62   497.2  623.55   526.5  625.49   555.8  629.55   585.0  633.89
   614.2  637.44   672.8  643.02   731.2  648.80   760.5  651.41   789.8  653.74
   819.0  655.89
#Mann= 3 , 0 , 0
       0     0.1       0     402   0.045       0     417     0.1       0
Bank Sta=402,417
Exp/Cntr=0.3,0.1

Type RM Length L Ch R = 1 ,11869,151.3,150,147.1
XS GIS Cut Line= 3
     2197374.492      637641.075     2196990.654      637783.760
     2196606.989      637926.907
#Sta/Elev= 29
       0  654.74    58.5  647.12    87.8  643.42   117.0  639.50   146.2  634.72
   175.5  630.04   204.8  626.51   234.0  624.36   263.2  622.97   292.5  621.98
   321.8  621.67   351.0  621.47   380.2  620.95     402  620.66   409.5  620.56
     417  620.65   438.8  620.93   468.0  622.02   497.2  622.10   555.8  621.72
   585.0  622.06   614.2  622.99   643.5  624.22   672.8  625.75   702.0  628.00
   731.2  631.04   760.5  635.26   789.8  638.80   819.0  641.69
#Mann= 3 , 0 , 0
       0     0.1       0     402   0.045       0     417     0.1       0
Bank Sta=402,417
Exp/Cntr=0.3,0.1

Type RM Length L Ch R = 1 ,11719,150.7,150,144.4
XS GIS Cut Line= 3
     2197307.812      637478.253     2196934.107      637644.842
     2196568.820      637834.224
#Sta/Elev= 29
       0  662.13    58.4  654.32    87.7  650.63   116.9  647.42   146.1  644.42
   175.4  640.84   204.6  636.74   263.0  628.99   292.2  625.67   321.5  622.76
   350.7  621.09   379.9  620.26   401.7  620.01   409.2  619.92   416.7  620.03
   438.5  620.34   467.9  621.02   497.3  621.26   526.7  621.27   556.1  621.04
   585.5  620.60   614.9  620.31   644.3  620.98   673.7  621.77   703.0  622.23
   732.4  623.19   761.8  625.10   791.2  628.27   820.6  632.86
#Mann= 3 , 0 , 0
       0     0.1       0   401.7   0.045       0   416.7     0.1       0
Bank Sta=401.7,416.7
Exp/Cntr=0.3,0.1

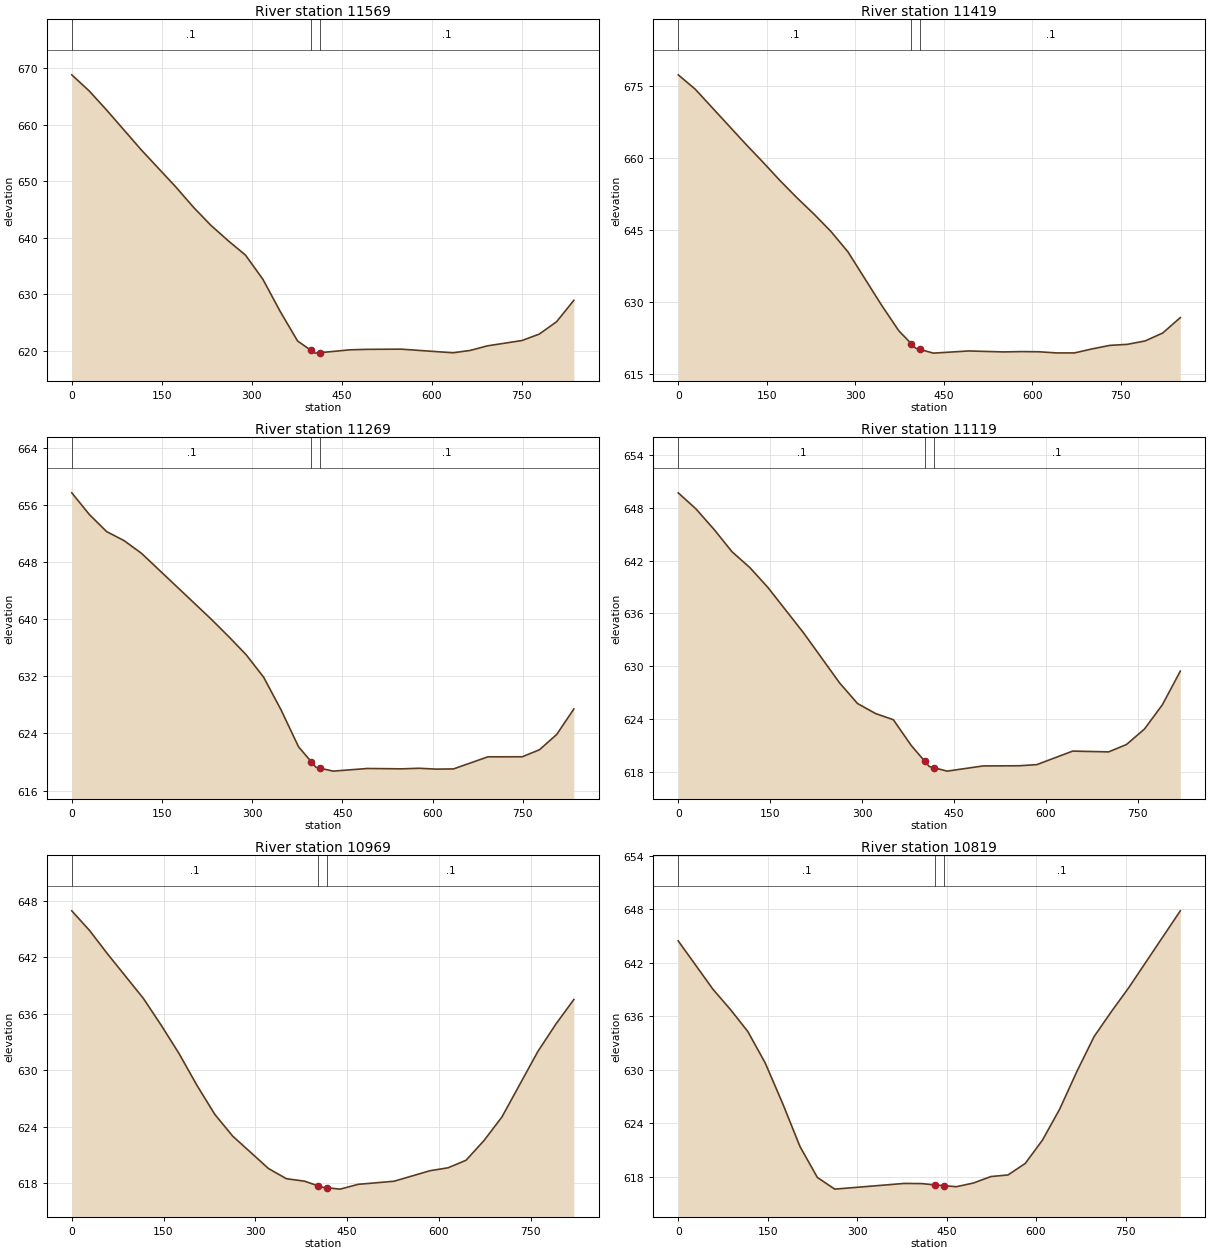
Type RM Length L Ch R = 1 ,11569,160.1,150,144.6
XS GIS Cut Line= 3
     2197234.976      637333.520     2196869.523      637509.479
     2196546.842      637796.041
#Sta/Elev= 25
       0  668.82    29.0  665.98    57.9  662.62   115.9  655.55   173.8  648.96
   202.8  645.42   231.8  642.23   260.8  639.49   289.7  636.94   318.7  632.67
   347.7  626.95   376.6  621.75   398.1  620.16   405.6  619.61   413.1  619.68
   463.2  620.19   491.9  620.28   549.5  620.31   635.8  619.67   664.5  620.09
   693.3  620.90   750.8  621.84   779.6  622.98   808.4  625.16   837.2  628.95
#Mann= 3 , 0 , 0
       0     0.1       0   398.1   0.045       0   413.1     0.1       0
Bank Sta=398.1,413.1
Exp/Cntr=0.3,0.1

Type RM Length L Ch R = 1 ,11419,163,150,144.7
XS GIS Cut Line= 3
     2197022.949      637081.894     2196772.607      637397.260
     2196516.768      637765.416
#Sta/Elev= 27
       0  677.33    28.8  674.34   115.0  662.83   143.8  659.12   172.6  655.30
   201.3  651.72   230.1  648.33   258.8  644.72   287.6  640.48   345.1  629.28
   373.9  624.03   395.1  621.34   402.6  620.39   410.1  620.14   432.5  619.38
   492.3  619.83   552.1  619.63   582.0  619.70   611.9  619.66   641.8  619.42
   671.6  619.42   701.5  620.26   731.4  620.99   761.3  621.21   791.2  621.91
   821.1  623.56   851.0  626.78
#Mann= 3 , 0 , 0
       0     0.1       0   395.1   0.045       0   410.1     0.1       0
Bank Sta=395.1,410.1
Exp/Cntr=0.3,0.1

Type RM Length L Ch R = 1 ,11269,150.4,150,144.3
XS GIS Cut Line= 3
     2196672.915      636944.651     2196632.991      637348.776
     2196477.557      637748.421
#Sta/Elev= 25
       0  657.67    29.0  654.66    58.0  652.24    87.0  650.98   116.0  649.20
   232.0  639.98   261.1  637.54   290.1  635.00   319.1  631.86   348.1  627.28
   377.1  622.13   398.6  620.00   406.1  619.26   413.6  619.12   434.7  618.72
   491.8  619.09   549.0  619.04   577.6  619.12   606.2  619.00   634.8  619.03
   692.0  620.72   749.1  620.73   777.7  621.71   806.3  623.84   834.9  627.42
#Mann= 3 , 0 , 0
       0     0.1       0   398.6   0.045       0   413.6     0.1       0
Bank Sta=398.6,413.6
Exp/Cntr=0.3,0.1

Type RM Length L Ch R = 1 ,11119,145.9,150,150.9
XS GIS Cut Line= 3
     2196515.158      636925.936     2196483.921      637334.301
     2196434.070      637740.918
#Sta/Elev= 25
       0  649.73    29.2  647.88    58.5  645.56    87.8  643.02   117.0  641.21
   146.3  638.96   204.8  633.76   263.3  628.09   292.5  625.75   321.8  624.61
   351.0  623.90   380.3  620.96   402.1  619.19   409.6  618.58   417.1  618.44
   438.8  618.05   497.3  618.64   555.9  618.66   585.1  618.79   643.6  620.33
   702.2  620.24   731.4  621.08   760.7  622.84   790.0  625.61   819.2  629.43
#Mann= 3 , 0 , 0
       0     0.1       0   402.1   0.045       0   417.1     0.1       0
Bank Sta=402.1,417.1
Exp/Cntr=0.3,0.1

Type RM Length L Ch R = 1 ,10969,144.7,150,155.9
XS GIS Cut Line= 3
     2196440.146      636915.634     2196336.010      637311.354
     2196269.501      637717.180
#Sta/Elev= 26
       0  646.96    29.2  644.86    58.5  642.37   116.9  637.65   146.1  634.79
   175.4  631.76   204.6  628.38   233.8  625.29   263.0  622.98   321.5  619.53
   350.7  618.45   380.0  618.19   401.7  617.71   409.2  617.54   416.7  617.49
   438.6  617.34   467.9  617.85   526.7  618.18   585.4  619.30   614.8  619.61
   644.2  620.41   673.6  622.51   702.9  625.02   761.7  632.00   791.1  634.91
   820.4  637.52
#Mann= 3 , 0 , 0
       0     0.1       0   401.7   0.045       0   416.7     0.1       0
Bank Sta=401.7,416.7
Exp/Cntr=0.3,0.1

Type RM Length L Ch R = 1 ,10819,144.9,150,160.2
XS GIS Cut Line= 3
     2196392.944      636903.132     2196188.846      637290.121
     2196021.969      637658.426
#Sta/Elev= 25
       0  644.44    58.3  639.01    87.5  636.75   116.7  634.28   145.8  630.76
   175.0  626.23   204.2  621.38   233.3  617.92   262.5  616.61   379.2  617.25
   408.3  617.23     430  617.09     445  617.00   466.4  616.88   495.3  617.30
   524.2  618.02   553.0  618.20   581.9  619.49   610.8  622.11   639.7  625.59
   668.6  629.82   697.4  633.72   726.3  636.51   755.2  639.17   841.9  647.81
#Mann= 3 , 0 , 0
       0     0.1       0     430   0.045       0     445     0.1       0
Bank Sta=430,445
Exp/Cntr=0.3,0.1

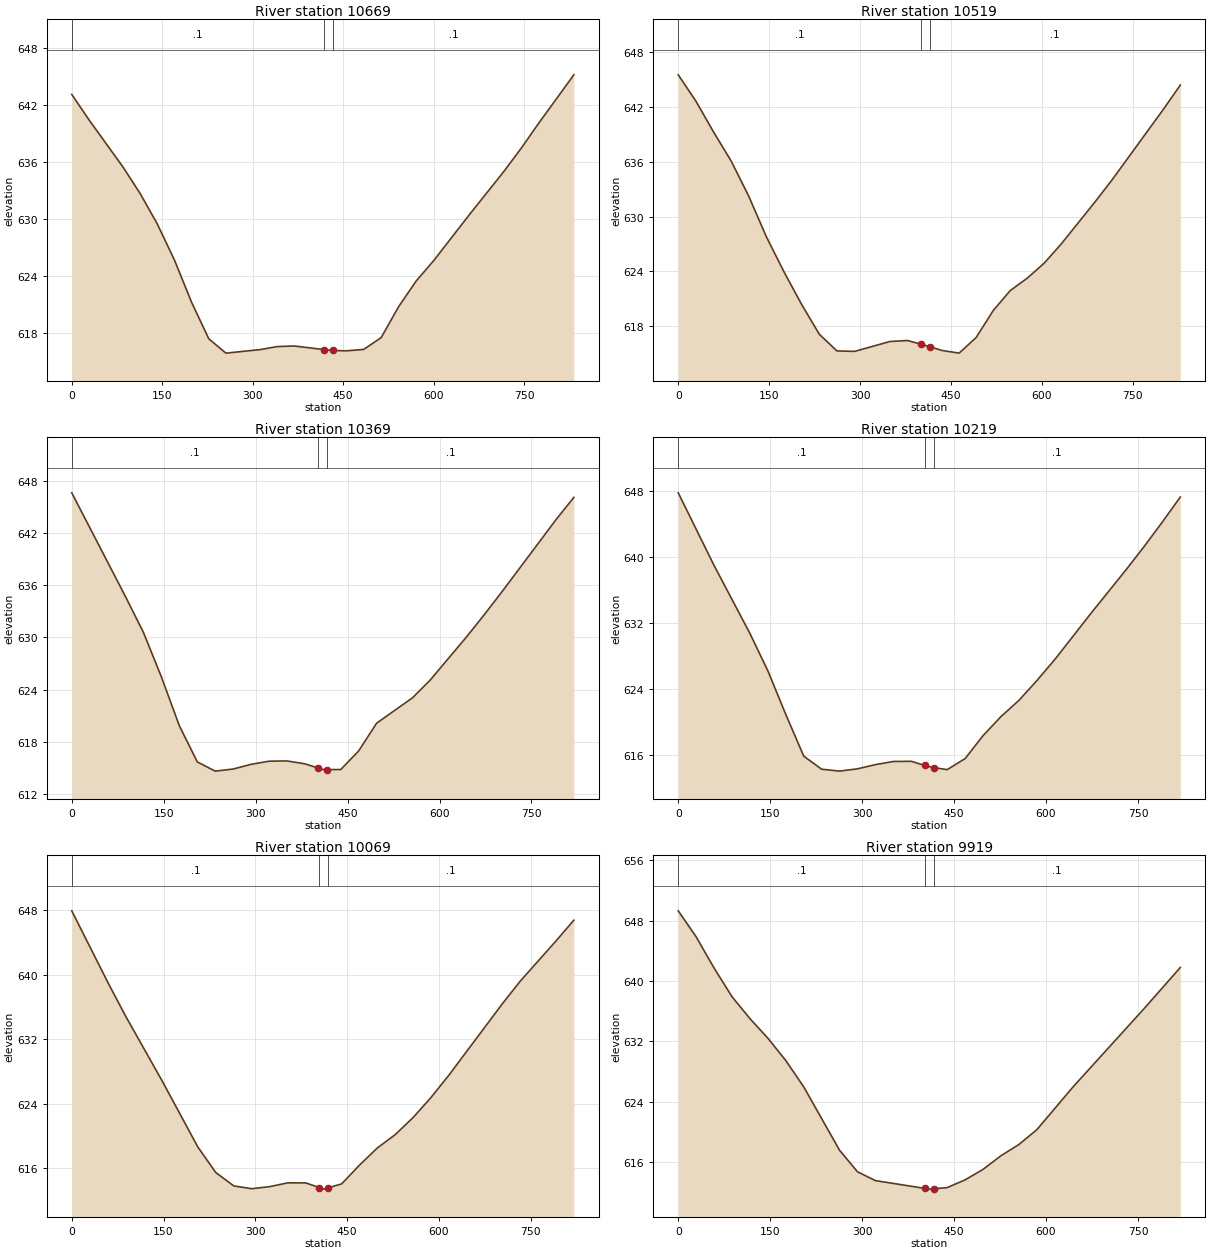
Type RM Length L Ch R = 1 ,10669,152.1,150,145
XS GIS Cut Line= 3
     2196358.454      636876.727     2196075.166      637194.672
     2195762.340      637454.191
#Sta/Elev= 25
       0  643.13    28.4  640.47    85.2  635.47   113.6  632.68   142.0  629.48
   170.3  625.70   198.7  621.26   227.1  617.43   255.5  615.92   312.3  616.29
   340.7  616.61   369.1  616.67   418.3  616.29   433.3  616.20   454.9  616.16
   483.9  616.31   512.9  617.55   542.0  620.82   571.0  623.51   600.0  625.65
   658.1  630.40   716.2  635.02   745.2  637.48   774.2  640.11   832.3  645.19
#Mann= 3 , 0 , 0
       0     0.1       0   418.3   0.045       0   433.3     0.1       0
Bank Sta=418.3,433.3
Exp/Cntr=0.3,0.1

Type RM Length L Ch R = 1 ,10519,153.6,150,146
XS GIS Cut Line= 3
     2196217.669      636750.578     2195980.397      637081.690
     2195722.876      637414.664
#Sta/Elev= 27
       0  645.50    29.1  642.63    58.2  639.26    87.3  636.08   116.4  632.22
   145.5  627.78   174.6  623.94   203.7  620.38   232.8  617.13   261.9  615.31
   291.0  615.26   349.2  616.34   378.2  616.45   399.8  616.06   414.8  615.77
   435.4  615.36   463.5  615.07   491.5  616.78   519.6  619.72   547.7  621.91
   575.7  623.26   603.8  624.91   631.8  627.00   688.0  631.64   716.0  634.04
   800.2  641.71   828.3  644.38
#Mann= 3 , 0 , 0
       0     0.1       0   399.8   0.045       0   414.8     0.1       0
Bank Sta=399.8,414.8
Exp/Cntr=0.3,0.1

Type RM Length L Ch R = 1 ,10369,147.7,150,151.5
XS GIS Cut Line= 3
     2196028.926      636650.177     2195845.682      637016.474
     2195656.171      637379.468
#Sta/Elev= 25
       0  646.60    87.8  634.67   117.0  630.57   146.3  625.46   175.5  619.87
   204.8  615.72   234.0  614.66   263.3  614.90   292.6  615.44   321.8  615.80
   351.1  615.83   380.3  615.50   402.1  615.01   409.6  614.84   417.1  614.84
   438.8  614.84   468.1  616.98   497.3  620.16   555.8  623.07   585.1  625.14
   643.6  630.03   672.8  632.60   702.1  635.27   789.8  643.50   819.1  646.08
#Mann= 3 , 0 , 0
       0     0.1       0   402.1   0.045       0   417.1     0.1       0
Bank Sta=402.1,417.1
Exp/Cntr=0.3,0.1

Type RM Length L Ch R = 1 ,10219,146.1,150,154.5
XS GIS Cut Line= 3
     2195934.312      636596.150     2195715.430      636942.232
     2195501.700      637291.596
#Sta/Elev= 26
       0  647.79    58.5  638.98   117.0  630.74   146.2  626.22   175.5  620.92
   204.8  615.87   234.0  614.29   263.2  614.06   292.5  614.34   321.7  614.85
   351.0  615.23   380.2  615.25     402  614.75     417  614.49   438.7  614.24
   468.0  615.58   497.2  618.36   526.5  620.67   555.8  622.64   585.0  625.03
   614.3  627.59   672.8  633.14   731.3  638.54   760.5  641.33   789.8  644.26
   819.0  647.28
#Mann= 3 , 0 , 0
       0     0.1       0     402   0.045       0     417     0.1       0
Bank Sta=402,417
Exp/Cntr=0.3,0.1

Type RM Length L Ch R = 1 ,10069,146.6,150,152.7
XS GIS Cut Line= 3
     2195866.937      636552.784     2195591.141      636858.882
     2195311.671      637157.269
#Sta/Elev= 25
       0  647.93    58.9  639.06    88.3  634.83   147.2  626.91   206.0  618.65
   235.4  615.47   264.9  613.81   294.3  613.46   323.7  613.72   353.2  614.19
   382.6  614.18   404.5  613.61   412.0  613.41   419.5  613.58   441.2  614.06
   470.4  616.39   499.6  618.52   528.8  620.17   558.0  622.29   587.2  624.77
   616.4  627.53   704.0  636.41   733.2  639.21   791.6  644.19   820.8  646.77
#Mann= 3 , 0 , 0
       0     0.1       0   404.5   0.045       0   419.5     0.1       0
Bank Sta=404.5,419.5
Exp/Cntr=0.3,0.1

Type RM Length L Ch R = 1 ,9919,156.6,150,144.2
XS GIS Cut Line= 3
     2195810.456      636486.249     2195493.303      636745.279
     2195180.045      637009.108
#Sta/Elev= 23
       0  649.31    29.2  645.87    58.5  641.72    87.8  637.92   117.0  635.02
   146.2  632.43   175.5  629.46   204.8  625.96   263.2  617.57   292.5  614.71
   321.7  613.55     402  612.52   409.5  612.42     417  612.47   438.7  612.62
   468.0  613.65   497.2  615.04   526.5  616.85   555.8  618.34   585.0  620.30
   643.5  625.92   760.5  636.40   819.0  641.80
#Mann= 3 , 0 , 0
       0     0.1       0     402   0.045       0     417     0.1       0
Bank Sta=402,417
Exp/Cntr=0.3,0.1