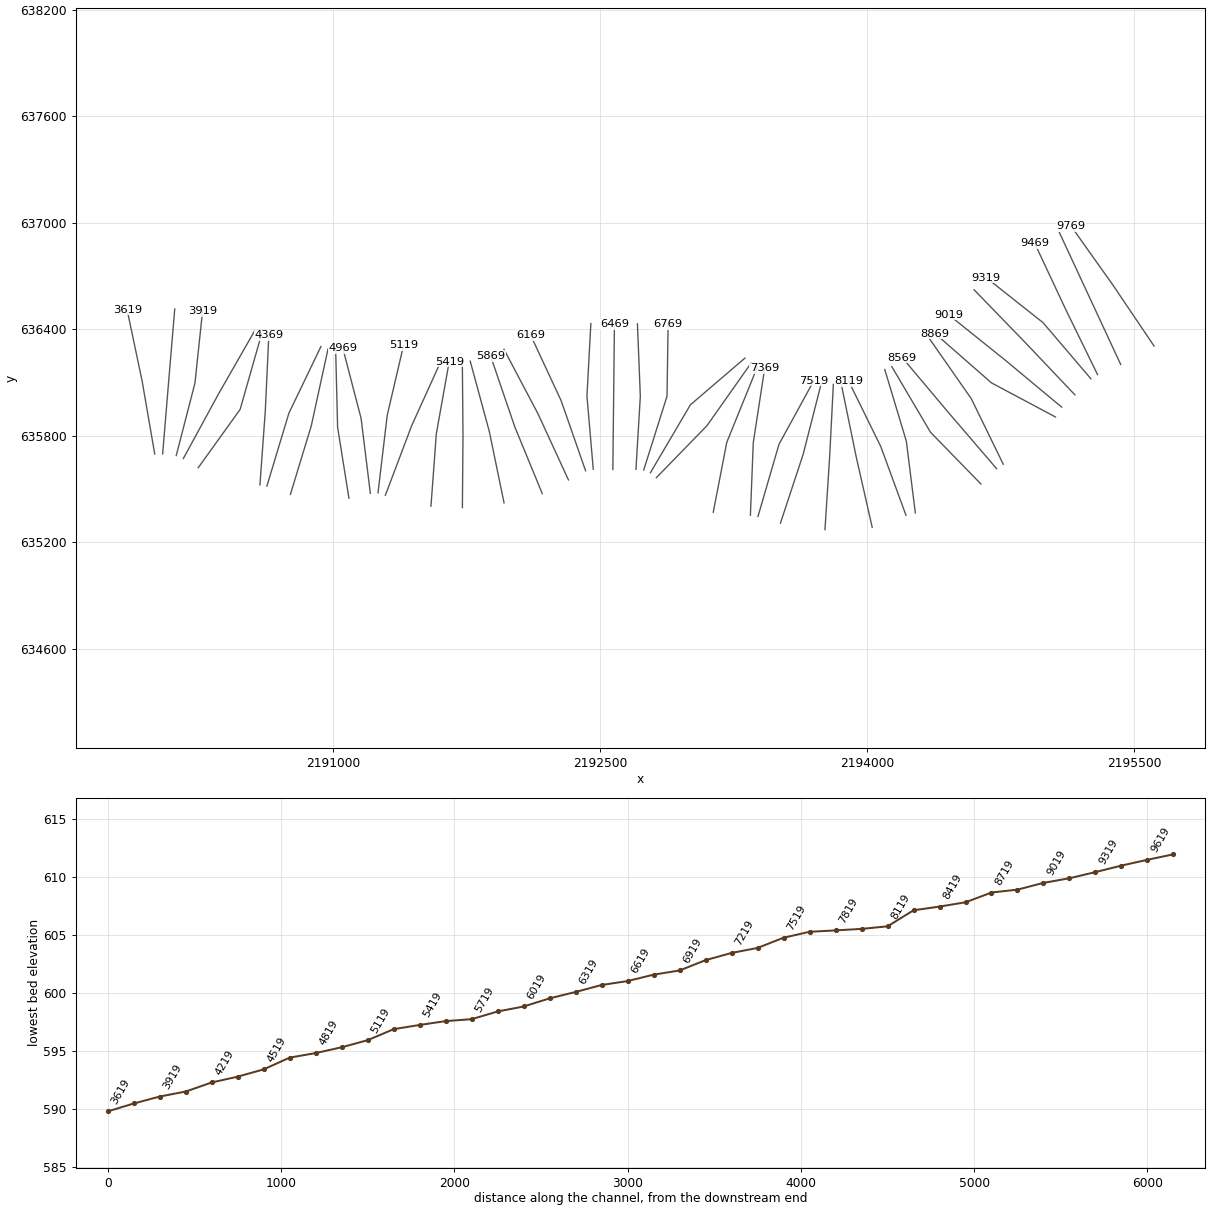
HEC-RAS study LFRFBUCKRV.prj: LFRFBUCKRV

--- LFRFBUCKRV.g01 (geometry) --- (continued)

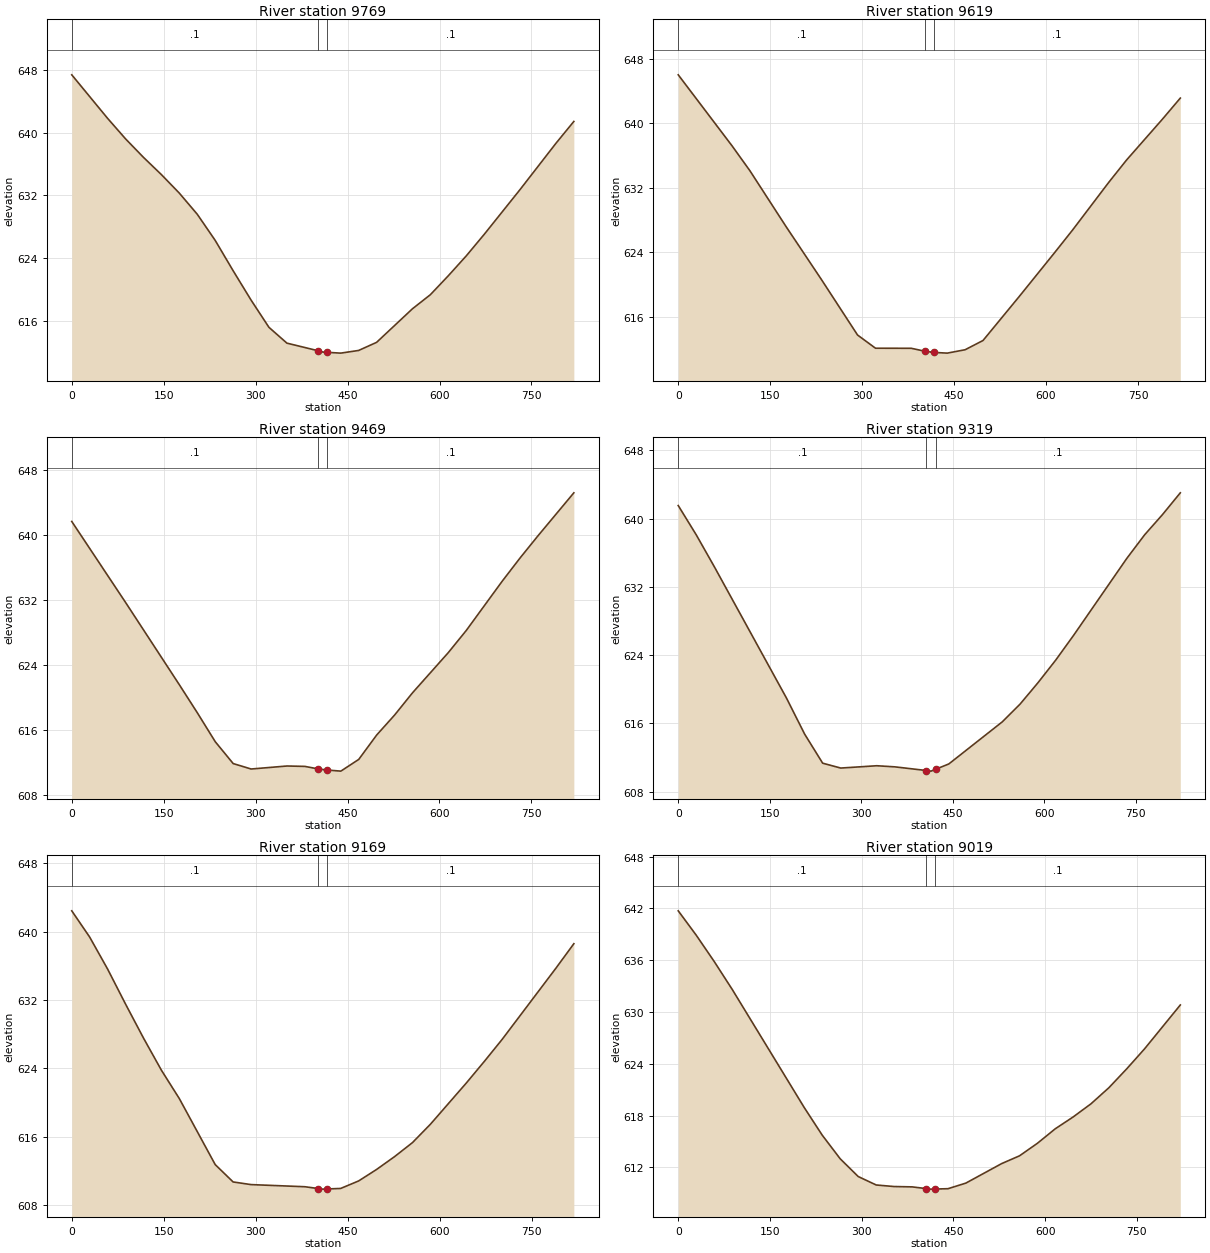
Type RM Length L Ch R = 1 ,9769,153.6,150,145.9
XS GIS Cut Line= 3
     2195612.429      636304.789     2195383.892      636644.555
     2195147.215      636978.905
#Sta/Elev= 26
       0  647.34    58.5  641.80    87.7  639.20   117.0  636.84   146.2  634.65
   175.5  632.29   204.7  629.61   234.0  626.28   263.2  622.43   292.5  618.69
   321.7  615.22   351.0  613.21     402  612.24   409.5  612.08     417  612.04
   438.7  611.94   468.0  612.28   497.3  613.31   555.8  617.58   585.0  619.37
   614.3  621.78   643.6  624.31   672.8  627.04   731.3  632.74   789.9  638.63
   819.1  641.41
#Mann= 3 , 0 , 0
       0     0.1       0     402   0.045       0     417     0.1       0
Bank Sta=402,417
Exp/Cntr=0.3,0.1

Type RM Length L Ch R = 1 ,9619,149.5,150,150
XS GIS Cut Line= 3
     2195424.992      636200.975     2195252.841      636572.532
     2195080.690      636944.088
#Sta/Elev= 20
       0  646.03    87.8  637.21   117.0  634.11   175.5  627.23   234.0  620.56
   292.5  613.72   321.8  612.08   380.2  612.07     402  611.71     417  611.56
   438.8  611.47   468.0  611.89   497.2  613.04   555.8  618.46   614.2  623.97
   643.5  626.78   702.0  632.65   731.2  635.44   789.8  640.52   819.0  643.14
#Mann= 3 , 0 , 0
       0     0.1       0     402   0.045       0     417     0.1       0
Bank Sta=402,417
Exp/Cntr=0.3,0.1

Type RM Length L Ch R = 1 ,9469,144.3,150,160.6
XS GIS Cut Line= 3
     2195294.879      636144.039     2195115.423      636512.471
     2194941.991      636883.371
#Sta/Elev= 22
       0  641.65    87.8  631.70   175.6  621.58   204.9  618.14   234.2  614.58
   263.4  611.90   292.7  611.23   351.3  611.60   380.5  611.55   402.3  611.24
   417.3  611.10   439.1  610.97   468.3  612.41   497.6  615.41   526.8  617.86
   556.0  620.59   614.5  625.54   643.8  628.26   702.3  634.30   731.5  637.16
   760.8  639.89   819.3  645.17
#Mann= 3 , 0 , 0
       0     0.1       0   402.3   0.045       0   417.3     0.1       0
Bank Sta=402.3,417.3
Exp/Cntr=0.3,0.1

Type RM Length L Ch R = 1 ,9319,148.7,150,147.1
XS GIS Cut Line= 3
     2195257.508      636120.584     2194989.044      636436.348
     2194669.118      636690.555
#Sta/Elev= 22
       0  641.52    29.6  638.08    59.2  634.35   177.6  618.95   207.2  614.75
   236.8  611.34   266.4  610.77   325.6  611.04   355.2  610.91     407  610.48
   414.5  610.41     422  610.63   443.6  611.25   531.2  616.18   560.4  618.26
   589.6  620.75   618.8  623.41   648.0  626.30   735.5  635.34   764.7  638.10
   793.9  640.46   823.1  643.01
#Mann= 3 , 0 , 0
       0     0.1       0     407   0.045       0     422     0.1       0
Bank Sta=407,422
Exp/Cntr=0.3,0.1

Type RM Length L Ch R = 1 ,9169,147.4,150,152.8
XS GIS Cut Line= 3
     2195167.635      636030.030     2194886.186      636327.386
     2194601.410      636621.813
#Sta/Elev= 25
       0  642.45    29.2  639.38    58.5  635.63    87.7  631.54   117.0  627.56
   146.2  623.80   175.5  620.47   234.0  612.75   263.2  610.72   292.4  610.41
   380.2  610.16   401.9  609.95   409.4  609.88   416.9  609.90   438.7  609.96
   468.0  610.84   497.2  612.18   526.5  613.68   555.7  615.32   585.0  617.47
   643.5  622.29   672.8  624.81   702.0  627.40   789.8  635.74   819.0  638.60
#Mann= 3 , 0 , 0
       0     0.1       0   401.9   0.045       0   416.9     0.1       0
Bank Sta=401.9,416.9
Exp/Cntr=0.3,0.1

Type RM Length L Ch R = 1 ,9019,145.4,150,148.8
XS GIS Cut Line= 3
     2195093.324      635960.874     2194777.021      636224.850
     2194458.262      636481.217
#Sta/Elev= 26
       0  641.73    29.4  638.91    58.8  635.86    88.3  632.62   206.0  618.94
   235.4  615.74   264.8  613.00   294.3  610.94   323.7  609.96   353.1  609.78
   382.6  609.74   404.5  609.55   412.0  609.48   419.5  609.49   441.2  609.53
   470.4  610.18   528.9  612.44   558.1  613.34   587.3  614.79   616.5  616.47
   645.7  617.84   675.0  619.37   704.2  621.23   733.4  623.42   762.6  625.74
   821.0  630.82
#Mann= 3 , 0 , 0
       0     0.1       0   404.5   0.045       0   419.5     0.1       0
Bank Sta=404.5,419.5
Exp/Cntr=0.3,0.1

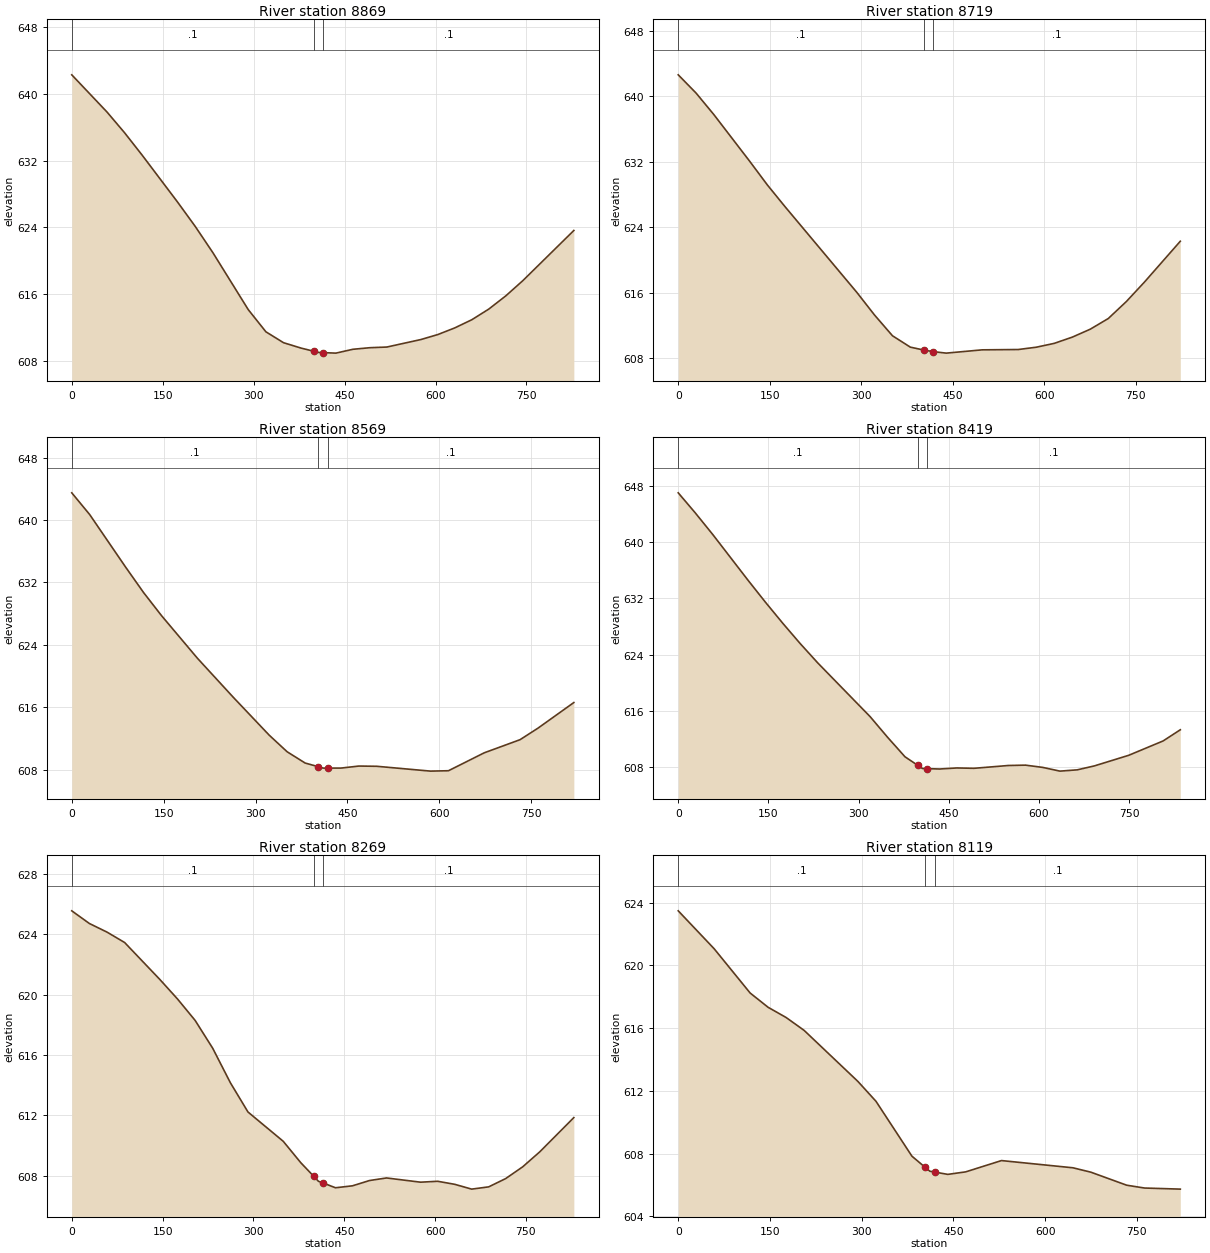
Type RM Length L Ch R = 1 ,8869,164.3,150,144.7
XS GIS Cut Line= 3
     2195058.467      635905.372     2194699.073      636097.472
     2194382.992      636374.962
#Sta/Elev= 26
       0  642.30    58.2  637.83    87.3  635.33   116.4  632.63   174.6  627.02
   203.8  624.09   232.9  620.94   291.1  614.12   320.2  611.46   349.3  610.15
   378.4  609.50     400  609.11   407.5  608.98     415  608.96   435.6  608.90
   463.6  609.36   491.6  609.55   519.7  609.63   575.8  610.53   603.8  611.13
   631.8  611.93   659.9  612.91   687.9  614.19   716.0  615.78   744.0  617.60
   828.1  623.62
#Mann= 3 , 0 , 0
       0     0.1       0     400   0.045       0     415     0.1       0
Bank Sta=400,415
Exp/Cntr=0.3,0.1

Type RM Length L Ch R = 1 ,8719,144.2,150,152
XS GIS Cut Line= 3
     2194765.286      635639.153     2194586.115      636007.649
     2194350.268      636347.170
#Sta/Elev= 23
       0  642.60    29.3  640.37    58.5  637.74   117.1  632.06   146.3  629.15
   175.6  626.47   292.7  616.07   321.9  613.29   351.2  610.77   380.5  609.38
   402.2  609.03   417.2  608.84   439.3  608.65   498.3  609.05   557.4  609.09
   586.9  609.37   616.4  609.84   646.0  610.60   675.5  611.57   705.0  612.87
   734.6  614.94   764.1  617.30   823.1  622.30
#Mann= 3 , 0 , 0
       0     0.1       0   402.2   0.045       0   417.2     0.1       0
Bank Sta=402.2,417.2
Exp/Cntr=0.3,0.1

Type RM Length L Ch R = 1 ,8569,148.6,150,146.2
XS GIS Cut Line= 3
     2194728.224      635613.953     2194461.510      635925.600
     2194198.397      636239.226
#Sta/Elev= 22
       0  643.48    29.3  640.69    87.9  633.96   117.2  630.70   146.5  627.74
   205.1  622.28   263.7  617.27   322.3  612.42   351.6  610.29   380.9  608.85
   402.7  608.37   410.2  608.20   417.7  608.20   439.4  608.20   468.7  608.46
   497.9  608.43   585.6  607.81   614.9  607.86   673.4  610.16   731.8  611.84
   761.1  613.32   819.6  616.60
#Mann= 3 , 0 , 0
       0     0.1       0   402.7   0.045       0   417.7     0.1       0
Bank Sta=402.7,417.7
Exp/Cntr=0.3,0.1

Type RM Length L Ch R = 1 ,8419,164.7,150,144.6
XS GIS Cut Line= 3
     2194639.814      635527.819     2194356.875      635819.098
     2194139.433      636188.792
#Sta/Elev= 26
       0  647.01    29.0  644.09    58.0  641.02   116.0  634.59   145.0  631.46
   174.0  628.45   203.0  625.56   232.0  622.83   319.1  615.19   348.1  612.26
   377.1  609.48   398.6  608.25   406.1  607.82   413.6  607.80   434.7  607.74
   463.3  607.89   491.9  607.84   549.0  608.24   577.6  608.29   606.2  607.97
   634.8  607.44   663.4  607.62   692.0  608.18   749.2  609.69   806.4  611.73
   835.0  613.32
#Mann= 3 , 0 , 0
       0     0.1       0   398.6   0.045       0   413.6     0.1       0
Bank Sta=398.6,413.6
Exp/Cntr=0.3,0.1

Type RM Length L Ch R = 1 ,8269,144.9,150,153.7
XS GIS Cut Line= 3
     2194271.500      635364.731     2194221.036      635768.936
     2194099.797      636172.859
#Sta/Elev= 28
       0  625.56    29.1  624.72    58.2  624.15    87.3  623.46   145.5  621.01
   174.6  619.72   203.7  618.30   232.8  616.45   261.9  614.17   291.0  612.23
   349.2  610.29   378.2  608.87   399.8  607.96   407.3  607.64   414.8  607.53
   435.5  607.21   463.6  607.34   491.7  607.69   519.8  607.86   576.0  607.58
   604.2  607.64   632.3  607.44   660.4  607.12   688.5  607.27   716.6  607.82
   744.7  608.60   772.8  609.59   829.1  611.86
#Mann= 3 , 0 , 0
       0     0.1       0   399.8   0.045       0   414.8     0.1       0
Bank Sta=399.8,414.8
Exp/Cntr=0.3,0.1

Type RM Length L Ch R = 1 ,8119,152.9,150,144.3
XS GIS Cut Line= 3
     2194218.891      635351.873     2194077.566      635738.345
     2193897.494      636105.995
#Sta/Elev= 20
       0  623.48    58.8  621.06   117.6  618.24   147.0  617.33   176.4  616.68
   205.8  615.86   293.9  612.60   323.3  611.34   382.1  607.84     404  607.12
   411.5  606.88     419  606.83   440.7  606.68   470.0  606.84   528.5  607.56
   645.4  607.10   674.7  606.82   733.2  605.99   762.4  605.81   820.9  605.74
#Mann= 3 , 0 , 0
       0     0.1       0     404   0.045       0     419     0.1       0
Bank Sta=404,419
Exp/Cntr=0.3,0.1

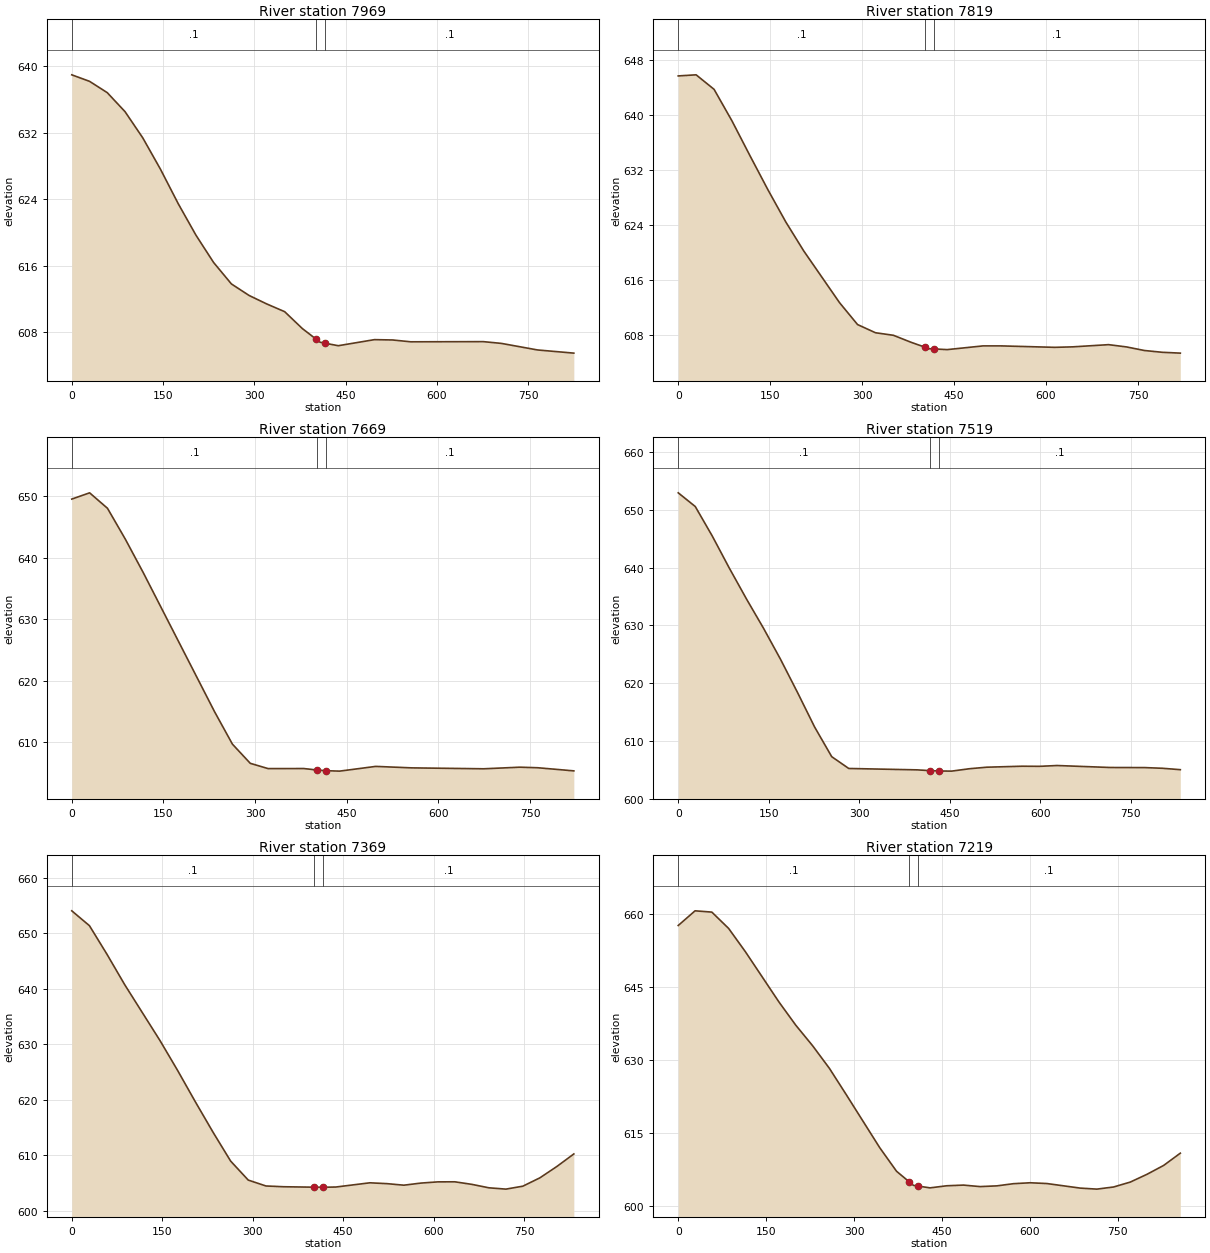
Type RM Length L Ch R = 1 ,7969,156.5,150,144.3
XS GIS Cut Line= 3
     2194029.198      635284.060     2193939.097      635682.164
     2193855.547      636090.726
#Sta/Elev= 25
       0  638.95    29.2  638.17    58.3  636.81    87.5  634.53   116.6  631.39
   145.8  627.61   174.9  623.48   204.1  619.69   233.2  616.40   262.4  613.83
   291.6  612.44   320.7  611.42   349.9  610.50   379.0  608.47   400.7  607.25
   408.2  606.83   415.7  606.72   438.0  606.41   497.5  607.14   527.3  607.10
   557.1  606.88   676.3  606.90   706.0  606.69   765.6  605.90   825.2  605.52
#Mann= 3 , 0 , 0
       0     0.1       0   400.7   0.045       0   415.7     0.1       0
Bank Sta=400.7,415.7
Exp/Cntr=0.3,0.1

Type RM Length L Ch R = 1 ,7819,155.7,150,145.5
XS GIS Cut Line= 3
     2193763.939      635271.035     2193790.152      635679.688
     2193811.130      636088.691
#Sta/Elev= 26
       0  645.64    29.2  645.80    58.5  643.69    87.8  639.09   117.0  634.06
   146.2  629.13   175.5  624.43   204.8  620.22   263.2  612.71   292.5  609.54
   321.7  608.35   351.0  607.98   380.2  606.95     402  606.27   409.5  606.03
     417  606.00   438.8  605.90   497.2  606.44   526.5  606.44   614.3  606.23
   643.5  606.30   702.0  606.62   731.3  606.29   760.5  605.77   789.8  605.51
   819.0  605.39
#Mann= 3 , 0 , 0
       0     0.1       0     402   0.045       0     417     0.1       0
Bank Sta=402,417
Exp/Cntr=0.3,0.1

Type RM Length L Ch R = 1 ,7669,149.2,150,144.1
XS GIS Cut Line= 3
     2193513.952      635307.097     2193641.676      635695.584
     2193743.435      636095.484
#Sta/Elev= 19
       0  649.53    29.2  650.55    58.4  648.04    87.6  643.02   116.8  637.60
   233.7  614.93   262.9  609.66   292.1  606.54   321.3  605.68   379.7  605.69
   401.4  605.45   416.4  605.34   438.4  605.27   497.4  606.04   556.3  605.80
   674.2  605.65   733.2  605.91   762.6  605.82   821.6  605.31
#Mann= 3 , 0 , 0
       0     0.1       0   401.4   0.045       0   416.4     0.1       0
Bank Sta=401.4,416.4
Exp/Cntr=0.3,0.1

Type RM Length L Ch R = 1 ,7519,144.5,150,157.9
XS GIS Cut Line= 3
     2193387.689      635344.566     2193505.773      635751.563
     2193701.396      636109.670
#Sta/Elev= 24
       0  652.95    28.2  650.58    56.5  645.45    84.8  639.88   113.0  634.58
   141.3  629.50   169.5  624.12   197.8  618.34   226.0  612.39   254.3  607.26
   282.5  605.22   395.5  604.98   416.3  604.85   431.3  604.79   452.9  604.76
   482.1  605.17   511.2  605.44   569.5  605.61   598.7  605.59   627.8  605.73
   715.2  605.39   773.5  605.37   802.7  605.25   831.8  605.01
#Mann= 3 , 0 , 0
       0     0.1       0   416.3   0.045       0   431.3     0.1       0
Bank Sta=416.3,431.3
Exp/Cntr=0.3,0.1

Type RM Length L Ch R = 1 ,7369,153.4,150,144.6
XS GIS Cut Line= 3
     2193345.104      635351.604     2193361.372      635760.965
     2193425.309      636178.814
#Sta/Elev= 28
       0  654.09    29.3  651.41    58.5  646.23    87.8  640.76   146.3  630.68
   175.6  625.27   204.8  619.65   234.1  614.17   263.4  608.94   292.6  605.51
   321.9  604.45   351.2  604.31   402.2  604.23   417.2  604.22   437.9  604.26
   494.2  605.02   522.4  604.87   550.6  604.59   578.8  604.97   607.0  605.19
   635.1  605.20   663.3  604.74   691.5  604.12   719.7  603.88   747.8  604.41
   776.0  605.91   804.2  607.96   832.4  610.23
#Mann= 3 , 0 , 0
       0     0.1       0   402.2   0.045       0   417.2     0.1       0
Bank Sta=402.2,417.2
Exp/Cntr=0.3,0.1

Type RM Length L Ch R = 1 ,7219,163.5,150,144.7
XS GIS Cut Line= 3
     2193136.445      635368.397     2193212.484      635762.478
     2193383.404      636184.890
#Sta/Elev= 30
       0  657.72    28.7  660.74    57.3  660.48    86.0  657.12   114.7  652.31
   172.0  641.96   200.7  637.19   229.3  632.98   258.0  628.32   286.7  622.92
   344.0  611.97   372.7  607.12   393.8  605.00   401.4  604.23   408.8  604.09
   429.8  603.71   458.3  604.14   486.8  604.28   515.3  603.97   543.8  604.12
   572.2  604.57   600.7  604.76   629.2  604.60   686.2  603.66   714.6  603.45
   743.1  603.89   771.6  604.90   800.1  606.50   828.6  608.33   857.0  610.85
#Mann= 3 , 0 , 0
       0     0.1       0   393.8   0.045       0   408.8     0.1       0
Bank Sta=393.8,408.8
Exp/Cntr=0.3,0.1

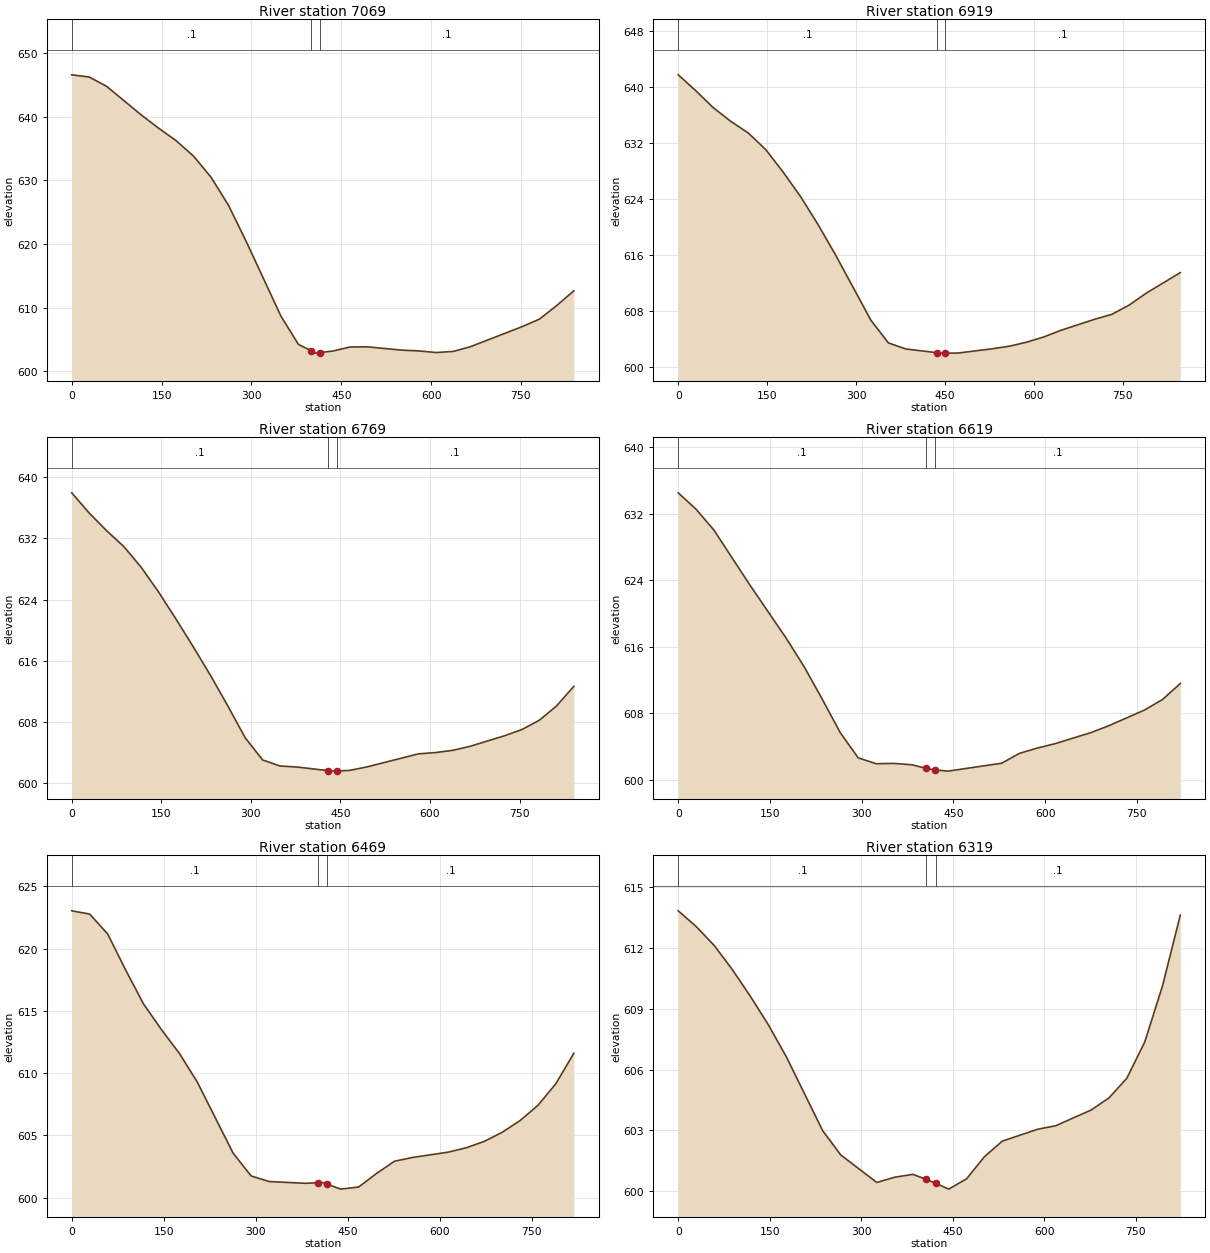
Type RM Length L Ch R = 1 ,7069,144,150,144.2
XS GIS Cut Line= 3
     2192817.051      635563.609     2193100.870      635855.864
     2193348.893      636208.236
#Sta/Elev= 27
       0  646.62    29.1  646.28    58.2  644.81   116.4  640.28   145.5  638.20
   174.6  636.23   203.7  633.79   232.8  630.48   261.9  626.05   291.0  620.45
   349.2  608.66   378.3  604.22   399.9  603.19   407.4  602.83   414.9  602.92
   436.1  603.16   464.8  603.80   493.6  603.82   551.0  603.30   579.8  603.18
   608.5  602.92   637.2  603.10   665.9  603.85   752.1  607.00   780.8  608.18
   809.6  610.31   838.3  612.63
#Mann= 3 , 0 , 0
       0     0.1       0   399.9   0.045       0   414.9     0.1       0
Bank Sta=399.9,414.9
Exp/Cntr=0.3,0.1

Type RM Length L Ch R = 1 ,6919,144.7,150,170
XS GIS Cut Line= 3
     2192783.763      635591.342     2193008.038      635973.683
     2193314.543      636236.859
#Sta/Elev= 27
       0  641.74    29.6  639.47    59.1  637.04    88.6  635.09   118.2  633.42
   147.8  631.04   177.3  627.80   206.9  624.27   236.4  620.26   266.0  615.90
   325.1  606.65   354.6  603.40   384.2  602.53   435.8  602.01   443.3  601.94
   450.8  601.94   472.1  601.95   529.8  602.56   558.7  602.93   587.6  603.50
   616.4  604.24   645.3  605.19   703.0  606.79   731.8  607.49   760.7  608.80
   789.5  610.50   847.2  613.46
#Mann= 3 , 0 , 0
       0     0.1       0   435.8   0.045       0   450.8     0.1       0
Bank Sta=435.8,450.8
Exp/Cntr=0.3,0.1

Type RM Length L Ch R = 1 ,6769,144.3,150,151.2
XS GIS Cut Line= 3
     2192746.004      635606.599     2192876.914      636022.455
     2192882.948      636427.238
#Sta/Elev= 28
       0  637.95    29.1  635.32    58.1  633.02    87.2  630.93   116.3  628.22
   145.3  625.00   174.4  621.47   203.5  617.83   232.5  614.07   261.6  610.06
   290.6  605.92   319.7  603.04   348.8  602.25   377.8  602.11   428.5  601.65
   436.0  601.58   443.5  601.60   464.9  601.67   493.8  602.12   580.6  603.84
   609.5  604.01   638.4  604.30   667.3  604.83   725.1  606.21   754.0  607.02
   783.0  608.23   811.9  610.10   840.8  612.66
#Mann= 3 , 0 , 0
       0     0.1       0   428.5   0.045       0   443.5     0.1       0
Bank Sta=428.5,443.5
Exp/Cntr=0.3,0.1

Type RM Length L Ch R = 1 ,6619,148.9,150,148.9
XS GIS Cut Line= 3
     2192702.397      635610.365     2192726.970      636021.608
     2192710.643      636430.345
#Sta/Elev= 24
       0  634.54    29.4  632.55    58.8  630.01   117.7  623.38   176.6  617.03
   206.0  613.59   235.4  609.71   264.8  605.68   294.3  602.63   323.7  601.92
   353.1  601.96   382.6  601.79   404.5  601.37   419.5  601.18   441.2  601.03
   528.8  601.98   558.1  603.17   587.3  603.81   616.5  604.34   675.0  605.67
   704.2  606.50   762.6  608.39   791.8  609.65   821.0  611.58
#Mann= 3 , 0 , 0
       0     0.1       0   404.5   0.045       0   419.5     0.1       0
Bank Sta=404.5,419.5
Exp/Cntr=0.3,0.1

Type RM Length L Ch R = 1 ,6469,147.8,150,149
XS GIS Cut Line= 3
     2192572.605      635609.480     2192577.041      636018.956
     2192581.476      636428.432
#Sta/Elev= 28
       0  623.03    29.2  622.77    58.5  621.18    87.8  618.29   117.0  615.56
   146.2  613.50   175.5  611.59   204.8  609.28   263.2  603.58   292.5  601.75
   321.8  601.30   380.2  601.16     402  601.20   409.5  601.22     417  601.08
   438.8  600.69   468.0  600.86   497.2  601.95   526.5  602.93   555.8  603.23
   614.2  603.66   643.5  604.01   672.8  604.52   702.0  605.25   731.2  606.19
   760.5  607.42   789.8  609.16   819.0  611.60
#Mann= 3 , 0 , 0
       0     0.1       0     402   0.045       0     417     0.1       0
Bank Sta=402,417
Exp/Cntr=0.3,0.1

Type RM Length L Ch R = 1 ,6319,144.3,150,160.9
XS GIS Cut Line= 3
     2192462.524      635610.787     2192427.143      636023.485
     2192449.087      636431.564
#Sta/Elev= 26
       0  613.84    29.6  613.06    59.2  612.12    88.8  610.93   118.4  609.61
   147.9  608.20   177.5  606.61   236.7  602.98   266.3  601.78   325.4  600.42
   355.0  600.68   384.6  600.82   406.7  600.57   421.7  600.38   443.4  600.09
   472.6  600.60   501.8  601.69   531.0  602.46   589.4  603.05   618.6  603.22
   676.9  604.00   706.1  604.60   735.3  605.57   764.5  607.35   793.7  610.13
   822.9  613.63
#Mann= 3 , 0 , 0
       0     0.1       0   406.7   0.045       0   421.7     0.1       0
Bank Sta=406.7,421.7
Exp/Cntr=0.3,0.1

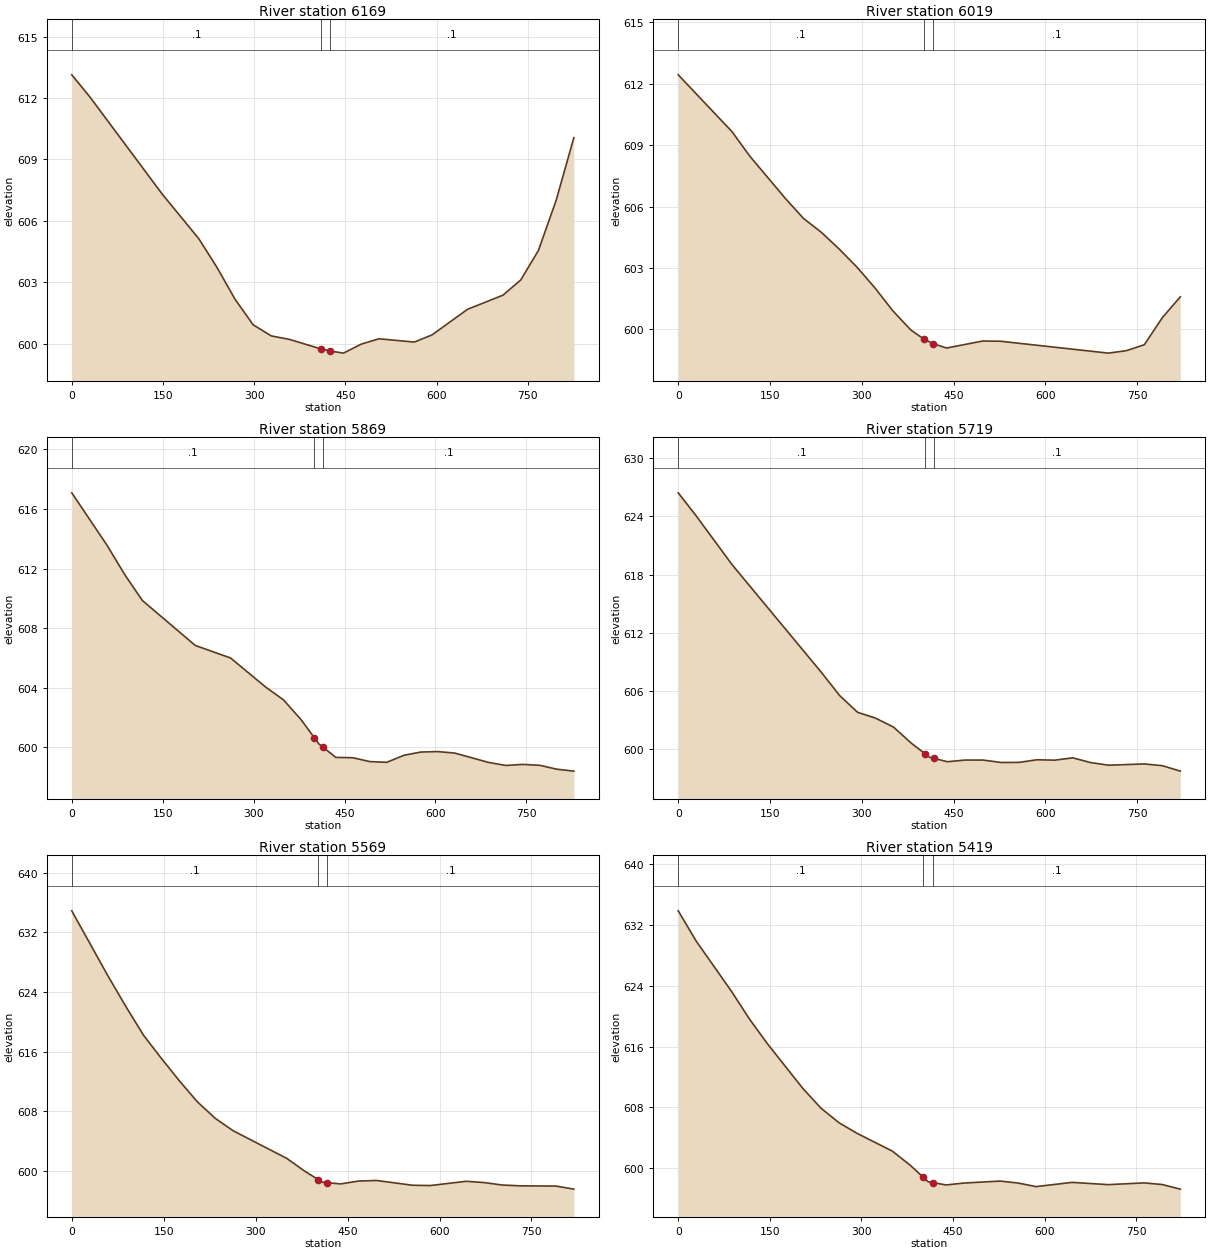
Type RM Length L Ch R = 1 ,6169,147.7,150,151
XS GIS Cut Line= 3
     2192419.453      635602.258     2192282.190      635996.950
     2192110.476      636367.079
#Sta/Elev= 22
       0  613.13    29.8  612.05   149.2  607.29   208.9  605.13   238.8  603.73
   268.6  602.17   298.5  600.92   328.3  600.38   358.2  600.21   410.4  599.74
   425.4  599.64   447.0  599.54   476.2  599.98   505.3  600.24   563.6  600.08
   592.7  600.43   651.0  601.68   709.3  602.37   738.5  603.11   767.6  604.55
   796.8  607.00   825.9  610.06
#Mann= 3 , 0 , 0
       0     0.1       0   410.4   0.045       0   425.4     0.1       0
Bank Sta=410.4,425.4
Exp/Cntr=0.3,0.1

Type RM Length L Ch R = 1 ,6019,150.6,150,146.2
XS GIS Cut Line= 3
     2192323.231      635550.672     2192152.498      635922.581
     2191961.024      636286.298
#Sta/Elev= 21
       0  612.43    87.7  609.66   116.9  608.46   175.4  606.38   204.6  605.42
   233.8  604.74   263.1  603.92   292.3  603.03   321.5  602.02   350.8  600.90
   380.0  599.97   401.7  599.52   416.7  599.30   438.6  599.09   497.3  599.43
   526.7  599.42   702.8  598.84   732.2  598.96   761.5  599.25   790.9  600.57
   820.3  601.59
#Mann= 3 , 0 , 0
       0     0.1       0   401.7   0.045       0   416.7     0.1       0
Bank Sta=401.7,416.7
Exp/Cntr=0.3,0.1

Type RM Length L Ch R = 1 ,5869,153.5,150,148.1
XS GIS Cut Line= 3
     2192176.242      635473.375     2192021.567      635850.394
     2191885.913      636248.680
#Sta/Elev= 26
       0  617.08    58.2  613.56    87.3  611.60   116.4  609.86   203.8  606.84
   262.0  606.00   320.2  604.04   349.3  603.19   378.4  601.86     400  600.66
   407.5  600.24     415  600.00   435.6  599.33   463.6  599.31   491.7  599.05
   519.7  599.00   547.8  599.47   575.8  599.69   603.9  599.72   631.9  599.62
   688.0  598.99   716.1  598.79   744.1  598.86   772.2  598.80   800.2  598.54
   828.3  598.41
#Mann= 3 , 0 , 0
       0     0.1       0     400   0.045       0     415     0.1       0
Bank Sta=400,415
Exp/Cntr=0.3,0.1

Type RM Length L Ch R = 1 ,5719,154.7,150,144.2
XS GIS Cut Line= 3
     2191961.487      635421.400     2191878.738      635823.464
     2191771.590      636219.463
#Sta/Elev= 25
       0  626.42    29.3  624.05    88.0  619.02   234.6  607.88   263.9  605.53
   293.2  603.81   322.5  603.21   351.8  602.29   381.2  600.62     403  599.56
   410.5  599.19     418  599.07   439.8  598.72   469.1  598.89   498.4  598.89
   527.7  598.64   557.0  598.65   586.3  598.92   615.6  598.88   644.9  599.12
   674.2  598.63   703.5  598.36   762.1  598.49   791.4  598.31   820.7  597.75
#Mann= 3 , 0 , 0
       0     0.1       0     403   0.045       0     418     0.1       0
Bank Sta=403,418
Exp/Cntr=0.3,0.1

Type RM Length L Ch R = 1 ,5569,151.4,150,145.7
XS GIS Cut Line= 3
     2191727.511      635394.479     2191730.951      635803.907
     2191727.244      636213.685
#Sta/Elev= 25
       0  634.87    58.5  626.23    87.7  622.13   117.0  618.21   146.2  615.10
   175.5  612.10   204.7  609.30   234.0  607.07   263.2  605.41   351.0  601.69
   380.2  599.98   401.9  598.87   409.4  598.49   416.9  598.44   438.7  598.28
   468.0  598.66   497.3  598.74   555.8  598.10   585.1  598.06   643.6  598.63
   672.9  598.46   702.2  598.13   731.4  598.02   790.0  597.99   819.2  597.58
#Mann= 3 , 0 , 0
       0     0.1       0   401.9   0.045       0   416.9     0.1       0
Bank Sta=401.9,416.9
Exp/Cntr=0.3,0.1

Type RM Length L Ch R = 1 ,5419,156.1,150,144.2
XS GIS Cut Line= 3
     2191551.005      635403.056     2191581.171      635810.817
     2191653.564      636217.465
#Sta/Elev= 24
       0  633.87    29.2  629.91    87.6  623.23   116.8  619.61   146.0  616.38
   204.4  610.46   233.6  607.91   262.8  606.01   292.0  604.62   350.5  602.25
   379.7  600.40   401.4  598.79   408.9  598.23   416.4  598.12   438.4  597.80
   467.9  598.05   526.9  598.31   556.4  598.05   585.9  597.58   644.9  598.14
   703.9  597.84   762.9  598.07   792.4  597.85   821.9  597.25
#Mann= 3 , 0 , 0
       0     0.1       0   401.4   0.045       0   416.4     0.1       0
Bank Sta=401.4,416.4
Exp/Cntr=0.3,0.1

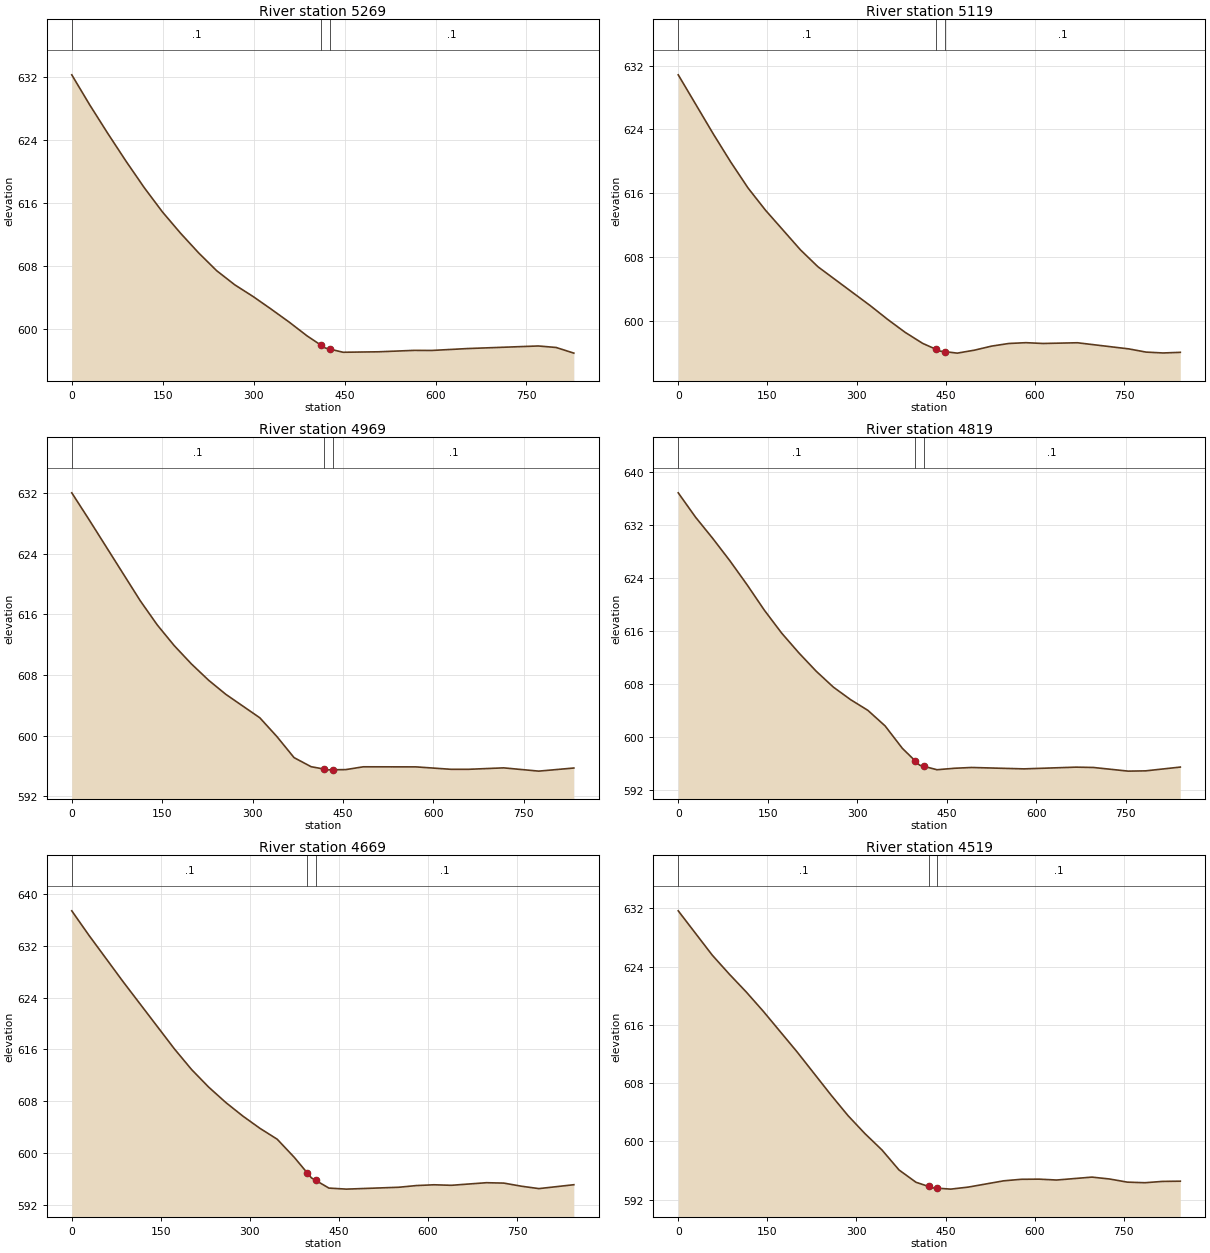
Type RM Length L Ch R = 1 ,5269,144.2,150,154.1
XS GIS Cut Line= 3
     2191294.950      635464.214     2191442.409      635855.687
     2191611.304      636229.158
#Sta/Elev= 25
       0  632.30    29.9  628.44    59.8  624.80    89.6  621.30   119.5  617.95
   149.4  614.87   179.3  612.16   209.2  609.65   239.0  607.38   268.9  605.58
   298.8  604.11   328.7  602.50   358.6  600.84   388.4  599.07   410.8  597.92
   418.3  597.54   425.8  597.40   447.6  597.00   506.2  597.06   564.7  597.24
   594.0  597.23   652.5  597.47   769.6  597.80   798.9  597.61   828.2  596.89
#Mann= 3 , 0 , 0
       0     0.1       0   410.8   0.045       0   425.8     0.1       0
Bank Sta=410.8,425.8
Exp/Cntr=0.3,0.1

Type RM Length L Ch R = 1 ,5119,144.7,150,160.7
XS GIS Cut Line= 3
     2191253.650      635477.837     2191305.405      635915.332
     2191397.125      636308.700
#Sta/Elev= 25
       0  630.84    58.7  623.46    88.1  619.93   117.5  616.64   146.8  613.86
   205.6  608.89   235.0  606.77   323.1  601.89   352.4  600.16   381.8  598.54
   411.2  597.16     433  596.44   440.6  596.19     448  596.13   469.4  595.94
   498.2  596.31   527.1  596.82   556.0  597.15   584.8  597.25   613.6  597.15
   671.4  597.24   757.9  596.47   786.8  596.07   815.6  595.96   844.5  596.04
#Mann= 3 , 0 , 0
       0     0.1       0     433   0.045       0     448     0.1       0
Bank Sta=433,448
Exp/Cntr=0.3,0.1

Type RM Length L Ch R = 1 ,4969,145.2,150,145
XS GIS Cut Line= 3
     2191210.555      635475.328     2191158.498      635897.766
     2191056.024      636292.207
#Sta/Elev= 23
       0  632.02    28.4  628.52   113.5  617.81   141.9  614.60   170.2  611.86
   198.6  609.46   227.0  607.32   255.4  605.47   312.1  602.36   340.5  599.88
   368.9  597.11   397.3  595.91   418.1  595.61   425.6  595.50   433.1  595.51
   454.7  595.53   483.8  595.90   571.2  595.89   629.4  595.57   658.5  595.57
   716.7  595.76   775.0  595.33   833.2  595.74
#Mann= 3 , 0 , 0
       0     0.1       0   418.1   0.045       0   433.1     0.1       0
Bank Sta=418.1,433.1
Exp/Cntr=0.3,0.1

Type RM Length L Ch R = 1 ,4819,160,150,144.5
XS GIS Cut Line= 3
     2191090.184      635448.143     2191026.665      635847.760
     2191015.669      636284.697
#Sta/Elev= 26
       0  636.81    28.9  633.15    57.8  629.94    86.7  626.55   115.6  622.92
   144.5  619.09   173.4  615.65   202.3  612.66   231.2  609.91   260.1  607.50
   289.0  605.61   317.9  604.00   346.8  601.65   375.7  598.27   397.1  596.39
   404.6  595.73   412.1  595.55   433.8  595.04   462.9  595.26   492.0  595.38
   579.5  595.17   666.9  595.43   696.0  595.38   754.3  594.83   783.4  594.87
   841.7  595.44
#Mann= 3 , 0 , 0
       0     0.1       0   397.1   0.045       0   412.1     0.1       0
Bank Sta=397.1,412.1
Exp/Cntr=0.3,0.1

Type RM Length L Ch R = 1 ,4669,146.8,150,144.4
XS GIS Cut Line= 3
     2190761.755      635469.747     2190878.945      635855.971
     2190972.697      636287.924
#Sta/Elev= 25
       0  637.38    28.8  633.62    86.5  626.44   173.0  616.06   201.8  612.89
   230.6  610.18   259.5  607.80   288.3  605.70   317.1  603.81   346.0  602.14
   374.8  599.34   396.1  597.00   403.6  596.18   411.1  595.78   433.1  594.60
   462.6  594.44   551.0  594.73   580.4  594.99   609.9  595.11   639.4  595.03
   698.3  595.43   727.8  595.37   757.2  594.89   786.7  594.52   845.6  595.12
#Mann= 3 , 0 , 0
       0     0.1       0   396.1   0.045       0   411.1     0.1       0
Bank Sta=396.1,411.1
Exp/Cntr=0.3,0.1

Type RM Length L Ch R = 1 ,4519,147.3,150,157.4
XS GIS Cut Line= 3
     2190629.485      635515.802     2190752.950      635926.380
     2190932.866      636301.728
#Sta/Elev= 27
       0  631.65    57.2  625.57    85.8  622.97   114.3  620.52   142.9  617.88
   200.1  612.27   257.2  606.35   285.8  603.52   314.4  601.04   343.0  598.80
   371.6  596.06   400.2  594.37   421.2  593.80   428.7  593.60   436.2  593.56
   458.5  593.43   488.2  593.71   547.7  594.57   577.4  594.78   607.1  594.80
   636.9  594.68   696.3  595.08   726.0  594.82   755.8  594.39   785.5  594.31
   815.2  594.49   845.0  594.52
#Mann= 3 , 0 , 0
       0     0.1       0   421.2   0.045       0   436.2     0.1       0
Bank Sta=421.2,436.2
Exp/Cntr=0.3,0.1

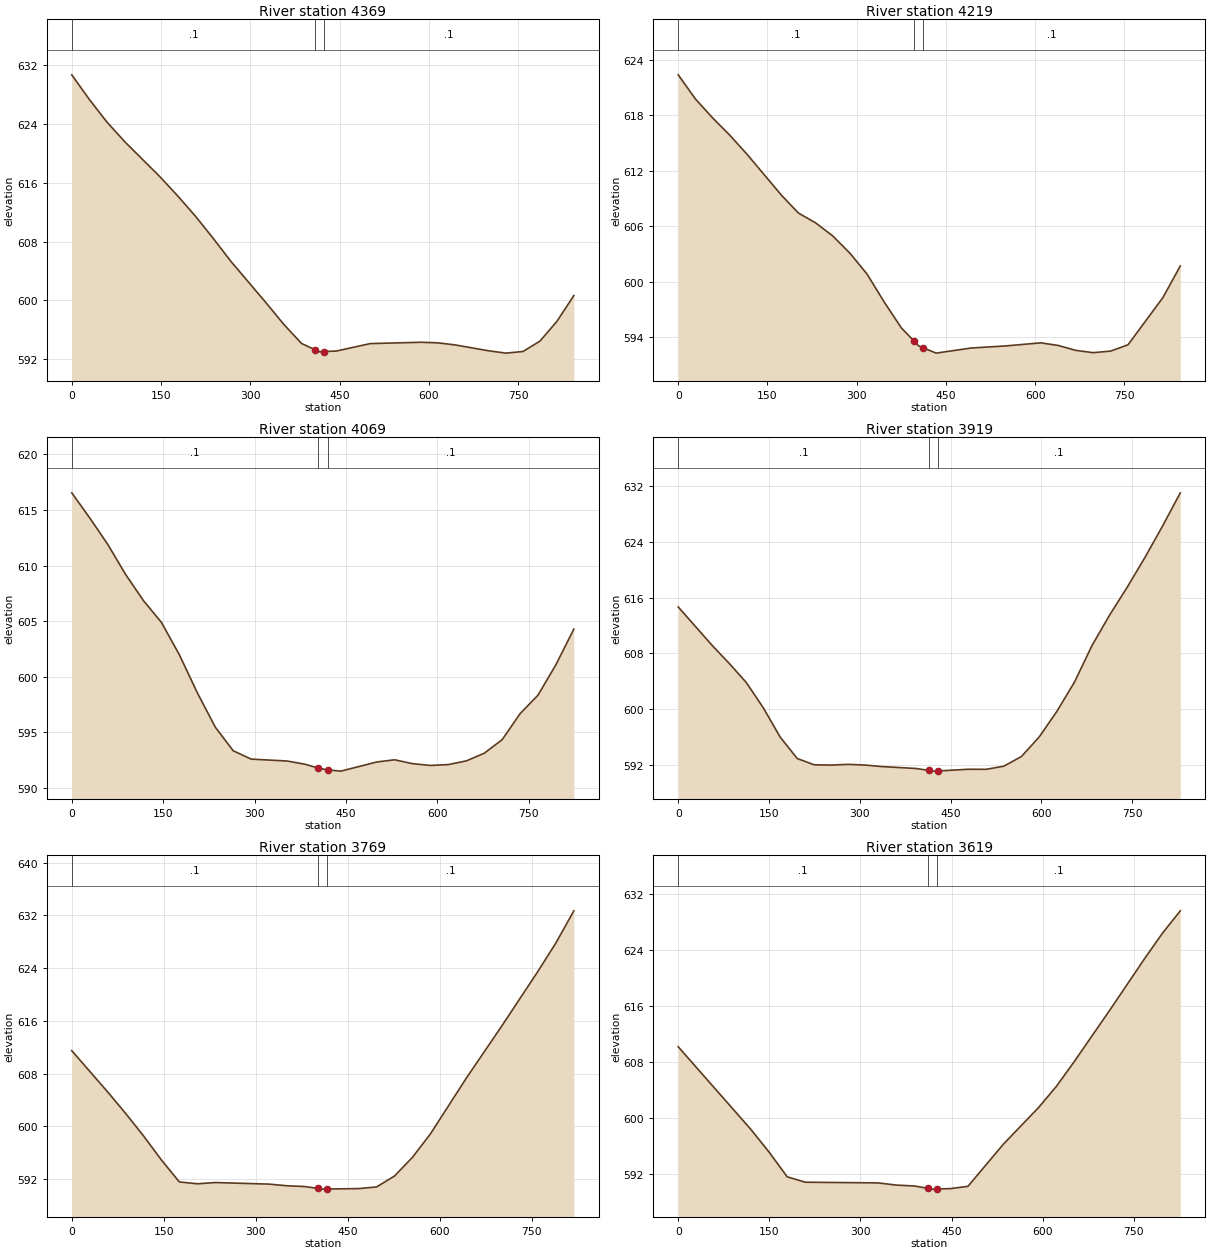
Type RM Length L Ch R = 1 ,4369,162,150,145.2
XS GIS Cut Line= 3
     2190590.397      635522.610     2190620.436      635937.260
     2190640.349      636364.218
#Sta/Elev= 26
       0  630.72    29.7  627.35    59.4  624.25    89.1  621.60   148.5  616.80
   178.2  614.20   207.9  611.44   237.6  608.43   267.3  605.30   326.6  599.63
   356.4  596.69   386.0  594.11   408.2  593.28   415.7  593.00   423.2  593.02
   444.2  593.08   501.2  594.10   586.7  594.28   615.2  594.20   643.7  593.92
   700.7  593.11   729.2  592.80   757.7  593.02   786.2  594.43   814.7  597.12
   843.2  600.64
#Mann= 3 , 0 , 0
       0     0.1       0   408.2   0.045       0   423.2     0.1       0
Bank Sta=408.2,423.2
Exp/Cntr=0.3,0.1

Type RM Length L Ch R = 1 ,4219,147,150,143.7
XS GIS Cut Line= 3
     2190243.738      635619.294     2190479.108      635947.752
     2190599.332      636370.763
#Sta/Elev= 27
       0  622.38    28.9  619.77    57.7  617.73    86.6  615.86   115.4  613.81
   173.2  609.39   202.0  607.44   230.9  606.38   259.8  604.96   288.6  603.10
   317.5  600.83   346.4  597.80   375.2  595.01   396.6  593.58   404.1  593.08
   411.6  592.88   433.4  592.30   492.0  592.85   550.7  593.08   609.3  593.41
   638.6  593.13   667.9  592.60   697.3  592.35   726.6  592.52   755.9  593.20
   814.5  598.30   843.8  601.72
#Mann= 3 , 0 , 0
       0     0.1       0   396.6   0.045       0   411.6     0.1       0
Bank Sta=396.6,411.6
Exp/Cntr=0.3,0.1

Type RM Length L Ch R = 1 ,4069,144.2,150,159.1
XS GIS Cut Line= 3
     2190160.360      635671.426     2190357.046      636033.711
     2190561.219      636391.348
#Sta/Elev= 28
       0  616.54    29.4  614.29    58.9  611.92    88.3  609.21   117.8  606.84
   147.2  604.89   176.7  601.97   206.1  598.56   235.6  595.47   265.0  593.35
   294.4  592.60   353.3  592.43   382.8  592.14   404.7  591.79   419.7  591.63
   441.6  591.52   500.5  592.34   529.9  592.54   559.3  592.19   588.7  592.03
   618.1  592.11   647.6  592.44   677.0  593.13   706.4  594.35   735.8  596.69
   765.2  598.35   794.6  601.09   824.0  604.29
#Mann= 3 , 0 , 0
       0     0.1       0   404.7   0.045       0   419.7     0.1       0
Bank Sta=404.7,419.7
Exp/Cntr=0.3,0.1

Type RM Length L Ch R = 1 ,3919,145.5,150,149.8
XS GIS Cut Line= 3
     2190120.431      635688.362     2190225.463      636096.244
     2190268.273      636502.242
#Sta/Elev= 29
       0  614.68    56.2  609.14    84.2  606.57   112.3  603.84   140.4  600.21
   168.5  595.97   196.6  592.90   224.6  592.00   252.7  591.96   280.8  592.06
   308.9  591.96   337.0  591.74   393.1  591.47   413.7  591.19   421.2  591.09
   428.7  591.11   479.5  591.36   508.7  591.35   537.8  591.80   567.0  593.19
   596.2  595.99   625.3  599.65   654.5  603.87   683.6  609.15   712.8  613.54
   742.0  617.56   771.1  621.81   800.3  626.34   829.4  631.08
#Mann= 3 , 0 , 0
       0     0.1       0   413.7   0.045       0   428.7     0.1       0
Bank Sta=413.7,428.7
Exp/Cntr=0.3,0.1

Type RM Length L Ch R = 1 ,3769,144.2,150,156.5
XS GIS Cut Line= 3
     2190044.032      635697.165     2190077.750      636105.275
     2190111.914      636513.347
#Sta/Elev= 24
       0  611.49    58.5  605.24    87.8  601.98   117.0  598.57   146.2  594.92
   175.5  591.58   204.8  591.30   234.0  591.49   321.8  591.25   351.0  591.00
   380.2  590.88     402  590.59   409.5  590.49     417  590.51   468.0  590.57
   497.2  590.82   526.5  592.48   555.8  595.32   585.0  598.86   643.5  607.31
   702.0  615.31   760.5  623.53   789.8  627.84   819.0  632.70
#Mann= 3 , 0 , 0
       0     0.1       0     402   0.045       0     417     0.1       0
Bank Sta=402,417
Exp/Cntr=0.3,0.1

Type RM Length L Ch R = 1 ,3619,145.3,150,153.8
XS GIS Cut Line= 3
     2189999.501      635696.798     2189928.402      636109.338
     2189844.545      636508.515
#Sta/Elev= 21
       0  610.19   119.6  598.36   149.5  595.12   179.4  591.57   209.3  590.80
   328.9  590.70   358.8  590.39   388.7  590.26   411.1  589.92   418.6  589.81
   426.1  589.83   447.8  589.88   476.9  590.21   535.2  596.24   593.4  601.51
   622.6  604.53   651.7  608.04   710.0  615.38   768.2  622.87   797.4  626.48
   826.5  629.65
#Mann= 3 , 0 , 0
       0     0.1       0   411.1   0.045       0   426.1     0.1       0
Bank Sta=411.1,426.1
Exp/Cntr=0.3,0.1