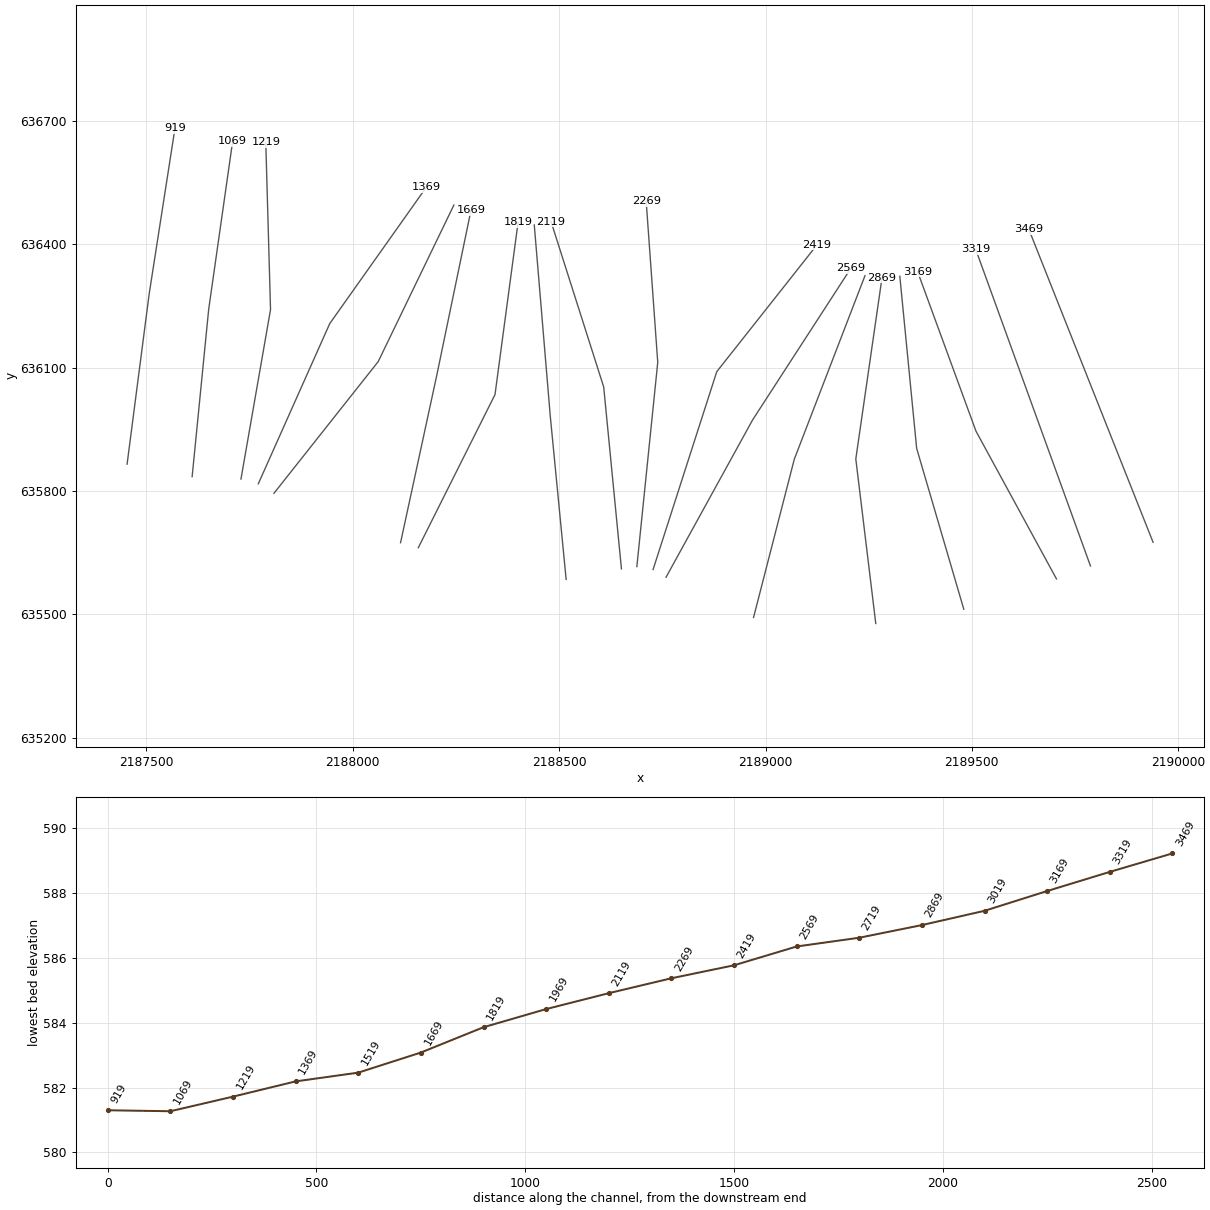
HEC-RAS study LFRFBUCKRV.prj: LFRFBUCKRV

--- LFRFBUCKRV.g01 (geometry) --- (continued)

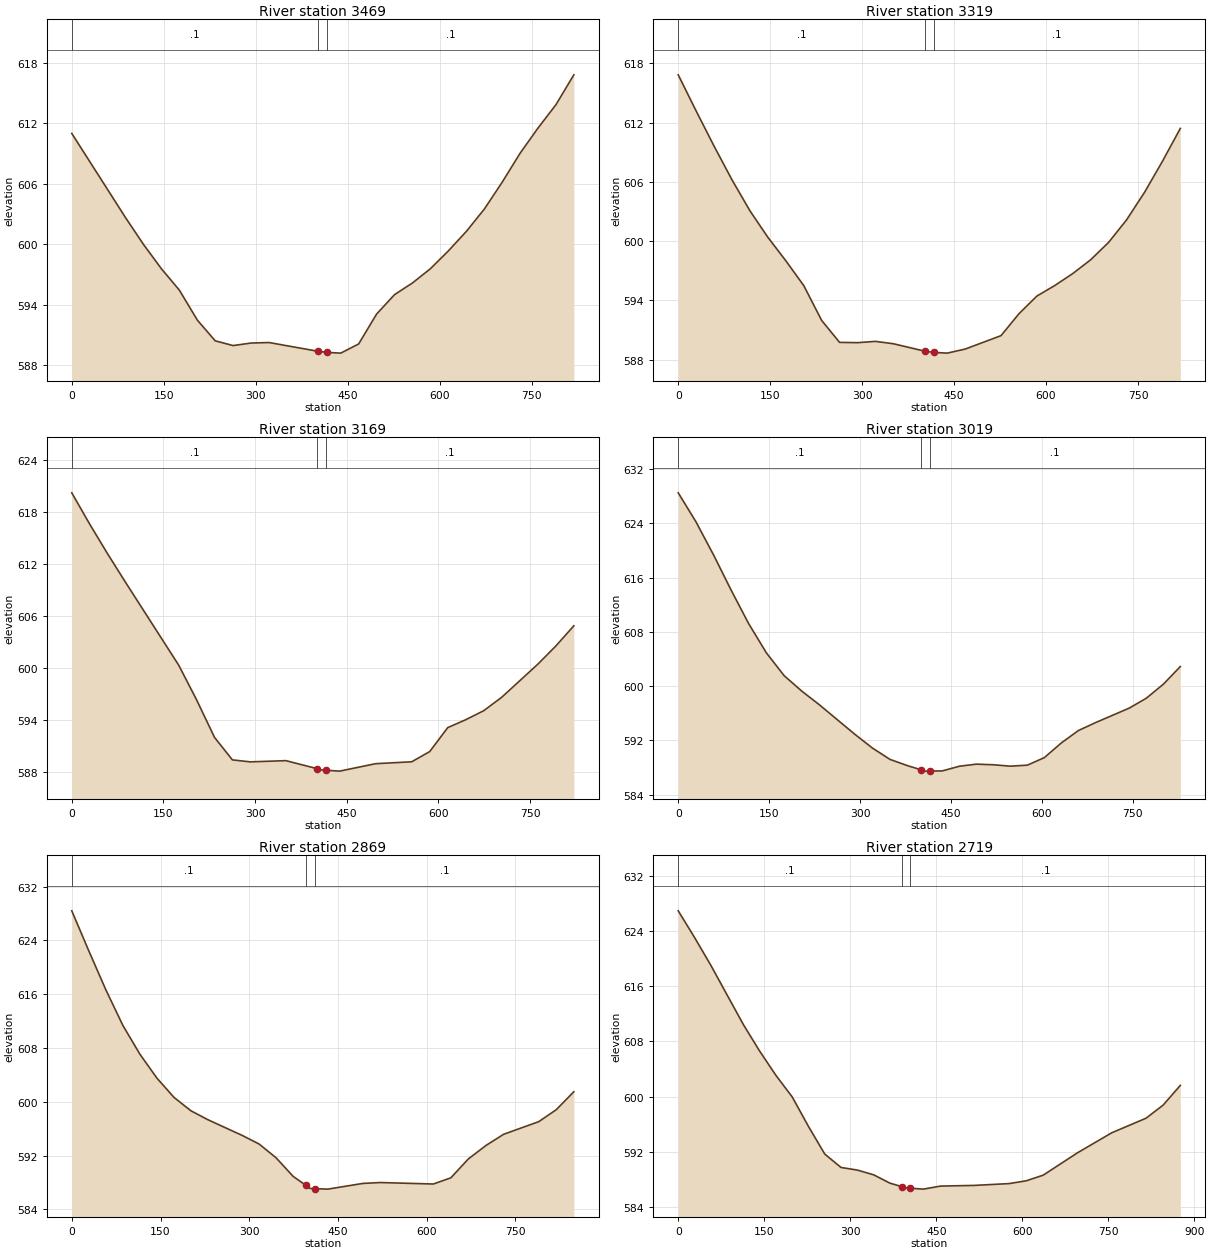
Type RM Length L Ch R = 1 ,3469,150.6,150,149.2
XS GIS Cut Line= 3
     2189939.108      635675.208     2189788.524      636056.016
     2189637.941      636436.824
#Sta/Elev= 26
       0  611.01    87.8  602.65   117.0  600.00   146.2  597.59   175.5  595.47
   204.8  592.50   234.0  590.44   263.2  589.97   292.5  590.22   321.8  590.27
     402  589.40     417  589.29   438.8  589.22   468.0  590.13   497.2  593.09
   526.5  595.02   555.8  596.18   585.0  597.59   614.2  599.35   643.5  601.28
   672.8  603.49   702.0  606.16   731.2  609.03   760.5  611.54   789.8  613.86
   819.0  616.82
#Mann= 3 , 0 , 0
       0     0.1       0     402   0.045       0     417     0.1       0
Bank Sta=402,417
Exp/Cntr=0.3,0.1

Type RM Length L Ch R = 1 ,3319,146.6,150,150.1
XS GIS Cut Line= 3
     2189787.413      635617.530     2189648.363      636002.700
     2189509.313      636387.869
#Sta/Elev= 28
       0  616.85    29.2  613.19    58.5  609.62    87.8  606.20   117.0  603.07
   146.2  600.39   175.5  598.01   204.8  595.49   234.0  591.96   263.2  589.74
   292.5  589.71   321.8  589.84   351.0  589.60     402  588.85     417  588.72
   438.8  588.65   468.0  589.06   526.5  590.42   555.8  592.64   585.0  594.43
   614.2  595.50   643.5  596.71   672.8  598.11   702.0  599.87   731.2  602.14
   760.5  604.93   789.8  608.08   819.0  611.42
#Mann= 3 , 0 , 0
       0     0.1       0     402   0.045       0     417     0.1       0
Bank Sta=402,417
Exp/Cntr=0.3,0.1

Type RM Length L Ch R = 1 ,3169,154.7,150,144.2
XS GIS Cut Line= 3
     2189705.062      635586.013     2189510.024      635945.396
     2189368.566      636333.333
#Sta/Elev= 24
       0  620.23    29.2  616.63    58.4  613.21    87.6  609.93   175.2  600.29
   204.4  596.29   233.6  591.97   262.9  589.36   292.1  589.13   350.5  589.27
   401.4  588.35   408.9  588.20   416.4  588.16   438.4  588.06   497.4  588.92
   556.4  589.14   585.9  590.32   615.4  593.09   644.8  594.00   674.4  595.05
   703.8  596.60   762.8  600.42   792.3  602.52   821.8  604.86
#Mann= 3 , 0 , 0
       0     0.1       0   401.4   0.045       0   416.4     0.1       0
Bank Sta=401.4,416.4
Exp/Cntr=0.3,0.1

Type RM Length L Ch R = 1 ,3019,153.7,150,144.3
XS GIS Cut Line= 3
     2189480.447      635512.339     2189366.263      635903.560
     2189325.455      636322.162
#Sta/Elev= 30
       0  628.50    29.1  624.25    58.2  619.35    87.3  614.14   116.4  609.17
   145.6  604.87   174.7  601.53   203.8  599.25   232.9  597.23   291.1  592.90
   320.2  590.86   349.3  589.18   378.4  588.25     400  587.66   407.5  587.45
     415  587.46   435.6  587.48   463.6  588.17   491.7  588.48   519.7  588.39
   547.7  588.18   575.8  588.33   603.8  589.44   631.9  591.61   659.9  593.43
   687.9  594.59   744.0  596.75   772.0  598.20   800.1  600.27   828.1  602.87
#Mann= 3 , 0 , 0
       0     0.1       0     400   0.045       0     415     0.1       0
Bank Sta=400,415
Exp/Cntr=0.3,0.1

Type RM Length L Ch R = 1 ,2869,158.3,150,144.9
XS GIS Cut Line= 3
     2189267.164      635477.524     2189218.802      635877.747
     2189282.314      636318.772
#Sta/Elev= 27
       0  628.39    28.8  622.44    57.6  616.65    86.4  611.35   115.2  607.07
   144.0  603.51   172.8  600.65   201.6  598.65   230.4  597.32   288.0  595.00
   316.8  593.71   345.5  591.66   374.3  588.90   395.6  587.58   403.1  587.11
   410.6  587.08   432.8  587.01   492.2  587.86   522.0  587.99   611.1  587.77
   640.8  588.69   670.5  591.51   700.2  593.50   729.9  595.16   789.3  597.04
   819.0  598.82   848.7  601.49
#Mann= 3 , 0 , 0
       0     0.1       0   395.6   0.045       0   410.6     0.1       0
Bank Sta=395.6,410.6
Exp/Cntr=0.3,0.1

Type RM Length L Ch R = 1 ,2719,150.8,150,146.4
XS GIS Cut Line= 3
     2188971.016      635492.295     2189069.752      635877.223
     2189241.030      636323.621
#Sta/Elev= 27
       0  626.92    28.4  623.07    56.8  619.04   113.5  610.46   141.9  606.62
   170.3  603.10   198.7  599.98   227.1  595.70   255.5  591.70   283.8  589.76
   312.2  589.38   340.6  588.70   369.0  587.49   389.9  586.98   397.4  586.80
   404.9  586.75   427.3  586.62   457.2  587.06   516.9  587.16   576.7  587.42
   606.6  587.82   636.4  588.64   696.2  591.88   756.0  594.78   815.8  596.89
   845.6  598.79   875.5  601.64
#Mann= 3 , 0 , 0
       0     0.1       0   389.9   0.045       0   404.9     0.1       0
Bank Sta=389.9,404.9
Exp/Cntr=0.3,0.1

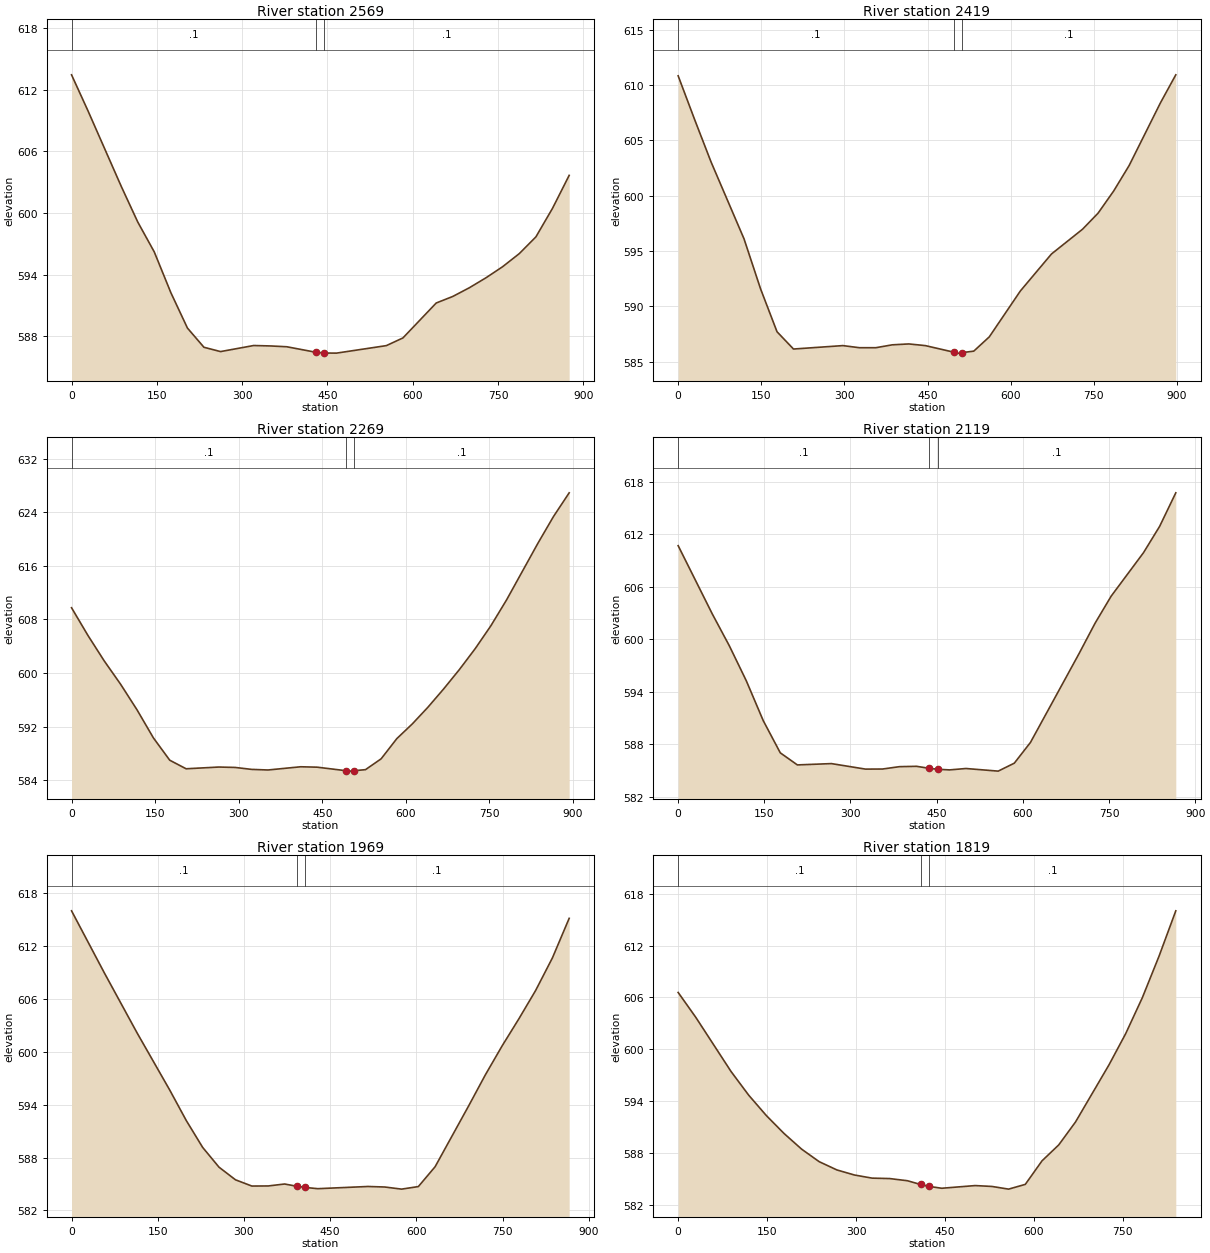
Type RM Length L Ch R = 1 ,2569,149.7,150,145.8
XS GIS Cut Line= 3
     2188758.962      635590.098     2188968.819      635972.959
     2189206.555      636341.256
#Sta/Elev= 26
       0  613.45    29.1  609.92    87.3  602.60   116.4  599.12   145.5  596.20
   174.6  592.24   203.8  588.79   232.8  586.92   262.0  586.50   320.2  587.09
   349.3  587.05   378.4  586.97   429.1  586.44   444.1  586.36   465.8  586.35
   553.5  587.08   582.7  587.83   641.2  591.23   670.4  591.87   699.6  592.72
   728.8  593.69   758.1  594.77   787.3  596.04   816.5  597.67   845.7  600.45
   875.0  603.66
#Mann= 3 , 0 , 0
       0     0.1       0   429.1   0.045       0   444.1     0.1       0
Bank Sta=429.1,444.1
Exp/Cntr=0.3,0.1

Type RM Length L Ch R = 1 ,2419,145.2,150,166.7
XS GIS Cut Line= 3
     2188727.581      635608.911     2188881.844      636090.117
     2189124.720      636398.560
#Sta/Elev= 26
       0  610.83    29.7  606.88    59.4  603.04   118.9  596.09   148.6  591.59
   178.4  587.70   208.1  586.14   297.2  586.45   327.0  586.26   356.7  586.26
   386.4  586.52   416.2  586.60   445.9  586.45   497.8  585.85   505.3  585.77
   512.8  585.82   533.4  585.95   561.4  587.24   617.5  591.39   673.6  594.73
   729.7  596.97   757.7  598.42   785.8  600.42   813.8  602.73   869.9  608.36
   897.9  610.92
#Mann= 3 , 0 , 0
       0     0.1       0   497.8   0.045       0   512.8     0.1       0
Bank Sta=497.8,512.8
Exp/Cntr=0.3,0.1

Type RM Length L Ch R = 1 ,2269,148.5,150,153.7
XS GIS Cut Line= 3
     2188688.241      635616.052     2188738.861      636112.820
     2188710.784      636505.460
#Sta/Elev= 30
       0  609.75    29.4  605.62    58.8  601.80    88.1  598.33   117.5  594.52
   146.9  590.33   176.2  587.00   205.6  585.72   264.4  585.98   293.7  585.92
   323.1  585.63   352.5  585.54   411.2  586.02   440.6  585.96   491.8  585.44
   499.3  585.37   506.8  585.43   527.5  585.59   555.6  587.21   583.7  590.22
   611.8  592.44   639.9  594.94   668.0  597.66   696.2  600.55   724.3  603.64
   752.4  607.05   780.5  610.90   836.8  619.36   864.9  623.37   893.0  626.90
#Mann= 3 , 0 , 0
       0     0.1       0   491.8   0.045       0   506.8     0.1       0
Bank Sta=491.8,506.8
Exp/Cntr=0.3,0.1

Type RM Length L Ch R = 1 ,2119,146.1,150,146.2
XS GIS Cut Line= 3
     2188650.879      635610.458     2188607.854      636052.999
     2188480.362      636454.981
#Sta/Elev= 25
       0  610.68    59.3  602.89    88.9  599.26   118.6  595.24   148.2  590.67
   177.8  587.00   207.5  585.62   266.8  585.77   326.1  585.14   355.7  585.15
   385.3  585.42   415.0  585.46   437.1  585.23   452.1  585.12   472.7  585.05
   500.9  585.21   557.1  584.91   585.2  585.82   613.3  588.19   697.7  598.32
   725.8  601.82   753.9  604.92   810.1  609.88   838.2  612.89   866.3  616.72
#Mann= 3 , 0 , 0
       0     0.1       0   437.1   0.045       0   452.1     0.1       0
Bank Sta=437.1,452.1
Exp/Cntr=0.3,0.1

Type RM Length L Ch R = 1 ,1969,162.4,150,145
XS GIS Cut Line= 3
     2188516.904      635584.760     2188478.414      635982.139
     2188439.652      636447.058
#Sta/Elev= 26
       0  616.02    57.0  608.98   114.1  602.15   171.1  595.64   199.6  592.21
   228.1  589.16   256.6  586.91   285.2  585.48   313.7  584.77   342.2  584.78
   370.7  585.00   391.7  584.75   406.7  584.61   428.4  584.47   515.9  584.72
   545.0  584.66   574.2  584.42   603.4  584.71   632.5  586.96   690.8  593.86
   720.0  597.40   749.1  600.68   778.3  603.76   807.4  606.97   836.6  610.67
   865.8  615.17
#Mann= 3 , 0 , 0
       0     0.1       0   391.7   0.045       0   406.7     0.1       0
Bank Sta=391.7,406.7
Exp/Cntr=0.3,0.1

Type RM Length L Ch R = 1 ,1819,144.3,150,147.9
XS GIS Cut Line= 3
     2188158.634      635661.905     2188344.517      636034.413
     2188400.454      636453.672
#Sta/Elev= 28
       0  606.58    29.7  603.71    89.2  597.45   119.0  594.71   148.7  592.36
   178.4  590.30   208.2  588.48   237.9  587.03   267.6  586.08   297.4  585.49
   327.1  585.13   356.8  585.08   386.6  584.83   408.8  584.40   423.8  584.17
   444.5  583.96   500.9  584.27   529.1  584.17   557.3  583.86   585.5  584.41
   613.7  587.13   641.9  588.97   670.1  591.61   726.5  598.20   754.7  601.81
   782.9  605.98   811.1  610.78   839.3  616.01
#Mann= 3 , 0 , 0
       0     0.1       0   408.8   0.045       0   423.8     0.1       0
Bank Sta=408.8,423.8
Exp/Cntr=0.3,0.1

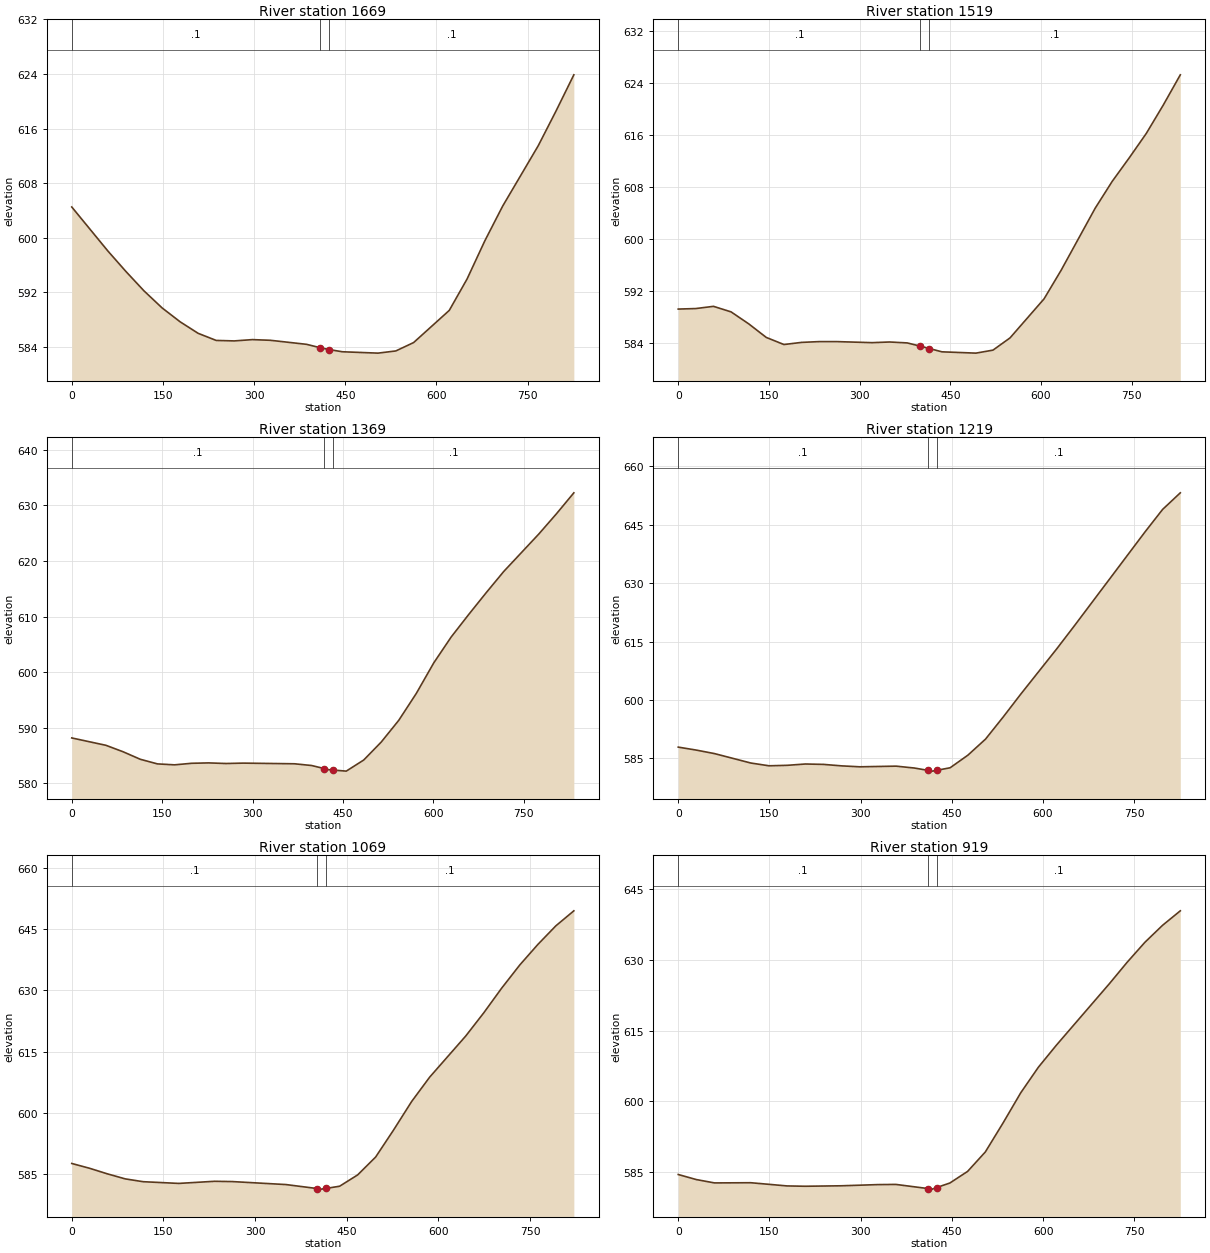
Type RM Length L Ch R = 1 ,1669,160.2,150,144
XS GIS Cut Line= 3
     2188115.627      635674.036     2188203.273      636080.735
     2188286.231      636482.354
#Sta/Elev= 25
       0  604.50    59.4  598.05    89.2  595.04   118.9  592.20   148.6  589.71
   178.3  587.67   208.0  585.98   237.7  584.94   267.4  584.87   297.2  585.06
   326.9  584.96   386.3  584.37   408.5  583.88   423.5  583.60   445.3  583.28
   503.9  583.08   533.2  583.40   562.5  584.63   621.1  589.34   650.4  593.94
   679.7  599.55   709.0  604.63   767.6  613.49   796.8  618.57   826.1  623.87
#Mann= 3 , 0 , 0
       0     0.1       0   408.5   0.045       0   423.5     0.1       0
Bank Sta=408.5,423.5
Exp/Cntr=0.3,0.1

Type RM Length L Ch R = 1 ,1519,144.1,150,146.5
XS GIS Cut Line= 3
     2187808.804      635794.253     2188061.462      636114.604
     2188244.819      636495.362
#Sta/Elev= 27
       0  589.23    29.1  589.31    58.3  589.65    87.4  588.80   116.6  586.96
   145.7  584.87   174.9  583.78   204.0  584.11   233.1  584.23   262.3  584.23
   320.6  584.07   349.7  584.17   378.8  584.03   400.5  583.53   415.5  583.17
   436.2  582.66   492.5  582.46   520.7  582.92   548.9  584.80   605.2  590.80
   633.4  595.19   689.7  604.72   717.9  608.85   746.1  612.47   774.3  616.22
   802.4  620.58   830.6  625.23
#Mann= 3 , 0 , 0
       0     0.1       0   400.5   0.045       0   415.5     0.1       0
Bank Sta=400.5,415.5
Exp/Cntr=0.3,0.1

Type RM Length L Ch R = 1 ,1369,144.5,150,164.4
XS GIS Cut Line= 3
     2187771.028      635817.593     2187944.069      636207.148
     2188178.416      636539.350
#Sta/Elev= 28
       0  588.16    56.8  586.83    85.2  585.67   113.7  584.32   142.1  583.49
   170.5  583.32   198.9  583.60   227.3  583.67   255.8  583.56   284.2  583.63
   369.4  583.51   397.8  583.20   418.8  582.65   426.3  582.45   433.8  582.38
   455.3  582.19   484.3  584.19   513.4  587.43   542.4  591.33   571.4  596.15
   600.5  601.67   629.5  606.34   658.6  610.39   687.6  614.31   716.6  618.11
   774.7  624.84   803.8  628.46   832.8  632.25
#Mann= 3 , 0 , 0
       0     0.1       0   418.8   0.045       0   433.8     0.1       0
Bank Sta=418.8,433.8
Exp/Cntr=0.3,0.1

Type RM Length L Ch R = 1 ,1219,148.3,150,146.1
XS GIS Cut Line= 3
     2187728.911      635828.933     2187800.561      636241.023
     2187789.015      636648.811
#Sta/Elev= 25
       0  587.89    29.9  587.12    59.8  586.22   119.5  583.80   149.4  583.09
   179.3  583.21   209.1  583.55   239.0  583.45   268.9  583.07   298.8  582.83
   358.5  583.00   388.4  582.52   410.8  581.92   418.3  581.72   425.8  581.94
   447.4  582.58   476.6  585.81   505.7  589.95   534.8  595.64   564.0  601.57
   622.2  613.01   651.4  618.96   768.0  643.16   797.1  648.97   826.2  653.23
#Mann= 3 , 0 , 0
       0     0.1       0   410.8   0.045       0   425.8     0.1       0
Bank Sta=410.8,425.8
Exp/Cntr=0.3,0.1

Type RM Length L Ch R = 1 ,1069,150.2,150,149.2
XS GIS Cut Line= 3
     2187610.610      635834.813     2187650.688      636241.730
     2187708.771      636650.512
#Sta/Elev= 25
       0  587.56    29.2  586.38    58.4  585.01    87.6  583.78   116.8  583.09
   175.2  582.67   233.6  583.19   262.8  583.12   350.5  582.39   401.4  581.42
   408.9  581.27   416.4  581.45   438.4  581.98   467.9  584.75   497.4  589.14
   526.8  595.78   556.4  602.77   585.8  608.72   644.8  618.80   674.3  624.48
   703.8  630.57   733.3  636.22   762.8  641.24   792.3  645.81   821.8  649.50
#Mann= 3 , 0 , 0
       0     0.1       0   401.4   0.045       0   416.4     0.1       0
Bank Sta=401.4,416.4
Exp/Cntr=0.3,0.1

Type RM Length L Ch R = 1 ,919,926.3,919,909.3
XS GIS Cut Line= 3
     2187452.976      635865.203     2187506.484      636279.253
     2187569.050      636682.403
#Sta/Elev= 24
       0  584.41    29.8  583.33    59.6  582.62   119.3  582.66   178.9  581.98
   208.8  581.91   268.4  582.01   328.0  582.26   357.8  582.30     410  581.43
   417.5  581.30     425  581.64   446.6  582.60   475.8  585.07   504.9  589.20
   534.1  595.37   563.2  601.79   592.3  607.24   621.5  611.86   708.9  624.97
   738.0  629.51   767.2  633.76   796.3  637.38   825.5  640.46
#Mann= 3 , 0 , 0
       0     0.1       0     410   0.045       0     425     0.1       0
Bank Sta=410,425
Exp/Cntr=0.3,0.1